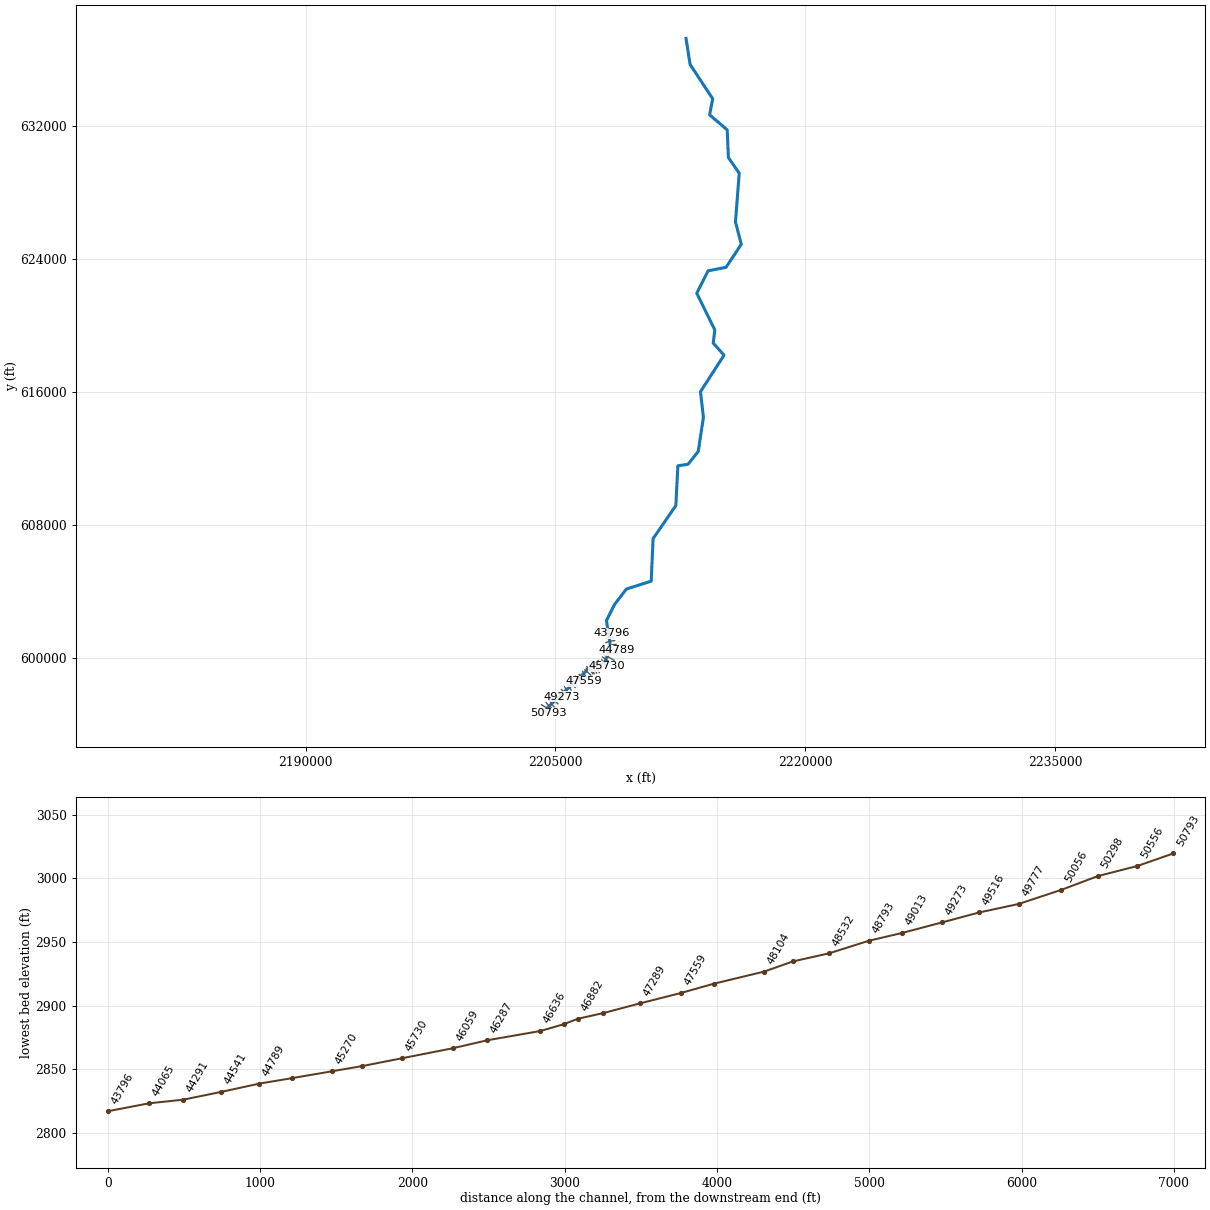
--- LFBUCKRV.prj (project) ---

Proj Title=LFBUCKRV
Current Plan=p01
Default Exp/Contr=0,0
English Units
Geom File=g01
Flow File=f01
Plan File=p01
Background Map Layer=Inundation Boundary (P100yr Value_0)
BEGIN DESCRIPTION:
----------MODEL BY WOOD PLC 2022----------
AFH study
Randolph County, WV
HEC-RAS Version: RAS 6.2
Vertical Datum: NAVD88
Projection: NAD 1983 StatePlane West Virginia S FIPS 4702 (US Feet)
Terrain: 1-meter LIDAR (FEMA Region III 3DEP collected 2016-2018)
Land Use: 2019 NLCD
Hydrologic Method:
WV SIR2010-5033 regression equations
Additional Model Notes:
None
END DESCRIPTION:
DSS Export Rating Curves= 0
DSS Export Rating Curve Sorted= 0
DSS Export Volume Flow Curves= 0
DXF OffsetX= 0
DXF OffsetY= 0
DXF ScaleX= 0
DXF ScaleY= 0

--- LFBUCKRV.p01 (plan) ---

Plan Title=Floodplain
Program Version=6.20
Short Identifier=Floodplain
Geom File=g01
Flow File=f01
Subcritical Flow
K Sum by GR= 0
Std Step Tol= 0.01
Critical Tol= 0.01
Num of Std Step Trials= 20
Max Error Tol= 0.3
Flow Tol Ratio= 0.001
Split Flow NTrial= 30
Split Flow Tol= 0.02
Split Flow Ratio= 0.02
Log Output Level= 0
Friction Slope Method= 1
Unsteady Friction Slope Method= 2
Unsteady Bridges Friction Slope Method= 1
Parabolic Critical Depth
Global Vel Dist= 0 , 0 , 0
Global Log Level= 0
CheckData=False
Encroach Param=-1 ,0,0, 0
Mapping Interval=1HOUR
Computation Time Step Use Courant=        0
Computation Time Step Use Time Series=    0
Computation Time Step Count To Double=0
Computation Time Step Max Doubling=0
Computation Time Step Max Halving=0
Computation Time Step Residence Courant=0
Run HTab= 0
Run UNet= 0
Run Sediment= 0
Run PostProcess= 0
Run WQNet= 0
Run RASMapper=-1
UNET Theta= 0
UNET Theta Warmup= 0
UNET ZTol= 0
UNET ZSATol= 0
UNET MxIter= 0
UNET Max Iter WO Improvement= 0
UNET MaxInSteps= 0
UNET DtIC= 0
UNET DtMin= 0
UNET MaxCRTS= 0
UNET WFStab= 0
UNET SFStab= 0
UNET WFX= 1
UNET SFX= 1
UNET Gravity=32.174
UNET 1D Methodology=Finite Difference
UNET DSS MLevel= 1
UNET Pardiso=0
UNET DZMax Abort= 0
UNET Use Existing IB Tables= 0
UNET Froude Reduction=False
UNET Froude Limit= 0
UNET Froude Power= 0
UNET D1 Cores= 0
UNET WindReference=Eulerian
UNET WindDragFormulation=Hsu (1988)
UNET D2 Coriolis=0
UNET D2 Cores= 0
UNET D2 Theta= 1
UNET D2 Theta Warmup= 1
UNET D2 Z Tol= 0.01
UNET D2 Volume Tol= 0.01
UNET D2 Max Iterations= 20
UNET D2 Equation= 0
UNET D2 RampUpFraction=0.1
UNET D2 TimeSlices= 1
UNET D2 Turbulence Formulation=Non-Conservative (original)
UNET D2 Eddy Viscosity=0.3
UNET D2 Transverse Eddy Viscosity=0.1
UNET D2 Smagorinsky Mixing=0
UNET D2 BCVolumeCheck=0
UNET D2 Cores=0
UNET D2 SolverType=PARDISO (Direct)
UNET D2 Minimum Iterations= 2147483647
UNET D2 Maximum Iterations= 2147483647
UNET D2 Restart Number= 10
UNET D2 Relaxation Coeff=1.3
UNET D2 SOR Precondition Iterations= 10
UNET D2 ILUT Maximum Fill= 8
UNET D2 ILUT Tolerance=1E-08
UNET D1D2 MaxIter= 0
UNET D1D2 ZTol=0.01
UNET D1D2 QTol=0.1
UNET D1D2 MinQTol=1
Write IC File= 0
Write IC File at Fixed DateTime=0
Write IC File at Sim End=0
Echo Input=False
Echo Parameters=False
Echo Output=False
Write Detailed= 0
HDF Write Warmup=0
HDF Write Time Slices=0
HDF Flush=0
HDF Compression= 1
HDF Chunk Size= 1
HDF Spatial Parts= 1
HDF Use Max Rows=0
HDF Fixed Rows= 1
Calibration Method= 0
Calibration Iterations= 20
Calibration Max Change=0.05
Calibration Tolerance=0.2
Calibration Maximum=1.5
Calibration Minimum=0.5
Calibration Optimization Method= 1
WQ AD Non Conservative
WQ ULTIMATE=-1
WQ Max Comp Step=1HOUR
WQ Output Interval=15MIN
WQ Output Selected Increments= 0
WQ Output face flow=0
WQ Output face velocity=0
WQ Output face area=0
WQ Output face dispersion=0
WQ Output cell volume=0
WQ Output cell surface area=0
WQ Output cell continuity=0
WQ Output cumulative cell continuity=0
WQ Output face conc=0
WQ Output face dconc_dx=0
WQ Output face courant=0
WQ Output face peclet=0
WQ Output face adv mass=0
WQ Output face disp mass=0
WQ Output cell mass=0
WQ Output cell source sink temp=0
WQ Output nsm pathways=0
WQ Output nsm derived pathways=0
WQ Create Restart=0
WQ Fixed Restart=0
WQ System Summary=0
WQ Write To DSS=0
Sorting and Armoring Iterations= 10
XS Update Threshold= 0.02
Bed Roughness Predictor= 0
Hydraulics Update Threshold= 0.02
Energy Slope Method= 1
Volume Change Method= 1
Sediment Retention Method= 0
Sediment TS Multiplier= 1
Warm Up Method= 0
XS Weighting Method= 0
Number of US Weighted Cross Sections= 1
Number of DS Weighted Cross Sections= 1
Upstream XS Weight=0
Main XS Weight=1
Downstream XS Weight=0
Number of DS XS's Weighted with US Boundary= 1
Upstream Boundary Weight= 1
Weight of XSs Associated with US Boundary= 0
Number of US XS's Weighted with DS Boundary= 1
Downstream Boundary Weight= 0.5
Weight of XSs Associated with DS Boundary= 0.5
Percentile Method= 0
Sediment Output Level= 3
Mass or Volume Output= 0
Output Increment Type= 1
Profile and TS Output Increment= 1
Transport Output Increment 1
XS Output Flag= 0
XS Output Increment= 10
Read HDF5 Sediment Hotstart= 0
Sediment Hotstart Type= 0
Write Gradation File= 0
Read Gradation Hotstart= 0
Write HDF5 File= 1
Write Binary Output= 1
Write DSS Sediment File= 0
DSS Sediment Output Type= 1
SV Curve= 0
Specific Gage Flag= 0
Subcell Erosion Methods= 0
Subcell Deposition Methods= 0
Advection Scheme= 1
Matrix Solver= 0
Implicit Weighting Factor= 1
Maximum Outer Loop Convergence Iterations= 5
Convergence Maximum Absolute= 0.001
Convergence RMSE= 0.0001
Grain Fractions Max Abs Error= 0.001
Max Subgrid Regions= 1
Max Subgrid Length Scale= 3.402823E+38
Initial Layer Thickness= 3.402823E+38
Min Layer Thickness= 3.402823E+38
Max Layer Thickness= 3.402823E+38
Number of Layers= 5

--- LFBUCKRV.f01 (steady flow) ---

Flow Title=Flow
Program Version=6.20
Number of Profiles= 1
Profile Names=P100yr
River Rch & RM=LFBUCKRV,Main            ,50793
     525
River Rch & RM=LFBUCKRV,Main            ,47049
     585
River Rch & RM=LFBUCKRV,Main            ,45730
     768
River Rch & RM=LFBUCKRV,Main            ,44065
     864
River Rch & RM=LFBUCKRV,Main            ,42281
     967
River Rch & RM=LFBUCKRV,Main            ,39016
    1620
River Rch & RM=LFBUCKRV,Main            ,35300
    1800
River Rch & RM=LFBUCKRV,Main            ,31536
    2000
River Rch & RM=LFBUCKRV,Main            ,23083
    3250
River Rch & RM=LFBUCKRV,Main            ,10590
    3860
River Rch & RM=LFBUCKRV,Main            ,554
    4710
Boundary for River Rch & Prof#=LFBUCKRV,Main            , 1
Up Type= 0
Dn Type= 1
Dn Known WS=2152.55
DSS Import GetInterval= 0
DSS Import GetPeak= 0
DSS Import FillOption= 0

--- LFBUCKRV.g01 (geometry) ---

Geom Title=Geometry
Program Version=6.20

River Reach=LFBUCKRV        ,Main
Reach XY= 30
2204321.10500003596813.9570000172207196.22799999599536.930000022
2207940.55700003599688.6190000032208318.51000002600599.103000015
2208068.33700001602245.6749999972208550.86300001603209.122000009
2209263.00700001604140.7600000052210753.81999999 604613.58600001
2210868.44999999607171.016000003     2212232.932609154.797000021
2212356.93300004611546.7950000022212971.98100005611642.583000019
2213579.93100002612414.027999997     2213891.066614460.820000008
2213714.36399999616001.0410000092215127.93900001618194.140000001
2214478.46100001618924.4500000182214575.54100001619712.272000015
2213489.85100003621919.4430000042214173.59100004623267.123000011
2215248.22499999623476.657000005     2216165.514624861.158999994
2215817.07600003626204.3879999972216041.05500001629134.157000005
2215390.68799999630071.5820000172215319.16000003631739.111000001
2214263.96700001632641.0590000152214449.40700005633604.694999993
     2213090.007635669.8040000052212846.95428828637238.904383142

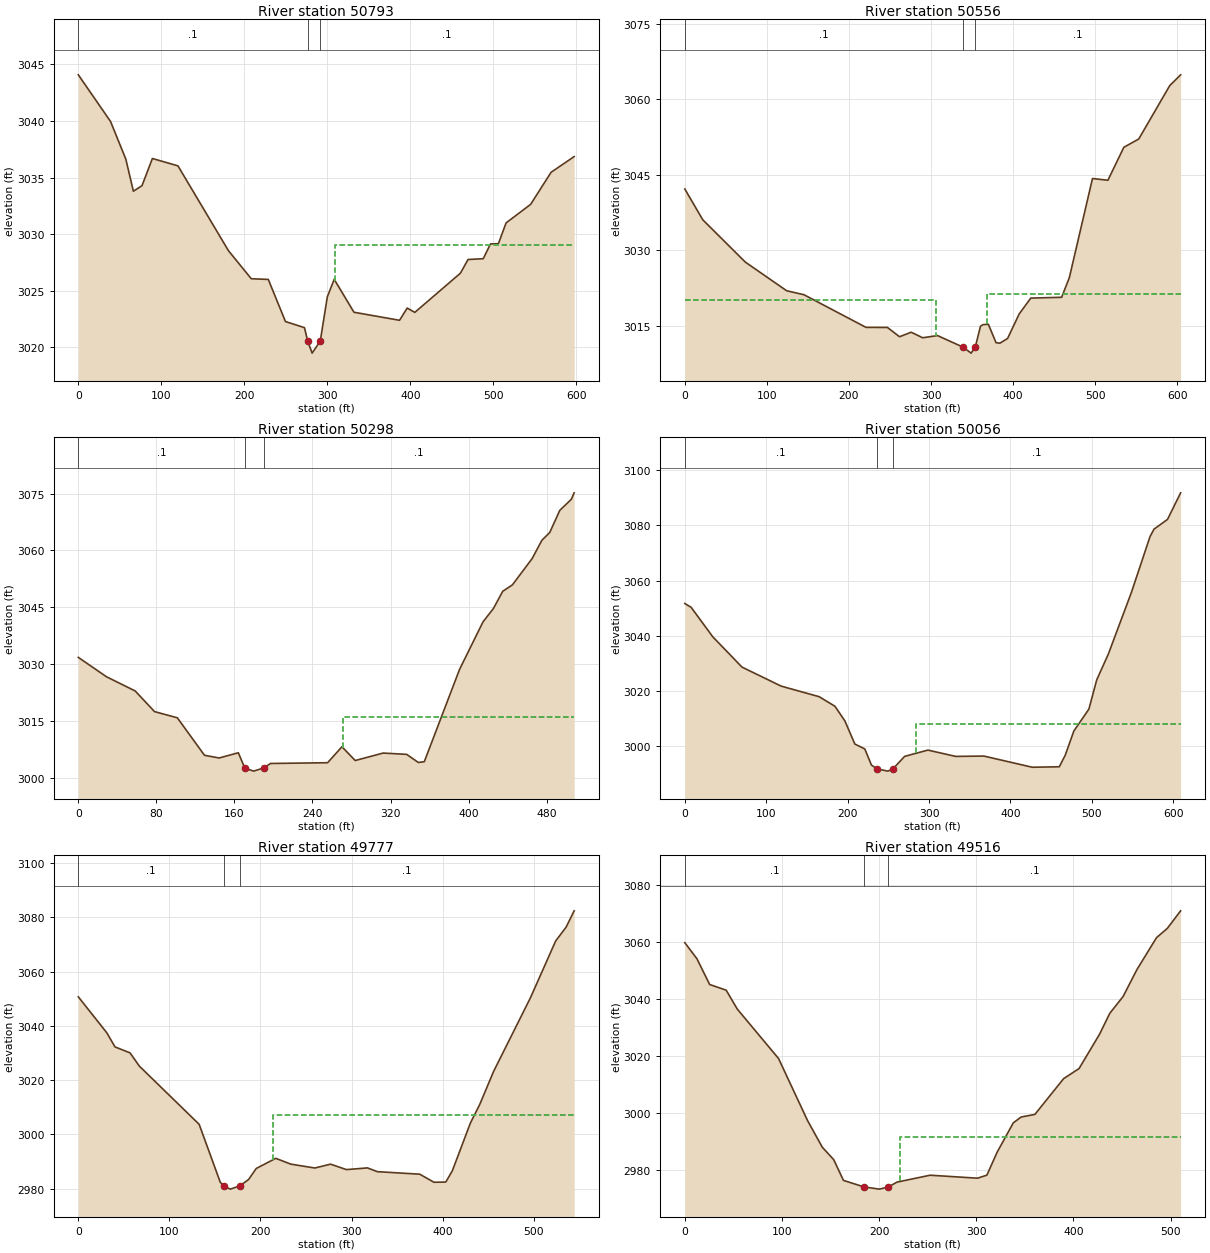
Type RM Length L Ch R = 1 ,50793   ,236.7,236.8,235.9
XS GIS Cut Line= 2
2204078.25849386596958.5526609312204599.80164866596667.641791148
#Sta/Elev= 30
       0 3044.07    38.8 3039.95    57.2 3036.63    66.3 3033.79    76.7 3034.28
    89.2 3036.68     120 3036.03   180.8 3028.54   208.3 3026.06   228.8    3026
   249.5 3022.28   272.4 3021.74  276.23 3020.56   281.6 3019.49   291.4 3020.55
   299.9 3024.46   308.2 3026.01     332  3023.1   386.9 3022.39   396.1 3023.47
   405.3 3023.09   460.2 3026.55   469.4 3027.76   487.7 3027.83   496.4 3029.13
     506 3029.16   515.2 3030.99   544.8 3032.63   569.4 3035.46   597.2 3036.85
#Mann= 3 ,0,0
       0      .1       0  276.23    .045       0   291.4      .1       0
#XS Ineff= 2 , 0
                          309.67         3029.06
Permanent Ineff=
       F       F
Bank Sta=276.23,291.4
XS Rating Curve= 0 ,0
Exp/Cntr=0.3,0.1

Type RM Length L Ch R = 1 ,50556   ,262.1,258.5,252.6
XS GIS Cut Line= 2
2204169.51879487597186.3977931352204683.48916872596868.837526435
#Sta/Elev= 30
       0 3042.19    21.9 3036.08    73.7 3027.69   124.1    3022   145.2 3021.21
   220.8 3014.73   246.9 3014.72   261.7 3012.87   275.8 3013.77   289.9 3012.67
     308  3013.1  339.08 3010.81   348.9 3009.62  353.99 3010.82   360.3 3014.94
   363.2 3015.27   369.9 3015.35   379.3 3011.69     384 3011.59   393.4 3012.54
   407.5  3017.4   421.6 3020.54   459.2  3020.7   468.6  3024.6   496.8 3044.27
   515.6 3043.92     535 3050.46   553.2 3052.11   590.9 3062.69   604.2 3064.84
#Mann= 3 ,0,0
       0      .1       0  339.08    .045       0  353.99      .1       0
#XS Ineff= 2 , 0
          306.27 3020.14     368         3021.37
Permanent Ineff=
       F       F
Bank Sta=339.08,353.99
XS Rating Curve= 0 ,0
Exp/Cntr(USF)=0,0
Exp/Cntr=0.3,0.1

Type RM Length L Ch R = 1 ,50298   ,244.5,241.3,235.3
XS GIS Cut Line= 3
2204396.82803517597384.0742395522204541.82943661 597193.67430284
2204742.90473952597015.176852069
#Sta/Elev= 30
       0 3031.76    28.8 3026.65    58.3 3022.89    78.1 3017.44   101.5  3015.8
   129.3 3005.91   144.3 3005.19     164 3006.57   170.6 3002.55   179.6 3001.72
  190.16 3002.57     197 3003.74   255.5 3003.94   270.2 3008.16   283.8 3004.52
   312.4 3006.49   336.5 3006.15   348.5 3004.01   354.6 3004.21   390.7 3028.56
   414.8 3041.15   425.5 3044.69     435 3049.22   444.9 3050.91   465.2 3057.88
   475.1 3062.68   483.2 3064.76   493.5  3070.6   505.2 3073.49   508.2 3075.22
#Mann= 3 ,0,0
       0      .1       0   170.6    .045       0  190.16      .1       0
#XS Ineff= 2 , 0
                          271.68         3016.08
Permanent Ineff=
       F       F
Bank Sta=170.6,190.16
XS Rating Curve= 0 ,0
Exp/Cntr=0.3,0.1

Type RM Length L Ch R = 1 ,50056   ,273.5,279.3,284.9
XS GIS Cut Line= 4
2204613.73604656597568.2043565662204690.83160264597404.835202021
2204716.53012133597276.3426085592204922.11827087597061.576416629
#Sta/Elev= 30
       0 3051.67     7.8 3050.28    34.3 3039.62    70.2 3028.61   118.3 3021.71
     165 3017.87   184.4  3014.4   196.6 3009.11   208.9 3000.69   221.1 2998.91
   229.2  2993.1   235.9 2991.68   249.5 2990.87  255.75 2991.71     270 2996.22
   298.6  2998.5   332.7 2996.21   367.4 2996.33   426.8 2992.28     460 2992.45
   467.4 2996.74   477.8 3005.38   496.3 3013.35     506 3024.01   520.2 3033.31
   548.5 3055.66   571.5    3076   576.3 3078.63   592.9 3082.17     609 3091.81
#Mann= 3 ,0,0
       0      .1       0   235.9    .045       0  255.75      .1       0
#XS Ineff= 2 , 0
                          284.34         3007.86
Permanent Ineff=
       F       F
Bank Sta=235.9,255.75
XS Rating Curve= 0 ,0
Exp/Cntr(USF)=0,0
Exp/Cntr=0.3,0.1

Type RM Length L Ch R = 1 ,49777   ,261.3,260.7,261.3
XS GIS Cut Line= 3
2204780.24723933597641.5319826332205007.84576803597404.599099795
2205147.07726936597239.450296732
#Sta/Elev= 30
       0 3050.72    31.3 3037.45    40.3 3032.25    56.8 3030.05      67 3025.17
   132.7  3003.7   155.8 2982.41   159.6 2980.94   166.9  2979.8  177.19 2980.97
   186.9 2983.32   195.4 2987.42   216.8 2991.16   233.4 2989.01   259.7 2987.59
     277 2989.01   294.4    2987   317.5 2987.63   328.4 2986.24   374.9 2985.31
   390.6 2982.33   403.5  2982.4   410.7 2986.55   430.6 3004.21   440.8 3011.02
   456.1 3023.26   496.6 3050.44   524.2 3071.33   535.6 3076.39   544.5 3082.44
#Mann= 3 ,0,0
       0      .1       0   159.6    .045       0  177.19      .1       0
#XS Ineff= 2 , 0
                          214.21         3007.28
Permanent Ineff=
       F       F
Bank Sta=159.6,177.19
XS Rating Curve= 0 ,0
Exp/Cntr=0.3,0.1

Type RM Length L Ch R = 1 ,49516   ,244.9,243.6,241
XS GIS Cut Line= 2
2204988.04657921597809.1500016462205320.29171373597421.836612781
#Sta/Elev= 30
       0 3059.85    12.5 3054.18    25.6 3045.12    42.6 3043.12      54 3036.48
    96.5 3019.07   126.4 2997.19   141.5 2987.86   153.3 2983.45   163.3 2976.17
   184.5 2973.87   200.2  2973.1   209.1  2973.8   218.5 2975.57   252.5    2978
   301.2 2976.95   310.9 2978.01   321.4 2986.06   338.1 2996.43   346.1 2998.47
   360.3 2999.39   389.9 3011.99   405.8 3015.55   426.8 3027.58   437.4 3034.98
   451.1  3040.9   465.3 3050.35   485.5 3061.61   496.5 3064.83   510.3 3071.05
#Mann= 3 ,0,0
       0      .1       0   184.5    .045       0   209.1      .1       0
#XS Ineff= 2 , 0
                          221.86         2991.35
Permanent Ineff=
       F       F
Bank Sta=184.5,209.1
XS Rating Curve= 0 ,0
Exp/Cntr(USF)=0,0
Exp/Cntr=0.3,0.1

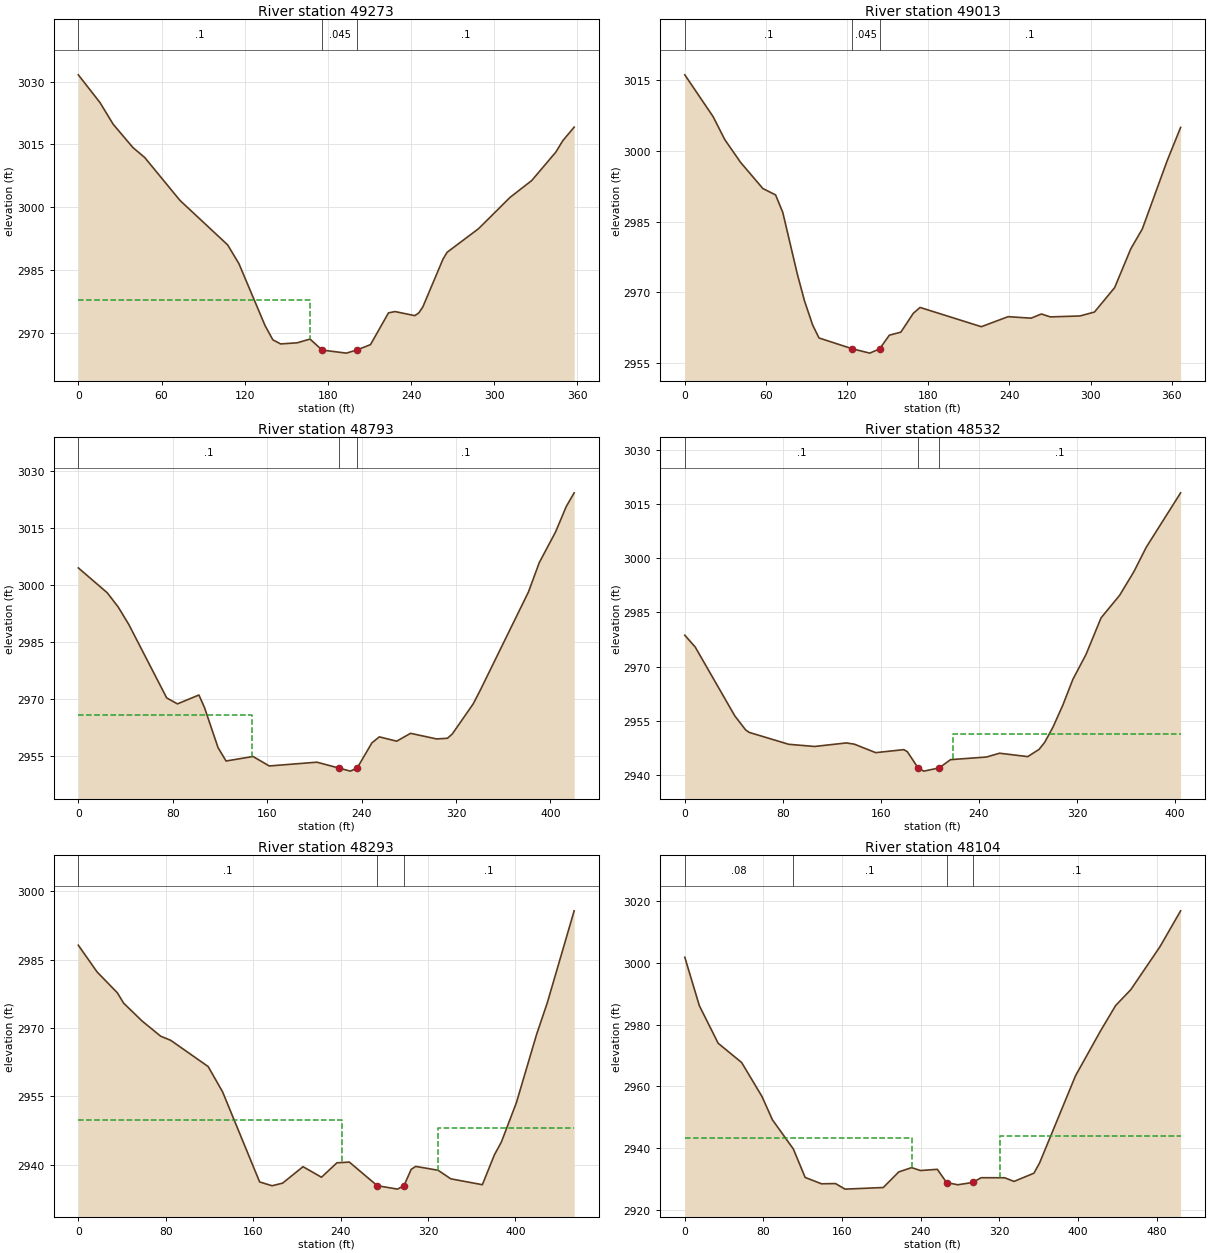
Type RM Length L Ch R = 1 ,49273   ,255.8,259.9,263.7
XS GIS Cut Line= 3
 2205183.2967016597940.0004552172205291.85278304597835.064386517
2205400.48616682597659.264846836
#Sta/Elev= 30
       0 3031.59    15.6 3024.99    25.2 3019.79    39.4 3014.26    47.9 3011.89
    73.3 3001.68   107.7 2991.08   115.8 2986.63   134.7 2971.84   140.3 2968.47
   145.9 2967.49   157.9 2967.76   167.1 2968.65   175.8 2966.03   193.3  2965.3
  200.88 2966.05   210.7 2967.32   223.7 2974.89   228.4  2975.2   242.7 2974.23
   245.6  2974.9   248.5 2976.33     263 2987.69     266 2989.33   288.6 2994.93
   311.4 3002.41     327 3006.41   344.4 3013.19   349.4  3015.9   357.6 3019.13
#Mann= 3 ,0,0
       0      .1       0   175.8    .045       0  200.88      .1       0
#XS Ineff= 2 , 0
          166.87 2977.89
Permanent Ineff=
       F       F
Bank Sta=175.8,200.88
XS Rating Curve= 0 ,0
Exp/Cntr=0.3,0.1

Type RM Length L Ch R = 1 ,49013   ,223.2,219.6,215
XS GIS Cut Line= 2
2205362.10900396598092.5786772562205635.68809152597848.736447033
#Sta/Elev= 30
       0 3016.17    20.9 3007.31    29.6  3002.4    41.2  2997.6    57.7 2992.03
    67.1 2990.68    72.4 2986.99    83.3 2973.73    88.5 2968.17    94.5 2963.06
    99.2 2960.31  123.81 2958.01   136.7 2957.09     144 2957.99   151.2  2960.9
   159.7 2961.54   168.9 2965.54   173.9 2966.79   219.2  2962.7     239 2964.83
     256 2964.51   263.6  2965.4   270.2 2964.78   292.1 2964.98   302.8 2965.81
   317.7 2970.98   329.7 2979.25   338.2 2983.46   356.4 2997.82   366.5 3005.01
#Mann= 3 ,0,0
       0      .1       0  123.81    .045       0     144      .1       0
Bank Sta=123.81,144
XS Rating Curve= 0 ,0
Exp/Cntr(USF)=0,0
Exp/Cntr=0.3,0.1

Type RM Length L Ch R = 1 ,48793   ,261.1,261.4,260.6
XS GIS Cut Line= 2
2205550.67538175598270.6275699162205754.81561966597903.330141714
#Sta/Elev= 30
       0 3004.54    24.5 2997.98    33.7 2994.27    42.8  2989.6    74.9 2970.24
      84 2968.67   102.2 2971.01   106.9 2967.72   118.4 2957.14   125.2  2953.6
   148.1 2954.79   161.8 2952.29   202.2 2953.29   221.3  2951.7   230.5 2950.93
  236.26 2951.72   248.8 2958.39   255.1 2959.97   269.8 2958.83   281.6  2960.9
   303.7 2959.42   312.8  2959.6   316.9 2960.72   334.6 2968.65   340.7 2972.31
   381.5 2998.21   390.6 3005.91   404.4 3013.99   413.5 3020.73   420.2 3024.34
#Mann= 3 ,0,0
       0      .1       0   221.3    .045       0  236.26      .1       0
#XS Ineff= 2 , 0
          147.54 2965.68
Permanent Ineff=
       F       F
Bank Sta=221.3,236.26
XS Rating Curve= 0 ,0
Exp/Cntr=0.3,0.1

Type RM Length L Ch R = 1 ,48532   ,234.1,238.6,242.4
XS GIS Cut Line= 2
2205747.91994158598424.5503832422205947.54792546598072.792234982
#Sta/Elev= 30
       0 2978.69     8.5 2975.42    40.8 2956.35    49.6 2952.48    52.5 2951.78
    84.8 2948.48   105.9 2947.88   131.8 2948.86   138.3 2948.52   155.7 2946.17
   178.7    2947   181.6 2946.41   190.4 2941.89     195 2941.05  207.45 2941.93
   216.8 2944.23   246.2 2944.96   256.8 2946.01   279.8 2945.07     289 2947.07
   293.6 2949.03   300.4 2953.26   308.5 2959.41   316.6 2966.47   327.3 2973.35
   339.6 2983.49   354.8 2989.77   366.5 2996.36   376.4 3003.02   404.5 3018.12
#Mann= 3 ,0,0
       0      .1       0   190.4    .045       0  207.45      .1       0
#XS Ineff= 2 , 0
                          218.58          2951.4
Permanent Ineff=
       F       F
Bank Sta=190.4,207.45
XS Rating Curve= 0 ,0
Exp/Cntr(USF)=0,0
Exp/Cntr=0.3,0.1

Type RM Length L Ch R = 1 ,48293   ,193.5,189.3,187.4
XS GIS Cut Line= 3
 2205853.3425244598536.7037606722205991.06185664 598412.58795284
2206184.95052252598227.118049042
#Sta/Elev= 30
       0 2988.14    17.2 2982.27    35.7 2977.71    41.5 2975.43    58.3 2971.53
    75.3  2968.2    84.6 2967.28   118.8 2961.54     132 2955.99   165.9 2936.24
   177.3  2935.4   186.9 2935.97   205.6 2939.58   222.5 2937.27   236.6 2940.43
     248 2940.59   273.5 2935.42   292.1 2934.66  297.97 2935.43   304.6    2939
   308.7 2939.64   329.2  2938.8   340.8 2936.92   369.7 2935.63   380.7 2942.17
   387.1 2944.99   400.8 2953.58   419.4 2968.64   429.1  2975.5   453.7 2995.68
#Mann= 3 ,0,0
       0      .1       0   273.5    .045       0  297.97      .1       0
#XS Ineff= 2 , 0
          241.38 2949.87  329.56         2948.12
Permanent Ineff=
       F       F
Bank Sta=273.5,297.97
XS Rating Curve= 0 ,0
Exp/Cntr=0.3,0.1

Type RM Length L Ch R = 1 ,48104   ,323,329.6,329.2
XS GIS Cut Line= 3
2206029.27655167598721.6073474142206242.80651636598394.266995455
2206313.26056562598305.386502539
#Sta/Elev= 30
       0 3001.82    14.8 2986.11    33.9 2973.95    57.8  2967.7    78.5 2956.68
    89.1 2949.14   110.4 2939.66   122.4 2930.45     139 2928.39   153.3 2928.46
   162.9 2926.66   201.8 2927.18   217.6 2932.24   230.7 2933.63   239.6 2932.69
   256.8 2933.08   266.2  2928.8   277.5 2928.07  292.67 2928.82   301.4 2930.36
   325.3 2930.34   334.8 2929.16     355 2931.82   360.8 2935.16   397.3 2963.39
   422.8 2977.97   438.1 2986.16   453.5 2991.29   483.2 3005.24   504.2 3016.86
#Mann= 4 ,-1,0
       0     .08       0     110      .1       0   266.2    .045       0
  292.67      .1       0
#XS Ineff= 2 , 0
          231.42 2943.32  320.16         2943.95
Permanent Ineff=
       F       F
Bank Sta=266.2,292.67
XS Rating Curve= 0 ,0
Exp/Cntr(USF)=0,0
Exp/Cntr=0.3,0.1

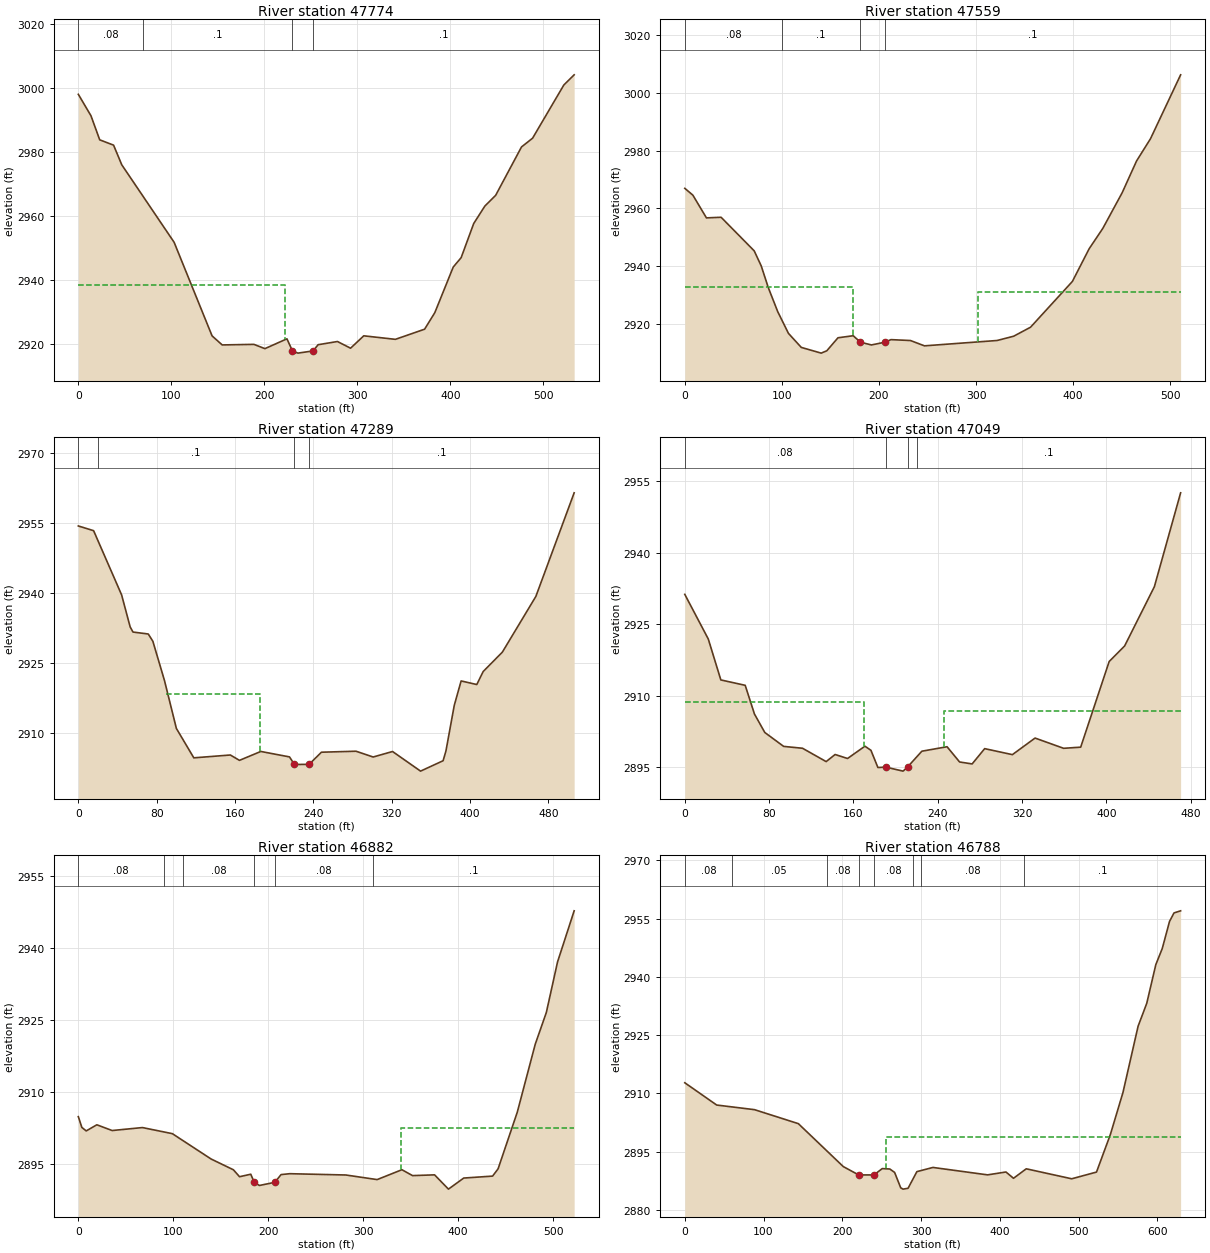
Type RM Length L Ch R = 1 ,47774   ,216,214.9,212.7
XS GIS Cut Line= 3
2206204.60558846598895.2040150142206482.64198499 598591.92427436
2206567.26923697598504.560815425
#Sta/Elev= 30
       0 2998.09    13.6 2991.38      23 2983.86    37.9  2982.2    46.7 2976.06
     103 2951.83   143.8 2922.58   154.7 2919.75   188.8 2919.93   200.6 2918.59
   224.3 2921.66   230.2 2917.89   236.1 2917.19   252.4 2917.88   257.8 2919.82
   278.6 2920.82   292.7 2918.73   306.9  2922.6   340.9  2921.5   372.3 2924.67
   383.3 2929.85   403.1  2944.1   411.6 2947.03   425.1  2957.7   437.1 2963.16
   448.7 2966.51   476.5 2981.64   488.4 2984.37     522    3001   533.1 3004.18
#Mann= 4 ,-1,0
       0     .08       0      70      .1       0   230.2    .045       0
   252.4      .1       0
#XS Ineff= 2 , 0
          221.82 2938.59
Permanent Ineff=
       F       F
Bank Sta=230.2,252.4
XS Rating Curve= 0 ,0
Exp/Cntr=0.3,0.1

Type RM Length L Ch R = 1 ,47559   ,270.9,270.7,269.6
XS GIS Cut Line= 2
2206423.47700667599011.9597588732206713.72360277598591.644148741
#Sta/Elev= 30
       0 2966.94     8.3 2964.59    22.3 2956.72    37.4 2956.93    71.5 2945.31
    78.7 2940.14      86 2932.61    95.7  2924.3   106.8 2916.75     120  2911.9
   140.5 2909.92   146.3 2910.73   157.8 2915.23   173.5 2915.94     181 2913.69
   192.3 2912.75  205.91 2913.69   212.4 2914.59   232.5 2914.28   246.9 2912.44
   321.7 2914.29   338.8 2915.77   356.2 2918.89   399.3 2934.73   416.6 2946.05
   430.6 2953.06   450.6 2965.43   465.4 2976.41   479.8 2984.13   510.8 3006.22
#Mann= 4 ,-1,0
       0     .08       0     100      .1       0     181    .045       0
  205.91      .1       0
#XS Ineff= 2 , 0
          172.98 2932.86  302.54         2931.21
Permanent Ineff=
       F       F
Bank Sta=181,205.91
XS Rating Curve= 0 ,0
Exp/Cntr(USF)=0,0
Exp/Cntr=0.3,0.1

Type RM Length L Ch R = 1 ,47289   ,236.2,239.5,241.2
XS GIS Cut Line= 3
 2206637.0630439599190.6017553942206779.94012717598949.928005005
 2206911.0015761598765.397546069
#Sta/Elev= 30
       0 2954.32    15.6 2953.31    44.2 2939.53    52.9 2932.67    55.8 2931.56
    71.4 2931.14    76.1 2929.58      88 2921.12   100.1 2910.88   117.9 2904.57
   155.2 2905.18   164.5 2904.03   186.3 2905.94   215.6 2904.77  220.58 2903.15
   235.6 2903.17   248.2 2905.78   283.5 2905.99     301 2904.75   320.8 2905.93
   349.4 2901.72   372.4 2903.95   375.3 2906.04   383.8 2915.83   390.8 2921.07
   406.8  2920.3   413.3 2923.08   432.9 2927.25   467.1  2939.2   506.2 2961.43
#Mann= 4 ,-1,0
       0     .08       0      20      .1       0  220.58    .045       0
   235.6      .1       0
#XS Ineff= 1 ,-1
   89.62  185.79 2918.28
Permanent Ineff=
       F
Bank Sta=220.58,235.6
XS Rating Curve= 0 ,0
Exp/Cntr=0.3,0.1

Type RM Length L Ch R = 1 ,47049   ,164.9,167.2,170
XS GIS Cut Line= 2
2206777.73182109599284.1340552712207126.49743191598968.409397049
#Sta/Elev= 30
       0 2931.25    22.3 2921.87    34.2 2913.29    57.3 2912.16    66.1 2906.13
    75.9 2902.26    93.8 2899.34   111.7 2898.95   134.1 2896.15   142.6 2897.64
   154.4  2896.8   170.9 2899.38   176.6 2898.52   183.2 2894.91   190.7 2894.99
   207.1 2894.15  211.32 2895.01   224.9 2898.33   248.8 2899.27   260.7 2896.07
   272.6 2895.66   284.5 2898.87   310.8 2897.61   332.3 2901.09   359.4 2898.94
   375.6 2899.18   402.6 2917.15   417.3 2920.43   445.5 2932.86   470.4 2952.56
#Mann= 4 ,-1,0
       0     .08       0   190.7    .045       0  211.32     .08       0
     220      .1       0
#XS Ineff= 2 , 0
          170.15 2908.64  246.18          2906.8
Permanent Ineff=
       F       F
Bank Sta=190.7,211.32
XS Rating Curve= 0 ,0
Exp/Cntr(USF)=0,0
Exp/Cntr=0.3,0.1

Type RM Length L Ch R = 1 ,46882   ,94.4,93.9,93.6
XS GIS Cut Line= 3
2206860.93129374 599372.383468512207140.69406798599219.137617652
2207247.60977788599046.290553311
#Sta/Elev= 30
       0  2904.8     3.7 2902.56     8.3 2901.82    19.5  2903.1    35.6  2901.9
    67.5 2902.52      99 2901.25   139.9 2895.95   163.3 2893.71   169.8 2892.26
   181.6 2892.78   185.32891.085   190.7 2890.43  206.93 2891.09   213.5  2892.7
   222.6 2892.89   281.7 2892.62   314.7 2891.66   340.8 2893.72     352 2892.49
   375.2 2892.65   389.8 2889.67   405.9 2891.98   436.3 2892.39   442.1 2893.91
   462.3 2905.73   481.2 2919.91   492.9 2926.54   504.7 2937.09   522.2 2947.76
#Mann= 6 ,-1,0
       0     .08       0      90     .05       0     110     .08       0
   185.3    .045       0  206.93     .08       0     310      .1       0
#XS Ineff= 2 , 0
                          340.19         2902.51
Permanent Ineff=
       F       F
Bank Sta=185.3,206.93
XS Rating Curve= 0 ,0
Exp/Cntr(USF)=0,0
Exp/Cntr=0.3,0.1

Type RM Length L Ch R = 1 ,46788   ,152.4,152,151.2
XS GIS Cut Line= 3
2206887.85958103599472.3009181562207164.72696564599309.384150569
2207334.66695089599052.069382981
#Sta/Elev= 30
       0 2912.73    40.5    2907    88.5 2905.81   144.2 2902.21   201.2 2891.17
  220.72 2889.02   240.2 2889.01   250.7 2890.64   260.3 2890.54   266.4 2889.67
   274.2 2885.69   277.2 2885.36   283.5 2885.58   294.7 2889.86   315.1 2890.94
   384.5 2889.03   407.8 2889.77   417.4 2888.15   433.6 2890.59   491.3 2888.02
   522.8 2889.75   540.4 2899.42   556.4 2910.24   575.6 2927.28   586.6 2933.18
   598.1 2943.13   606.3 2947.29   615.5 2954.25   621.2 2956.44   629.6 2956.98
#Mann= 8 ,-1,0
       0     .08       0      60     .05       0     180     .08       0
  220.72    .045       0   240.2     .08       0     290      .1       0
     300     .08       0  431.24      .1       0
#XS Ineff= 2 , 0
                          255.01         2898.79
Permanent Ineff=
       F       F
Bank Sta=220.72,240.2
XS Rating Curve= 0 ,0
Exp/Cntr=0.3,0.1

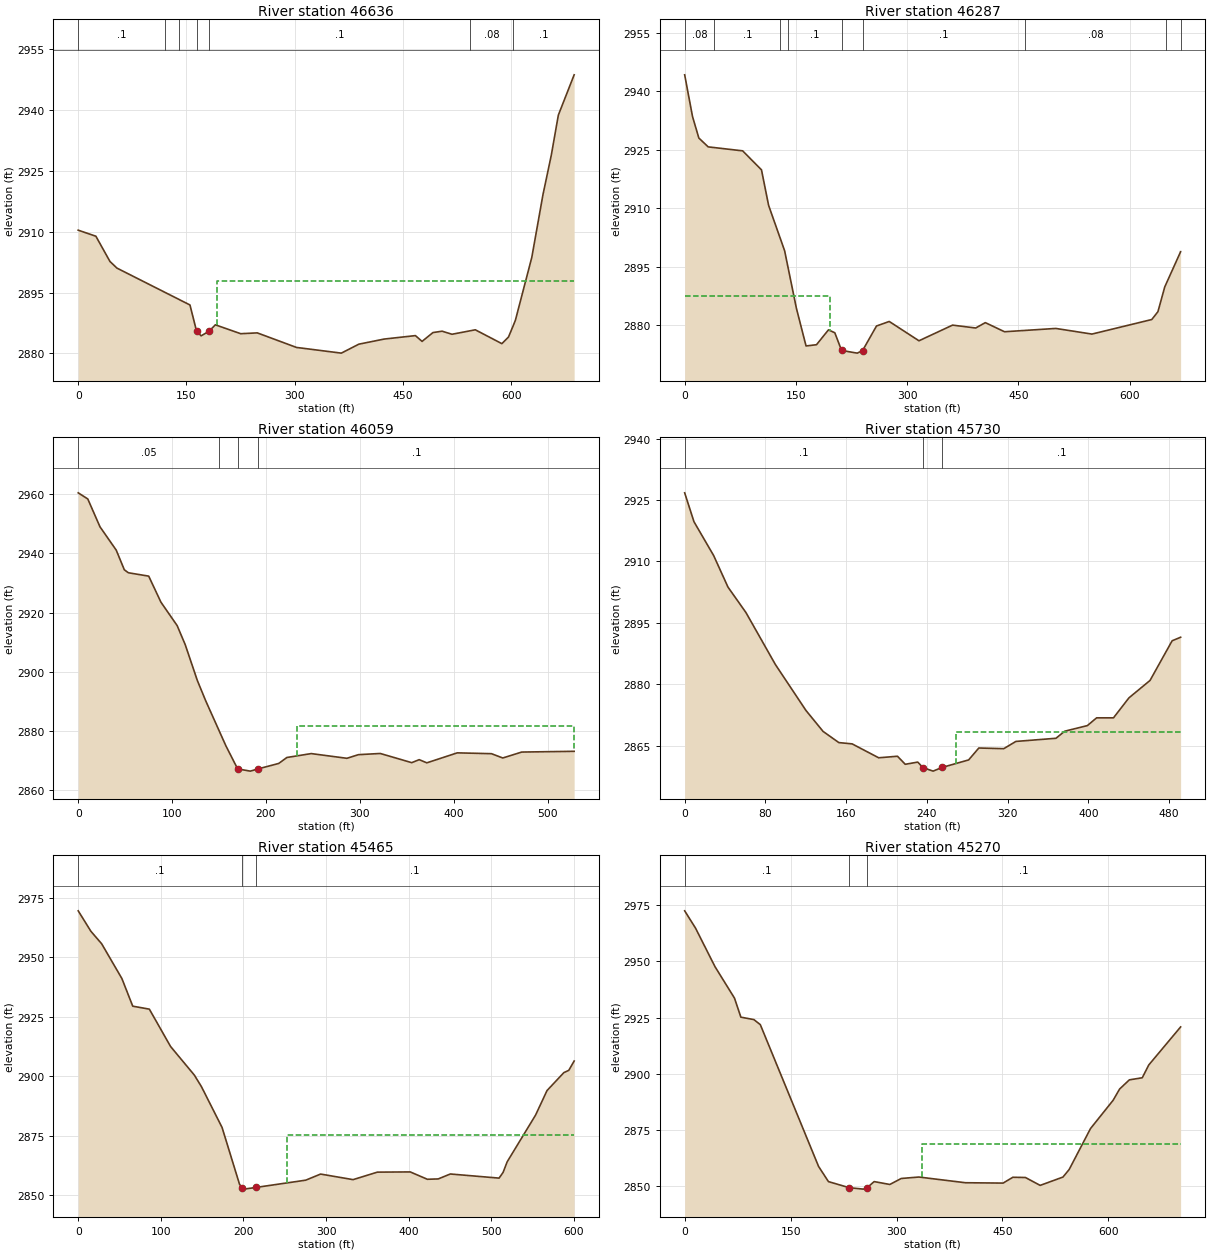
Type RM Length L Ch R = 1 ,46636   ,346.5,349.4,340.2
XS GIS Cut Line= 3
2207020.00858195599585.2499012982207310.38899392599384.526114225
 2207476.3206579599094.145702259
#Sta/Elev= 30
       0 2910.38    24.5 2908.89      44 2902.67    53.7 2901.03   154.9 2891.94
   164.1 2885.45   170.4 2884.33  181.58  2885.5   190.1 2887.05   225.2 2884.86
   248.2 2885.06   302.6 2881.47   364.7 2880.07     389 2882.28   424.2 2883.54
   467.4 2884.39   476.6 2882.96   491.6 2885.13   504.3 2885.48   518.1 2884.72
   550.4 2885.82   587.2 2882.41   596.4 2884.04     603 2886.86     606 2888.19
   628.7 2903.67   644.1 2919.07   655.8 2928.94   665.5 2938.75   687.4 2948.68
#Mann= 7 ,-1,0
       0      .1       0     120     .08       0     140      .1       0
   164.1    .045       0  181.58      .1       0     543     .08       0
     603      .1       0
#XS Ineff= 2 , 0
                          192.53         2897.73
Permanent Ineff=
       F       T
Bank Sta=164.1,181.58
XS Rating Curve= 0 ,0
Exp/Cntr(USF)=0,0
Exp/Cntr=0.3,0.1

Type RM Length L Ch R = 1 ,46287   ,224.2,227.3,226.6
XS GIS Cut Line= 3
2207390.63685893599747.228507999 2207428.9399045599634.474000706
2207636.04128578599125.157381042
#Sta/Elev= 30
       0 2944.24    10.6 2933.51    19.1 2928.01    31.7 2925.74    78.2 2924.72
   103.6 2919.84   113.2 2910.72   134.8 2899.07   150.7 2884.29   163.7 2874.62
   177.8 2874.94   193.9 2878.75   202.5 2878.01   211.6 2873.47   232.7 2872.78
   239.9 2873.42   258.7 2879.74   275.9 2880.91     316 2875.95   361.3 2879.97
   392.5 2879.23   405.5 2880.61   431.4 2878.27   500.5 2879.12   549.3 2877.67
     630 2881.41   638.3 2883.42   647.5 2889.78   668.9 2898.82   668.9 2898.83
#Mann= 9 ,-1,0
       0     .08       0      40      .1       0  129.08     .05       0
  139.08      .1       0   211.6    .045       0   239.9      .1       0
  459.08     .08       0  649.08     .05       0   668.9     .08       0
#XS Ineff= 2 , 0
          196.36 2887.52
Permanent Ineff=
       F       F
Bank Sta=211.6,239.9
XS Rating Curve= 0 ,0
Exp/Cntr=0.3,0.1

Type RM Length L Ch R = 1 ,46059   ,319.8,329.4,325.6
XS GIS Cut Line= 3
2207571.83084182599846.5954918112207700.69055698599534.358489697
 2207728.7753667 599346.02505985
#Sta/Elev= 30
       0 2960.46    10.2 2958.39    23.2 2948.98    40.5 2941.11    49.1 2934.48
    53.4 2933.47    75.1 2932.33    88.1 2923.54   105.4 2915.62     114 2909.17
   126.9 2897.08   135.7  2890.3   157.3 2875.03   169.8 2867.24   183.3 2866.49
   191.9 2867.27   213.6 2869.09   222.2 2871.09   248.2 2872.41   286.2 2870.82
   298.5 2872.05   321.7 2872.45   355.2 2869.35   363.2 2870.36   371.3 2869.29
   403.7 2872.66   440.1 2872.38   452.2 2870.93   472.4 2872.93   528.2 2873.18
#Mann= 4 ,-1,0
       0     .05       0     150      .1       0   169.8    .045       0
   191.9      .1       0
#XS Ineff= 2 , 0
                          232.79         2881.85
Permanent Ineff=
       F       F
Bank Sta=169.8,191.9
XS Rating Curve= 0 ,0
Exp/Cntr(USF)=0,0
Exp/Cntr=0.3,0.1

Type RM Length L Ch R = 1 ,45730   ,255.9,264.9,262.2
XS GIS Cut Line= 3
 2207783.2626285599884.4638211872207968.97146631599642.202559746
2208092.26289714599502.843874682
#Sta/Elev= 30
       0 2926.78     9.2 2919.72    28.7 2911.45    42.9 2903.73    60.7 2897.51
    89.8 2884.83   120.1 2873.59   137.1 2868.45   152.7 2865.72   165.9  2865.4
   192.2    2862   210.8 2862.38   218.5 2860.41   230.9 2860.95     236  2859.6
   246.1 2858.74  254.86 2859.63   281.3 2861.48   291.4 2864.39   316.1 2864.23
   328.1    2866   367.8 2866.77   376.5  2868.5   398.9 2869.87   408.1 2871.77
   424.8 2871.77   440.1 2876.65     461 2880.91   482.9 2890.61   491.3 2891.47
#Mann= 3 ,0,0
       0      .1       0     236    .045       0  254.86      .1       0
#XS Ineff= 2 , 0
                          268.52         2868.22
Permanent Ineff=
       F       F
Bank Sta=236,254.86
XS Rating Curve= 0 ,0
Exp/Cntr=0.3,0.1

Type RM Length L Ch R = 1 ,45465   ,191.3,195,194.9
XS GIS Cut Line= 2
2207837.06810864600054.0947137332208326.23941195599706.173482806
#Sta/Elev= 30
       0 2969.47    15.4 2960.85    28.4 2955.62    52.9 2940.99      66  2929.4
    86.1 2928.15   111.8 2912.45   140.6 2900.42   149.2 2895.55   174.1 2878.45
   195.2 2854.62   197.9 2853.18   200.8 2852.51   215.1 2853.22   275.4 2856.27
   293.4 2858.84   332.7  2856.5   362.1 2859.65   401.9 2859.74   422.6 2856.65
   435.8  2856.8   450.4 2858.87   509.4 2857.14   514.3 2859.54   519.2 2863.97
   553.6 2883.62   567.5 2893.95   587.9 2901.49   593.8 2902.43   600.3 2906.35
#Mann= 3 ,-1,0
       0      .1       0   197.9    .045       0   215.1      .1       0
#XS Ineff= 2 , 0
                          252.46         2875.46
Permanent Ineff=
       F       F
Bank Sta=197.9,215.1
XS Rating Curve= 0 ,0
Exp/Cntr(USF)=0,0
Exp/Cntr=0.3,0.1

Type RM Length L Ch R = 1 ,45270   ,260.6,266.3,269.6
XS GIS Cut Line= 2
2207906.69859312600204.8053344242208519.53619052599861.808619193
#Sta/Elev= 30
       0 2972.59    15.4 2964.86    42.9 2947.71    70.5 2933.69    79.6 2925.17
      98 2924.09   107.1 2921.85   189.6 2858.63   203.6 2851.85     233 2849.14
   253.1  2848.5   258.4 2849.15   268.3 2851.86   290.5 2850.58   306.7 2853.25
   331.7 2853.89   397.6 2851.35   450.9 2851.19   464.7 2853.78   482.5 2853.69
   503.4 2850.17   535.7 2853.88   544.5 2857.26   574.7 2875.51   606.8 2888.15
   615.9 2893.13   629.7 2897.22     648 2898.16   657.2 2903.86   702.3 2920.82
#Mann= 3 ,0,0
       0      .1       0     233    .045       0   258.4      .1       0
#XS Ineff= 2 , 0
                          336.61         2868.44
Permanent Ineff=
       F       F
Bank Sta=233,258.4
XS Rating Curve= 0 ,0
Exp/Cntr=0.3,0.1

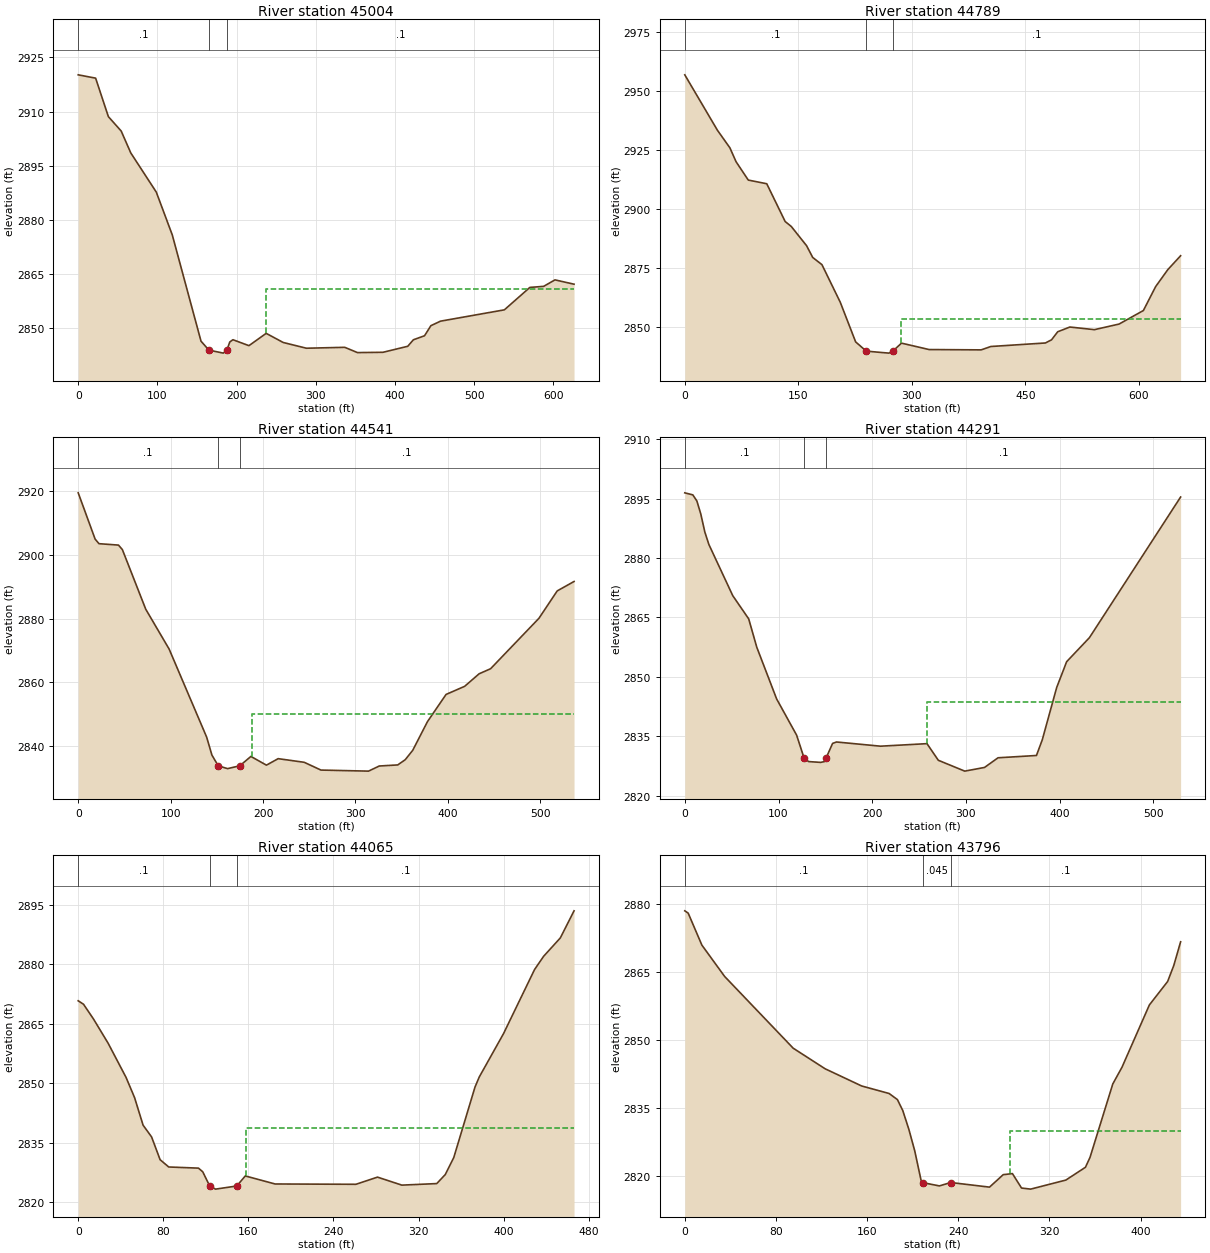
Type RM Length L Ch R = 1 ,45004   ,213.3,214.5,215.1
XS GIS Cut Line= 2
2208062.33254582600332.8845372952208683.50245478600253.586251044
#Sta/Elev= 30
       0 2920.19      22 2919.27    38.1  2908.6    54.3  2904.6    66.4 2898.54
    98.6 2887.68   118.8 2875.81   155.1 2846.34  165.082843.865   183.3 2843.03
  187.87 2843.92   191.4 2846.11   195.4 2846.75   215.6  2845.1   237.4 2848.51
   258.9 2845.98   288.2 2844.39   336.6 2844.64   352.7 2843.18   384.9 2843.26
   416.2 2844.93   423.3 2846.73   437.4 2847.85   445.4 2850.64   457.5 2851.89
   538.2 2855.03   570.4 2861.25   587.8 2861.54   602.1 2863.34   626.2 2862.14
#Mann= 3 ,0,0
       0      .1       0  165.08    .045       0  187.87      .1       0
#XS Ineff= 2 , 0
                          237.42         2860.73
Permanent Ineff=
       F       F
Bank Sta=165.08,187.87
XS Rating Curve= 0 ,0
Exp/Cntr(USF)=0,0
Exp/Cntr=0.3,0.1

Type RM Length L Ch R = 1 ,44789   ,241.2,248.4,255.3
XS GIS Cut Line= 3
2208053.39419193600548.0199047392208193.35576114600524.537523933
2208700.89152346600448.962476303
#Sta/Elev= 30
       0 2956.88    43.1 2933.37    59.6 2925.89    67.7 2920.02    83.9  2912.2
   108.3 2910.64   132.6 2894.61   140.7  2892.5   160.9 2884.34     169 2879.36
   181.2 2876.29   205.4 2860.34   225.7 2843.51  239.77 2839.58   269.6 2838.74
  274.68 2839.55   286.3 2842.98   322.7 2840.26   391.5 2840.12   404.3 2841.55
   476.4 2843.05   484.5 2844.39   492.6  2847.8   508.7 2849.82   541.1  2848.7
   573.7 2851.08   605.8 2856.82     622 2866.98   638.1 2874.19     655 2880.08
#Mann= 3 ,0,0
       0      .1       0  239.77    .045       0  274.68      .1       0
#XS Ineff= 2 , 0
                          286.09         2853.24
Permanent Ineff=
       F       F
Bank Sta=239.77,274.68
XS Rating Curve= 0 ,0
Exp/Cntr=0.3,0.1

Type RM Length L Ch R = 1 ,44541   ,249.3,249.7,250
XS GIS Cut Line= 3
2208118.80832596600693.4026531172208425.24664089600795.102705234
2208638.01385519600815.175083941
#Sta/Elev= 30
       0 2919.32    18.3 2904.85    22.5 2903.41    43.6 2902.97    47.8 2901.56
    73.1 2882.91    98.4 2870.45     139 2842.91   144.7 2837.29  151.49 2833.95
   161.6 2833.05   174.9 2833.94   186.9 2836.87   203.7 2834.14   216.4 2836.17
   244.6 2835.03   262.7  2832.6   314.2 2832.27   325.8 2833.87   345.8 2834.21
   353.9 2835.84     362 2838.77     378 2847.76   398.1 2856.26   418.2 2858.79
   433.9 2862.72   446.3  2864.3   498.6 2880.07   518.4 2888.64   536.6 2891.59
#Mann= 3 ,0,0
       0      .1       0  151.49    .045       0   174.9      .1       0
#XS Ineff= 2 , 0
                          188.24         2850.03
Permanent Ineff=
       F       F
Bank Sta=151.49,174.9
XS Rating Curve= 0 ,0
Exp/Cntr(USF)=0,0
Exp/Cntr=0.3,0.1

Type RM Length L Ch R = 1 ,44291   ,231.1,226.3,223.5
XS GIS Cut Line= 3
2208044.07041197600926.2014793432208262.49514915601005.921647352
2208556.88527807601040.664035487
#Sta/Elev= 30
       0 2896.46     8.6 2895.94    12.9  2894.4    17.1  2891.1    21.4 2886.55
    25.7 2883.42    51.2 2870.48    68.2 2864.62    76.8 2857.47      98 2844.39
   119.3 2835.26   127.2 2829.52   132.1 2828.57   144.9 2828.37     149 2828.56
  150.83 2829.51   157.7 2833.16   161.9 2833.52   208.8 2832.46   258.4  2833.1
   270.5  2828.9   298.7 2826.16   319.8 2827.09   334.2 2829.53   375.2 2830.11
   381.4 2834.07   396.8  2847.3   407.4  2853.8   431.7 2859.87     529  2895.4
#Mann= 3 ,0,0
       0      .1       0   127.2    .045       0  150.83      .1       0
#XS Ineff= 2 , 0
                          258.45         2843.72
Permanent Ineff=
       F       F
Bank Sta=127.2,150.83
XS Rating Curve= 0 ,0
Exp/Cntr=0.3,0.1

Type RM Length L Ch R = 1 ,44065   ,268.4,269.3,269.2
XS GIS Cut Line= 2
2208043.14210985601195.6576582292208509.22274344601205.292400009
#Sta/Elev= 30
       0 2870.83       5 2869.95    14.3 2866.26    28.1 2860.13      45 2851.48
      53 2846.38      61 2839.43      69 2836.46      77 2830.71    85.1 2828.87
   113.1 2828.58   117.1 2827.65  123.58  2824.1   129.1 2823.28   149.1 2824.07
   157.1 2826.61   185.1 2824.58   261.1  2824.5   281.4 2826.31   304.3 2824.29
   337.1 2824.68   345.1 2826.95   353.1 2831.24   373.1 2849.07   377.1  2851.6
   399.9 2862.54   429.1 2878.73   437.6 2882.06   453.3  2886.7   466.2 2893.54
#Mann= 3 ,0,0
       0      .1       0  123.58    .045       0   149.1      .1       0
#XS Ineff= 2 , 0
                          157.43         2838.79
Permanent Ineff=
       F       F
Bank Sta=123.58,149.1
XS Rating Curve= 0 ,0
Exp/Cntr(USF)=0,0
Exp/Cntr=0.3,0.1

Type RM Length L Ch R = 1 ,43796   ,222.4,220.9,221.4
XS GIS Cut Line= 2
2207941.18925643601451.1409814512208375.60640482601476.162944354
#Sta/Elev= 30
       0 2878.53       3 2878.02      15 2870.96      35 2864.03    95.1  2848.2
   123.2 2843.64   155.2 2839.85   179.3 2838.19   186.6 2836.84   191.3 2834.42
   196.6  2830.3   201.8 2825.51   207.3 2819.06   209.3 2818.48   223.4 2817.78
  233.43 2818.53   267.4 2817.51   279.4 2820.26   287.5  2820.5   295.5 2817.31
   303.5 2817.07   334.4 2819.07   351.6  2821.9   355.6 2824.09   375.6 2840.31
   383.6 2843.96   407.7 2857.75   423.7 2862.92   429.1 2866.46   435.1 2871.69
#Mann= 3 ,0,0
       0      .1       0   209.3    .045       0  233.43      .1       0
#XS Ineff= 2 , 0
                          285.19         2829.96
Permanent Ineff=
       F       F
Bank Sta=209.3,233.43
XS Rating Curve= 0 ,0
Exp/Cntr=0.3,0.1