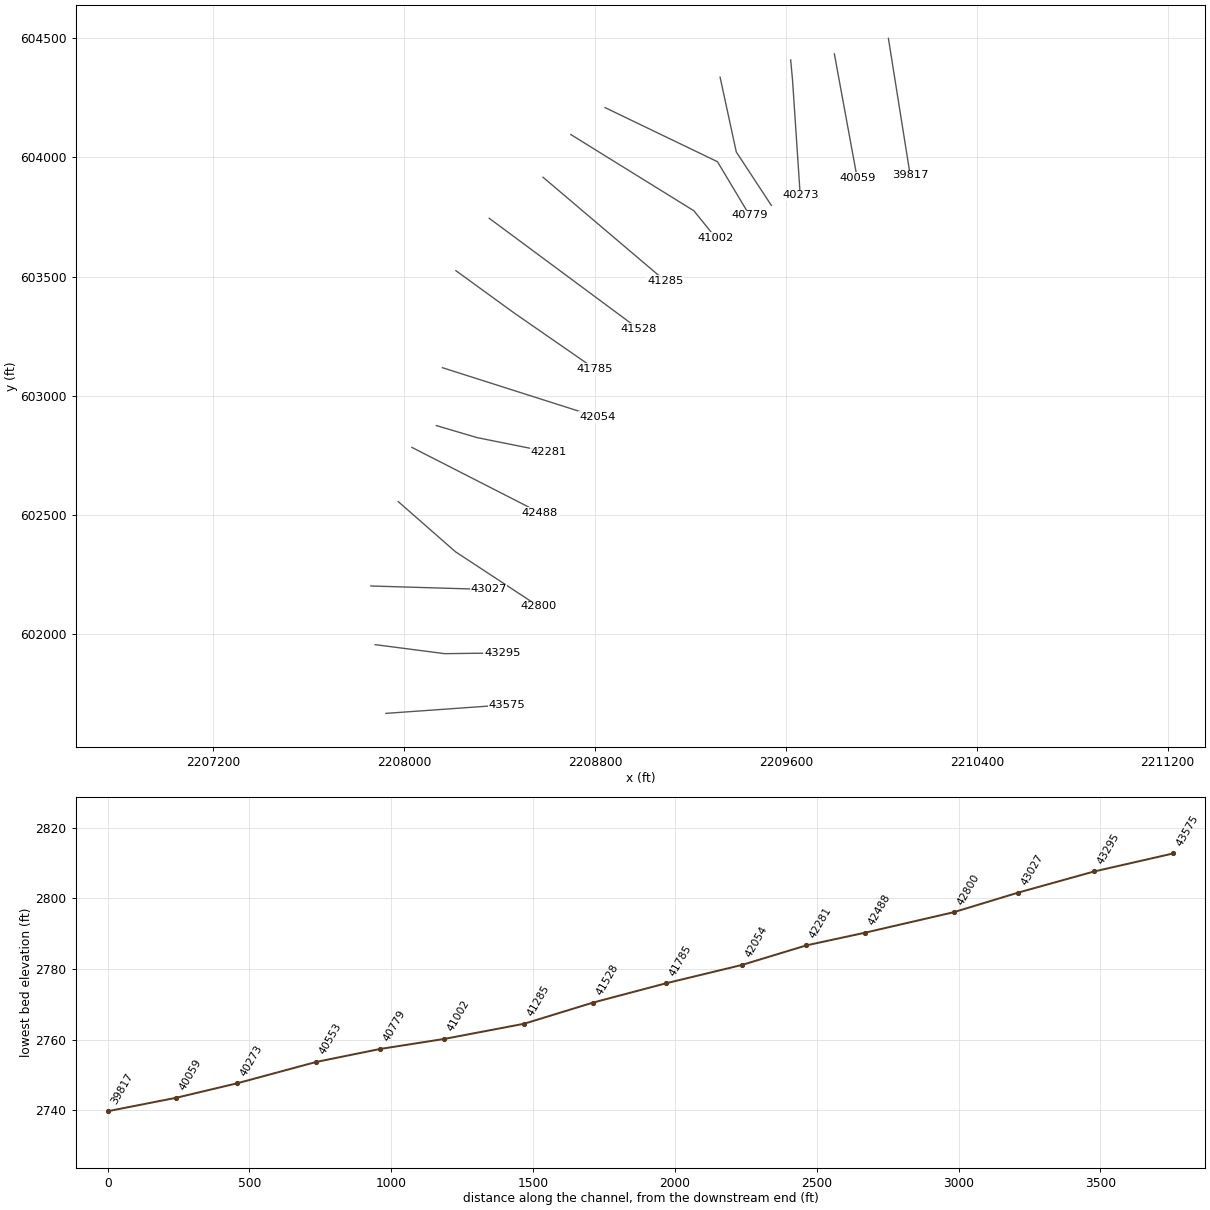
HEC-RAS study LFBUCKRV.prj: LFBUCKRV

--- LFBUCKRV.g01 (geometry) --- (continued)

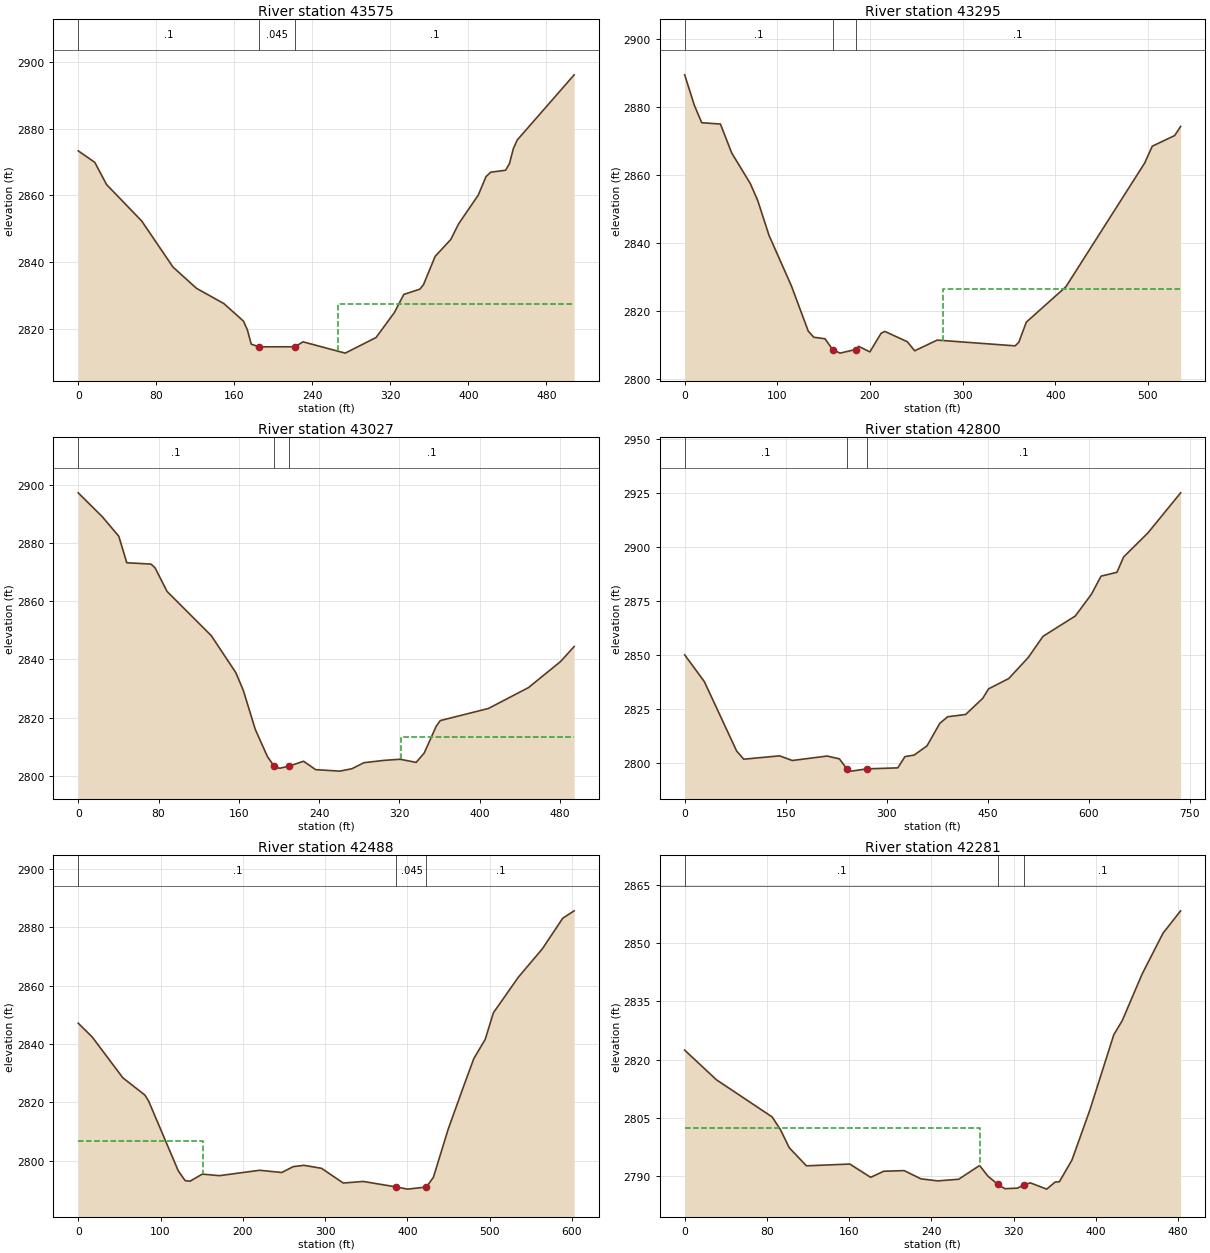
Type RM Length L Ch R = 1 ,43575   ,274.1,279.8,273.4
XS GIS Cut Line= 2
2207923.20459859601667.9734119082208430.36670059601704.103693582
#Sta/Elev= 30
       0 2873.35      17  2869.9      29 2863.27    65.1 2852.31    97.2 2838.49
   121.3 2832.12   149.3 2827.56   169.4  2822.3   173.4 2819.68   177.4 2815.38
   185.4 2814.59  222.29  2814.6   230.4 2816.09   273.7  2812.7   305.3 2817.37
     324 2824.82   333.8 2830.31   350.2 2831.87   353.9 2833.19   365.9 2841.72
   381.9 2846.76     390 2851.48   410.1 2860.07     418 2865.61   422.9 2866.95
   438.1 2867.53   442.1 2869.53   446.1 2874.05   450.1 2876.61   508.4 2896.14
#Mann= 3 ,0,0
       0      .1       0   185.4    .045       0  222.29      .1       0
#XS Ineff= 2 , 0
                          266.67         2827.44
Permanent Ineff=
       F       F
Bank Sta=185.4,222.29
XS Rating Curve= 0 ,0
Exp/Cntr(USF)=0,0
Exp/Cntr=0.3,0.1

Type RM Length L Ch R = 1 ,43295   ,266.5,267.5,269.1
XS GIS Cut Line= 3
2207877.89414176   601956.3128362208169.75546351601918.428350244
2208410.72736137601921.455180682
#Sta/Elev= 30
       0  2889.4    10.4 2880.48    18.4 2875.32    38.6 2874.93    50.7 2866.46
    70.9 2857.41    78.9 2852.41      91 2842.23   115.2 2827.34   133.4 2814.05
   139.4 2812.25   151.5  2811.8   159.6 2808.64   167.7 2807.58   184.4 2808.64
   187.8 2809.57   199.9 2807.95     212 2813.41   216.1 2813.96   240.3 2810.93
   248.3 2808.27   272.5 2811.41   356.7 2809.72   360.7 2810.79   368.7 2816.67
   411.5  2827.1   496.5 2863.47   504.7 2868.42   528.9 2871.55   535.3 2874.22
#Mann= 3 ,0,0
       0      .1       0   159.6    .045       0   184.4      .1       0
#XS Ineff= 2 , 0
                           278.8         2826.51
Permanent Ineff=
       F       F
Bank Sta=159.6,184.4
XS Rating Curve= 0 ,0
Exp/Cntr=0.3,0.1

Type RM Length L Ch R = 1 ,43027   ,237.5,227.9,225.1
XS GIS Cut Line= 2
2207859.75146601602202.3693944582208353.53198222602187.649650073
#Sta/Elev= 30
       0 2897.33      24 2889.11    40.4 2882.41    48.4 2873.28    72.5 2872.82
    76.5 2871.55    88.5 2863.42   132.5 2848.22     157 2835.48   164.5 2829.33
   176.4 2815.94   188.5  2806.6  195.15 2803.28   200.5 2802.57   209.6 2803.29
   224.5    2805   236.5 2802.11   260.5  2801.6   272.5 2802.41   284.5 2804.49
   304.6  2805.3   320.6 2805.68   336.6 2804.61   344.6 2807.79   356.6 2817.02
   360.6 2818.98   408.6 2823.15   448.5 2830.33   480.6 2839.34     494 2844.47
#Mann= 3 ,0,0
       0      .1       0  195.15    .045       0   209.6      .1       0
#XS Ineff= 2 , 0
                          321.37         2813.32
Permanent Ineff=
       F       F
Bank Sta=195.15,209.6
XS Rating Curve= 0 ,0
Exp/Cntr(USF)=0,0
Exp/Cntr=0.3,0.1

Type RM Length L Ch R = 1 ,42800   ,307.1,312,317.3
XS GIS Cut Line= 3
2207974.20836935602556.6822984032208214.31370021602346.086085452
     2208562.932      602116.959
#Sta/Elev= 30
       0 2849.99    29.2 2837.58    77.1 2805.42    87.7 2801.58     141 2803.13
   159.8 2800.97   211.6 2803.04   229.8 2801.73  240.75 2797.17     248 2796.04
   270.3 2797.09   316.5 2797.55   327.2 2802.78   340.8 2803.48   359.9 2807.76
     379 2818.24   390.7 2821.27   417.3 2822.33   442.7 2829.82   451.3 2834.21
   481.3 2838.98   510.4  2848.8   532.2 2858.57   580.1 2867.99     604 2878.04
   618.4  2886.5     642 2888.28   651.9 2895.38   688.2 2906.61   736.6 2925.15
#Mann= 3 ,0,0
       0      .1       0  240.75    .045       0   270.3      .1       0
Bank Sta=240.75,270.3
XS Rating Curve= 0 ,0
Exp/Cntr=0.3,0.1

Type RM Length L Ch R = 1 ,42488   ,201.2,206.8,211
XS GIS Cut Line= 2
2208031.88796187602783.7384991562208568.42264472602509.509661256
#Sta/Elev= 30
       0  2847.1      17 2842.38    54.2  2828.4    81.2 2822.44    85.7 2820.33
   121.6 2796.51   129.9 2793.17   135.9 2792.97   150.8  2795.4   171.6 2794.86
   220.4 2796.71   247.4 2795.95   261.2 2797.96   274.3  2798.4   295.7 2797.38
     322 2792.34   346.2 2792.88   386.7 2790.99   400.1 2790.25  423.18 2790.97
   431.6 2794.33   449.5 2810.74   467.5 2824.88   480.7 2834.98   494.5 2841.53
   504.5 2850.68   534.9  2862.9     564 2872.59   588.8 2883.08   602.6  2885.6
#Mann= 3 ,0,0
       0      .1       0   386.7    .045       0  423.18      .1       0
#XS Ineff= 2 , 0
          151.55 2806.68
Permanent Ineff=
       F       F
Bank Sta=386.7,423.18
XS Rating Curve= 0 ,0
Exp/Cntr(USF)=0,0
Exp/Cntr=0.3,0.1

Type RM Length L Ch R = 1 ,42281   ,227.5,227,221.8
XS GIS Cut Line= 3
2208134.57189854602875.1932606462208305.70189666602824.629356142
2208603.92941942602764.730546428
#Sta/Elev= 30
       0 2822.47    30.9 2814.83    85.1 2805.26    93.1 2802.03   101.8 2797.31
   118.5 2792.66   160.7 2793.12     181  2789.7   193.7 2791.27   213.6 2791.43
   229.9 2789.31   246.2 2788.78   266.6  2789.2     287 2792.75   295.2 2789.97
   304.8 2787.88   311.5 2786.78   323.8 2786.91  330.63 2787.83   336.4 2788.27
   352.3 2786.66   360.5 2788.48   364.6 2788.56   376.8 2794.12   394.1  2806.9
   417.6 2826.46   425.8 2830.08   445.1 2842.05   465.5 2852.61   482.6 2858.36
#Mann= 3 ,0,0
       0      .1       0   304.8    .045       0  330.63      .1       0
#XS Ineff= 2 , 0
          287.17 2802.51
Permanent Ineff=
       F       F
Bank Sta=304.8,330.63
XS Rating Curve= 0 ,0
Exp/Cntr=0.3,0.1

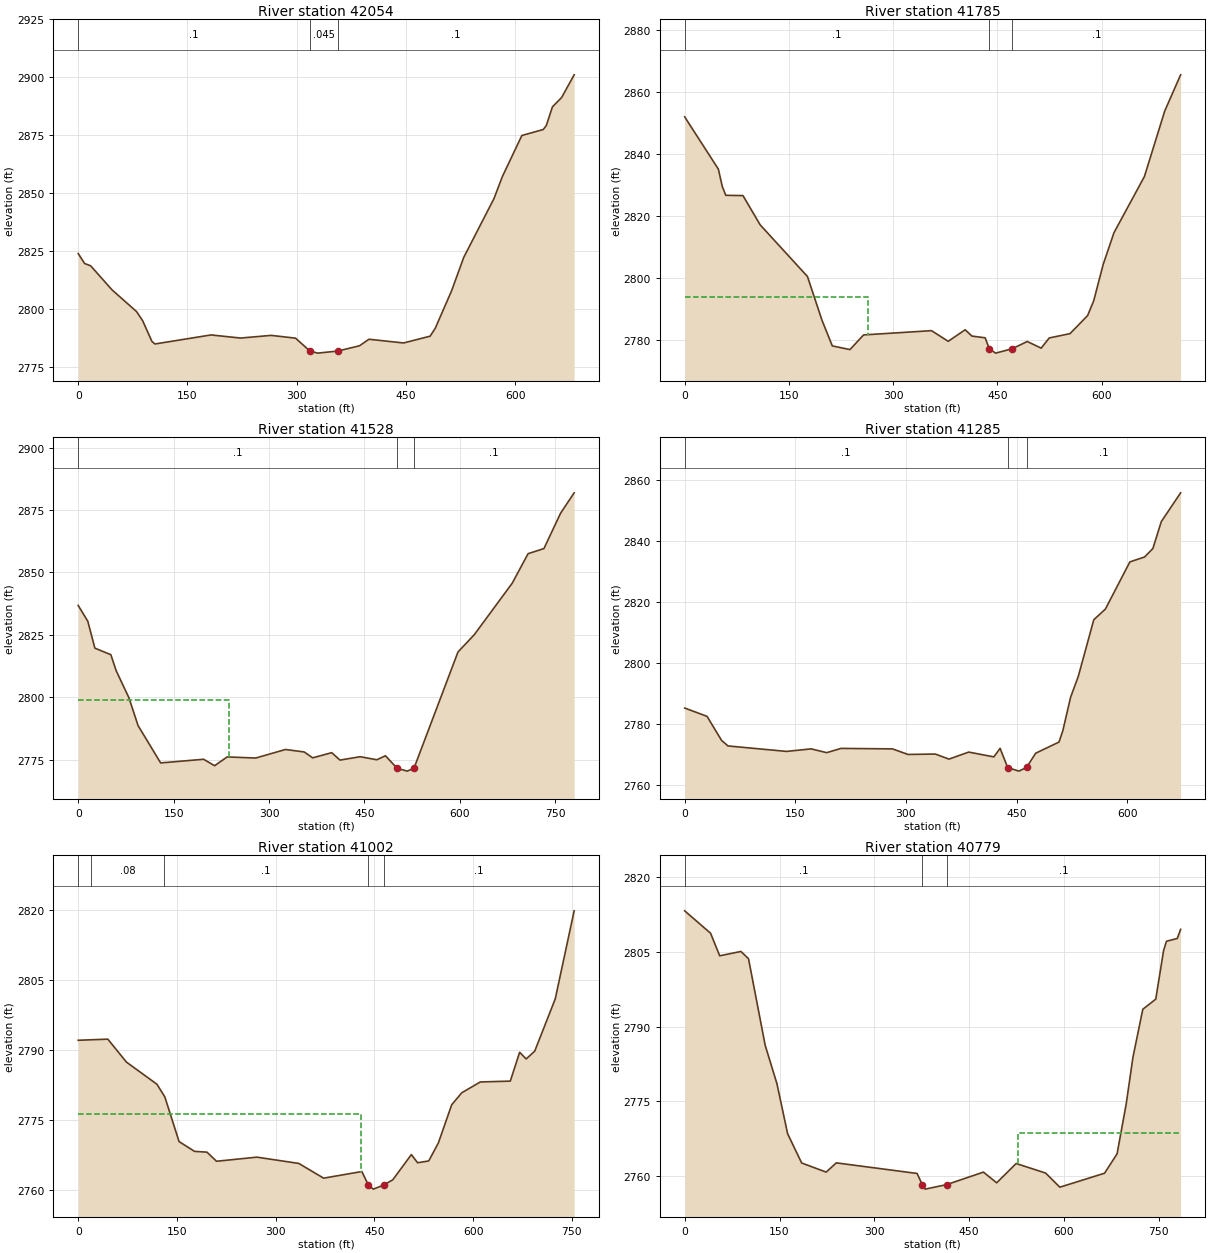
Type RM Length L Ch R = 1 ,42054   ,273.1,269.1,262.8
XS GIS Cut Line= 2
2208159.83585524603118.0741849252208808.55506268602911.264452628
#Sta/Elev= 30
       0 2824.04     8.8 2819.74    17.1 2818.76    46.5 2808.37    80.1 2799.03
    88.5 2795.08   101.1 2786.23   105.3 2785.06   182.4 2788.96   222.9 2787.62
   264.9 2788.77   298.4 2787.57  318.16    2782   328.9 2781.12   356.6 2782.03
   386.2 2784.29   399.2  2787.1   446.7  2785.5   483.2 2788.43   490.2 2791.83
   512.6 2807.96   529.3 2822.38   570.8 2847.71   582.4 2857.25   609.1 2874.92
   638.5  2877.5   642.7 2879.24   651.1 2887.27   663.7 2891.29   680.9 2901.07
#Mann= 3 ,-1,0
       0      .1       0  318.16    .045       0   356.6      .1       0
Bank Sta=318.16,356.6
XS Rating Curve= 0 ,0
Exp/Cntr(USF)=0,0
Exp/Cntr=0.3,0.1

Type RM Length L Ch R = 1 ,41785   ,257.4,256.1,255.2
XS GIS Cut Line= 3
     2208216.302      603525.0642208457.02733247603350.069667294
2208798.99561802603112.880619899
#Sta/Elev= 30
       0 2851.92    48.5  2835.1    54.2 2829.47    59.2 2826.68    83.9 2826.59
   108.6 2817.19   176.7 2800.57   197.7 2786.44   212.5 2778.22   237.9 2777.04
   257.5 2781.76   355.3 2783.13   379.3  2779.7   403.7 2783.42   413.4 2781.39
   432.5 2780.83   438.5 2777.25   447.5  2775.9  471.17 2777.29   493.1 2779.64
   513.1  2777.5   524.7 2780.78   554.6 2782.17   579.9 2787.97   588.7 2792.72
   602.3  2804.4   617.9 2814.66   661.7 2832.73   690.9 2853.79   713.8 2865.45
#Mann= 3 ,-1,0
       0      .1       0   438.5    .045       0  471.17      .1       0
#XS Ineff= 2 , 0
          263.65 2793.92
Permanent Ineff=
       F       F
Bank Sta=438.5,471.17
XS Rating Curve= 0 ,0
Exp/Cntr=0.3,0.1

Type RM Length L Ch R = 1 ,41528   ,244.2,243.4,242.5
XS GIS Cut Line= 2
2208356.05922777603744.757347628 2208982.3415303603280.410967564
#Sta/Elev= 30
       0 2836.79    15.1 2830.45    26.2  2819.7    51.3 2817.07    59.7 2810.66
    79.8 2799.79    94.1 2788.69   129.6 2773.74   197.1 2775.21   214.4 2772.63
   234.2 2776.15     279  2775.7   325.8 2779.12   355.2 2778.14   368.6 2775.78
   398.5 2777.85   411.5 2774.88   443.3 2776.23   469.4 2775.01     483 2776.61
  501.12 2771.63   517.3 2770.46  527.88 2771.65     597 2818.17   622.6 2825.08
   682.3 2845.72   707.2 2857.52   732.1 2859.56   758.2 2873.69   779.6 2881.88
#Mann= 3 ,-1,0
       0      .1       0  501.12    .045       0  527.88      .1       0
#XS Ineff= 2 , 0
          237.42 2798.87
Permanent Ineff=
       F       F
Bank Sta=501.12,527.88
XS Rating Curve= 0 ,0
Exp/Cntr(USF)=0,0
Exp/Cntr=0.3,0.1

Type RM Length L Ch R = 1 ,41285   ,280.3,283,284.1
XS GIS Cut Line= 2
     2208581.402      603917.0852209093.90671268603481.975572865
#Sta/Elev= 30
       0  2785.2    30.3 2782.47    50.1 2774.53    58.7 2772.74   138.1 2770.94
   171.5 2771.77   192.5 2770.53   211.9 2771.93   281.7 2771.77   302.7 2769.94
   339.8 2770.07   358.3 2768.41     385 2770.72   419.1 2769.14   427.6 2771.95
  437.892765.615   453.1 2764.46   463.4 2765.67   475.9 2770.36   507.4 2774.01
   512.6 2777.72   523.1  2788.7   533.6 2795.62   554.6 2814.22   570.3 2817.72
   603.5 2833.23   623.4 2834.85   634.7 2837.63   646.1 2846.48   672.3 2855.94
#Mann= 3 ,-1,0
       0      .1       0  437.89    .045       0   463.4      .1       0
Bank Sta=437.89,463.4
XS Rating Curve= 0 ,0
Exp/Cntr=0.3,0.1

Type RM Length L Ch R = 1 ,41002   ,219.9,223.3,224.1
XS GIS Cut Line= 3
2208697.95607204604096.1604726892209213.89649433603776.407479881
 2209306.0287126 603662.59709261
#Sta/Elev= 30
       0 2792.03      45 2792.27    73.2 2787.36   119.6 2782.61   131.6  2779.9
   153.2 2770.33   176.7 2768.23   195.6 2768.06   210.1 2766.11   271.4 2766.99
     335 2765.65   372.8 2762.49   430.9 2763.91   440.92760.985   448.3 2760.14
   463.8    2761   477.9 2762.14   506.1 2767.54   515.6 2765.79   532.5 2766.18
   547.1 2770.03   567.4 2778.22   582.7 2780.78   610.9  2783.1   656.4 2783.28
   670.6 2789.46   680.5 2788.03   693.5  2789.7   724.7  2800.9   753.4 2819.76
#Mann= 5 ,-1,0
       0      .1       0      20     .08       0     130      .1       0
   440.9    .045       0   463.8      .1       0
#XS Ineff= 2 , 0
          429.62 2776.21
Permanent Ineff=
       F       F
Bank Sta=440.9,463.8
XS Rating Curve= 0 ,0
Exp/Cntr(USF)=0,0
Exp/Cntr=0.3,0.1

Type RM Length L Ch R = 1 ,40779   ,241.9,225.8,214.4
XS GIS Cut Line= 3
2208841.46128614604209.2335236972209312.67328673603982.275332939
2209446.91490403603757.982810425
#Sta/Elev= 30
       0 2813.29      41 2808.78    55.4 2804.25      89 2805.12     101 2803.66
   127.3 2786.28   145.9 2778.55   162.8 2768.49     185  2762.6   223.8 2760.76
   239.8 2762.62   367.6 2760.49     376 2758.19   380.4 2757.34  414.11 2758.24
   472.5 2760.76   493.5 2758.61   524.3 2762.49   570.9 2760.57   593.4 2757.73
   664.1 2760.54   683.9 2764.43   698.4 2774.51     709 2783.85   724.6  2793.5
   745.1 2795.54   757.4 2805.26     762 2807.17   779.1 2807.73   784.4 2809.56
#Mann= 3 ,-1,0
       0      .1       0     376    .045       0  414.11      .1       0
#XS Ineff= 2 , 0
                          526.85         2768.56
Permanent Ineff=
       F       F
Bank Sta=376,414.11
XS Rating Curve= 0 ,0
Exp/Cntr=0.3,0.1

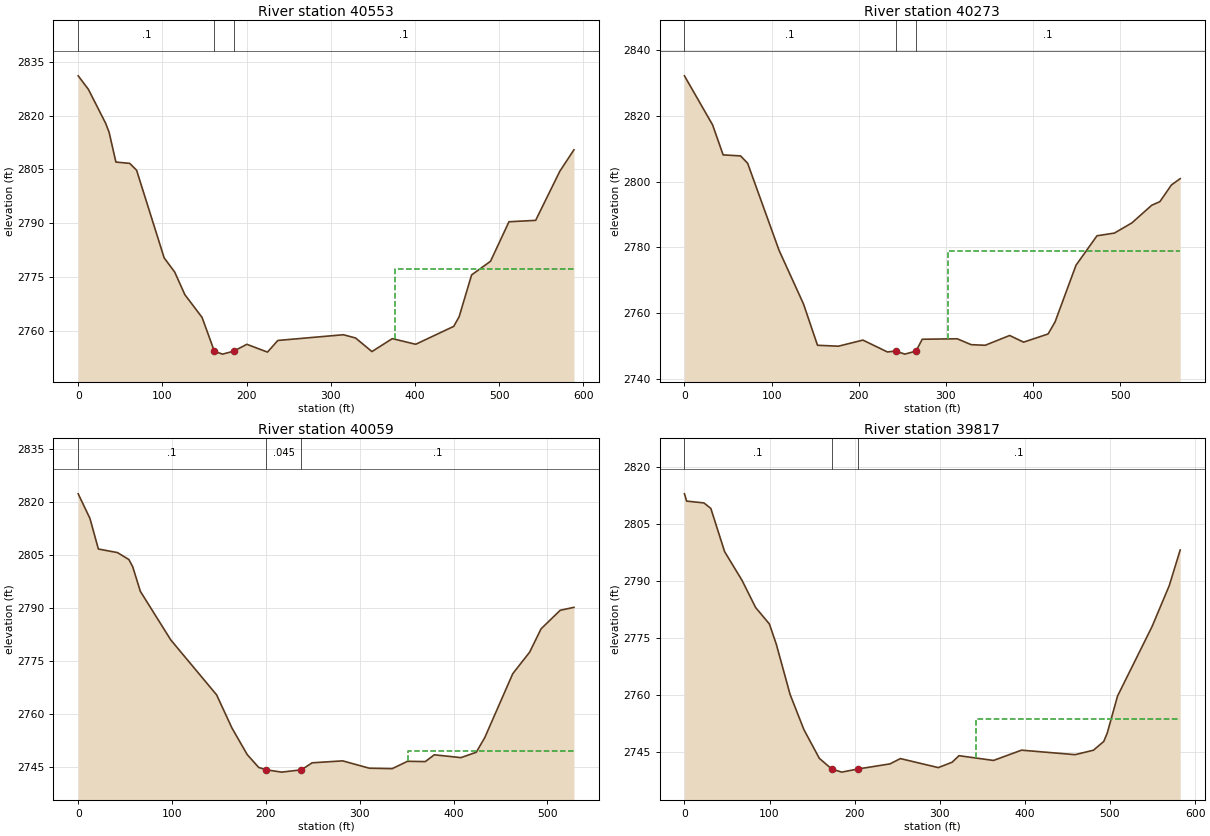
Type RM Length L Ch R = 1 ,40553   ,281,279.7,277.8
XS GIS Cut Line= 3
2209323.70247556604337.0102902462209391.61998925604023.121240501
2209538.46866749 603799.17700618
#Sta/Elev= 30
       0 2831.03    12.1 2827.28    32.6 2817.84    36.7 2815.36    44.8 2807.06
    61.2 2806.69    69.4 2804.78   102.1 2780.44   114.7 2776.46   126.7  2770.2
   147.2 2763.86   161.8 2754.44   171.5 2753.66  184.57 2754.47   200.4 2756.39
   224.9 2754.22   237.2 2757.46     315 2759.05   329.5 2758.15     349 2754.37
   373.2 2757.97     401  2756.4   446.2 2761.38   452.6 2764.06   467.4 2775.68
   489.9 2779.48   511.8 2790.46   543.5 2790.85   572.2 2804.49     589 2810.47
#Mann= 3 ,-1,0
       0      .1       0   161.8    .045       0  184.57      .1       0
#XS Ineff= 2 , 0
                          375.81         2777.31
Permanent Ineff=
       F       F
Bank Sta=161.8,184.57
XS Rating Curve= 0 ,0
Exp/Cntr(USF)=0,0
Exp/Cntr=0.3,0.1

Type RM Length L Ch R = 1 ,40273   ,214.7,214.2,215.3
XS GIS Cut Line= 3
2209619.58316956604409.3460250232209627.42921696604324.616371504
2209659.63004239603841.883635855
#Sta/Elev= 30
       0 2832.12    32.3 2817.22    44.4 2808.11    64.4  2807.8    72.5 2805.58
   108.6 2779.11   136.6 2762.85   152.7 2750.29   176.7 2750.01   204.8 2751.86
   232.9 2748.26  242.47 2748.54   252.9  2747.6   265.7 2748.52   272.9 2752.12
     313 2752.26   329.1 2750.47   345.1 2750.29   373.2 2753.26   389.2 2751.24
   417.3 2753.72   425.3 2757.37   449.3 2774.58   473.4 2783.54   493.4 2784.36
   513.5 2787.46   536.2 2792.81   545.6 2793.91   558.8 2798.97   568.9 2800.89
#Mann= 3 ,-1,0
       0      .1       0  242.47    .045       0   265.7      .1       0
#XS Ineff= 2 , 0
                          301.87         2778.94
Permanent Ineff=
       F       F
Bank Sta=242.47,265.7
XS Rating Curve= 0 ,0
Exp/Cntr=0.3,0.1

Type RM Length L Ch R = 1 ,40059   ,239.3,242.2,240.5
XS GIS Cut Line= 2
2209802.79628833604434.2975395822209898.24792919603914.820340296
#Sta/Elev= 30
       0 2822.38    12.5 2815.42    21.5 2806.74    41.8 2805.73      54 2803.76
    58.1  2801.7    66.2 2794.76    98.7 2780.96   147.5  2765.4   163.8 2756.02
   180.1 2748.48   192.3 2744.84   200.4 2744.17   216.7 2743.51  237.87 2744.16
   249.2 2746.15   281.8  2746.7   310.2 2744.62   334.6  2744.5   350.9 2746.58
   369.8  2746.5   379.4 2748.42   407.8 2747.62   424.1 2749.14   433.2  2753.3
     463  2771.4     481 2777.51   493.2 2784.13   513.6 2789.38   528.2 2790.21
#Mann= 3 ,-1,0
       0      .1       0   200.4    .045       0  237.87      .1       0
#XS Ineff= 2 , 0
                          351.17         2749.48
Permanent Ineff=
       F       F
Bank Sta=200.4,237.87
XS Rating Curve= 0 ,0
Exp/Cntr(USF)=0,0
Exp/Cntr=0.3,0.1

Type RM Length L Ch R = 1 ,39817   ,278.8,286,294.2
XS GIS Cut Line= 2
2210029.29137275604499.7681263662210120.83607097603924.484708898
#Sta/Elev= 30
       0 2812.82     2.6 2810.91    22.9 2810.43      31 2808.99    47.2 2797.63
    67.7 2790.07    83.6 2782.95    99.8 2778.63   107.9 2773.33   124.1 2760.13
   140.3 2750.89   158.5 2743.31   173.1 2740.51   184.9 2739.69  203.71 2740.51
   241.6 2741.86   253.7 2743.25   298.3 2740.88   314.5 2742.29   322.6 2744.01
   363.1 2742.76   396.1 2745.46     459 2744.28   480.6 2745.45   492.7 2747.76
   496.8 2749.96   508.9 2759.69   549.4 2777.92   569.7 2788.73   582.5 2798.06
#Mann= 3 ,-1,0
       0      .1       0   173.1    .045       0  203.71      .1       0
#XS Ineff= 2 , 0
                          342.91         2753.74
Permanent Ineff=
       F       F
Bank Sta=173.1,203.71
XS Rating Curve= 0 ,0
Exp/Cntr=0.3,0.1