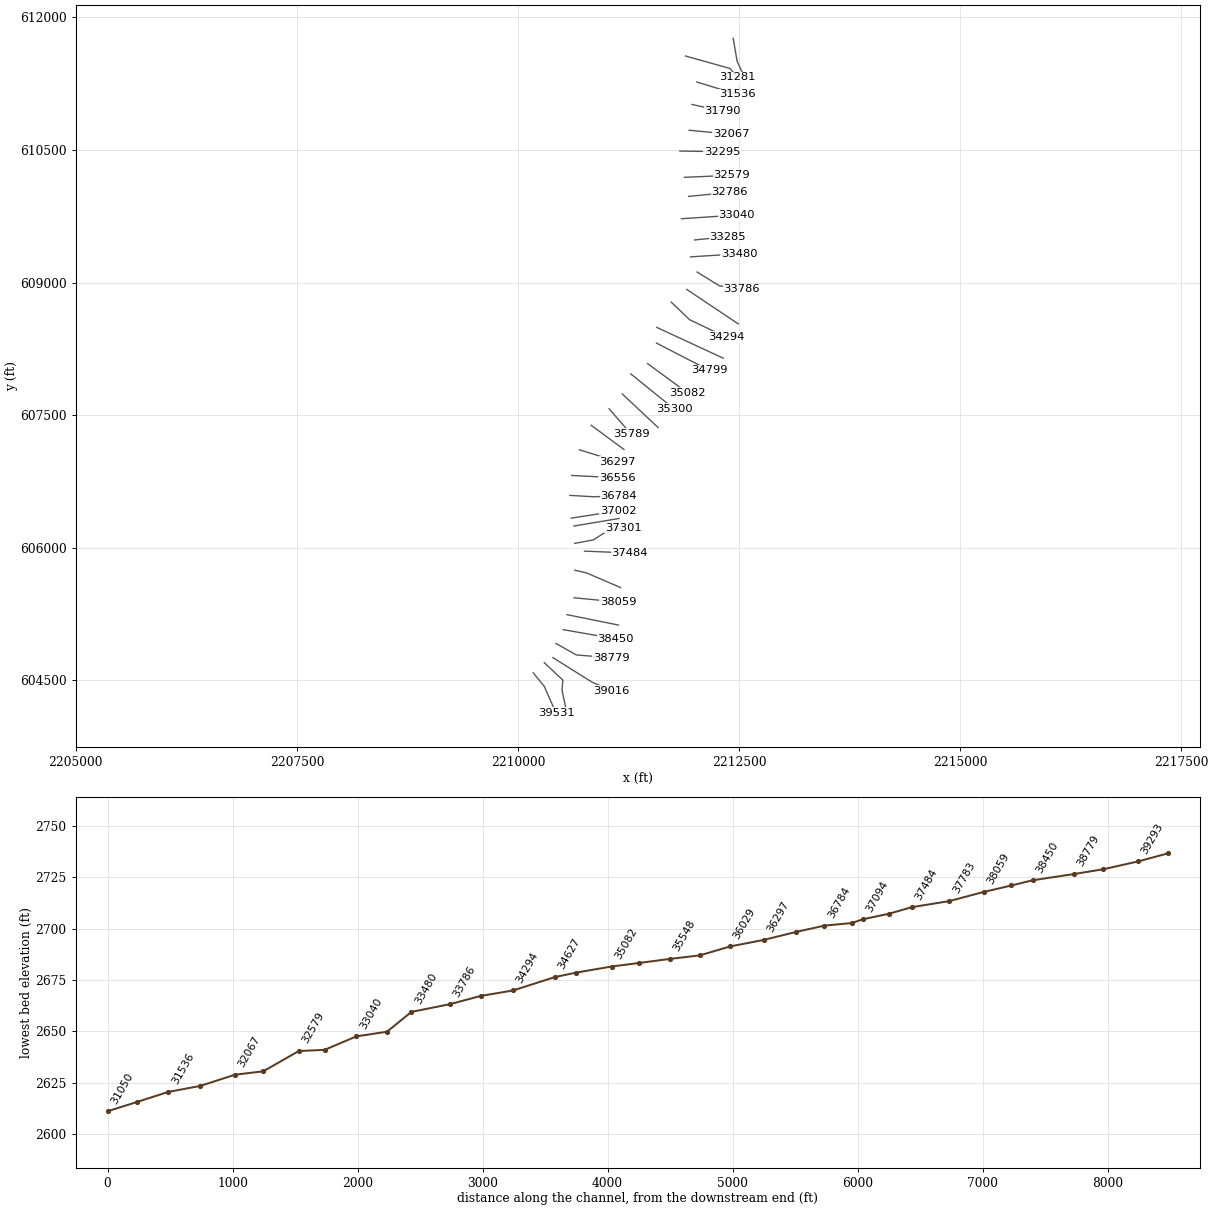
HEC-RAS study LFBUCKRV.prj: LFBUCKRV

--- LFBUCKRV.g01 (geometry) --- (continued)

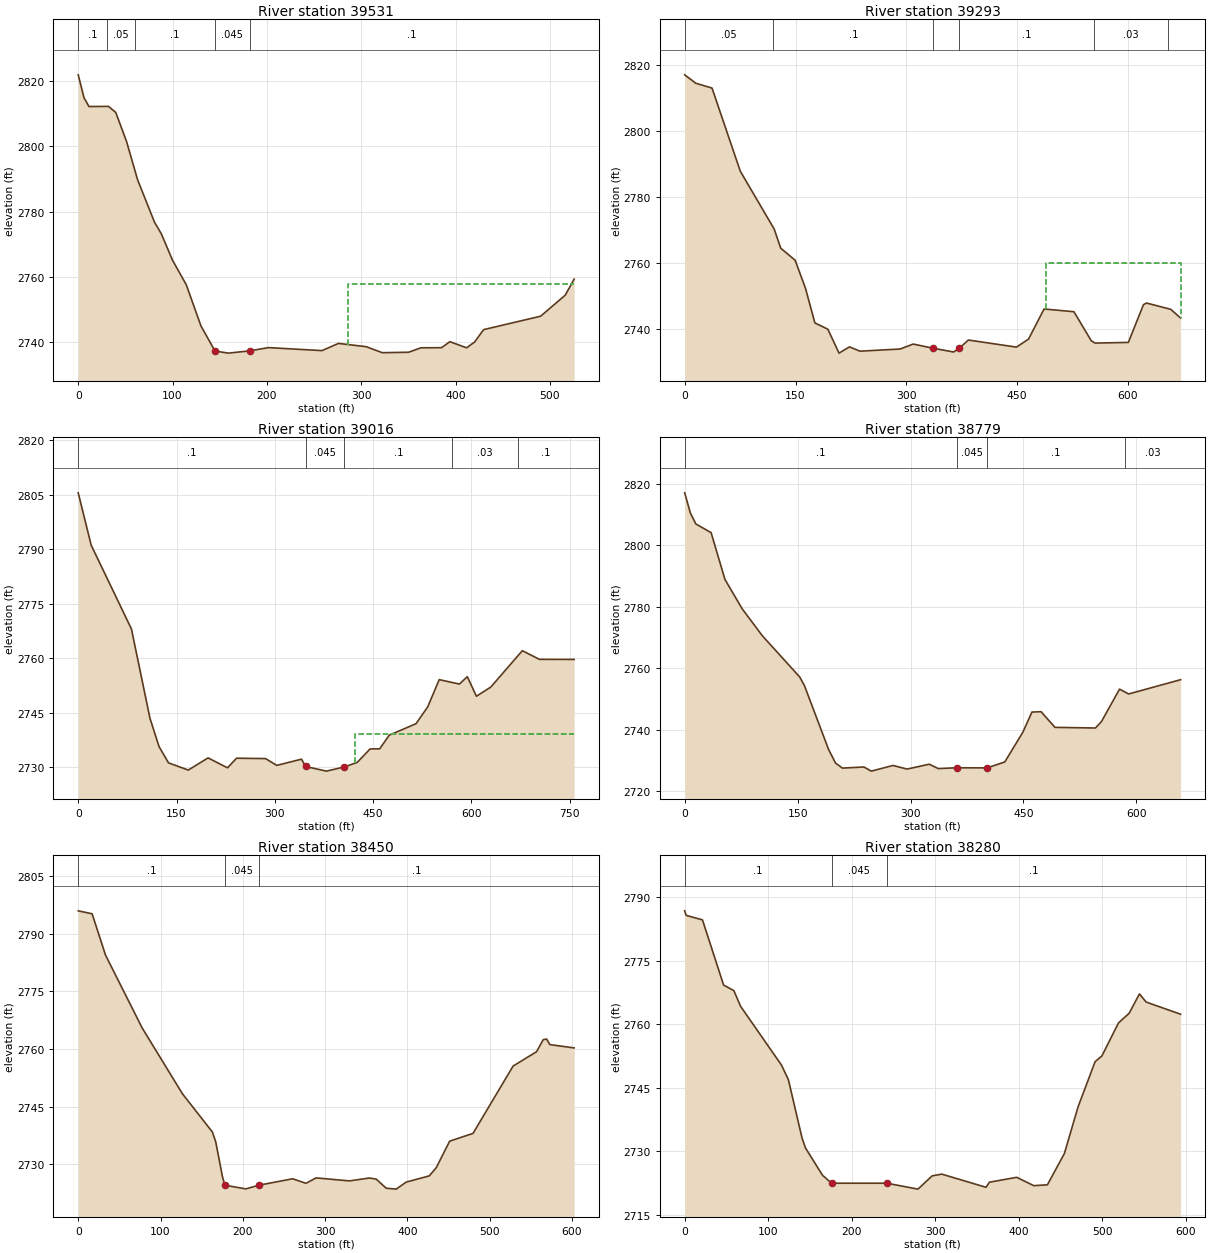
Type RM Length L Ch R = 1 ,39531   ,240.4,237.7,214.3
XS GIS Cut Line= 3
2210173.02005675604586.0014829522210297.69979424604433.183897233
2210430.14909391604132.588752011
#Sta/Elev= 30
       0 2821.94     6.2 2814.88    11.4 2812.22      32 2812.27    39.8 2810.42
    51.2 2801.55      63 2789.73    80.9 2776.76    88.1 2773.22    99.9 2765.16
   114.6 2757.57   130.1 2744.98     145 2737.29   159.2 2736.64   181.7 2737.33
   201.6 2738.33   258.4 2737.41   275.9 2739.62   305.3 2738.61   322.4 2736.77
   350.2 2736.91   363.3 2738.27   385.2 2738.31   393.9 2740.15   411.7 2738.27
   420.2 2740.05   429.7 2743.84   490.1 2747.95   516.3 2754.41   525.7 2759.33
#Mann= 5 ,-1,0
       0      .1       0      30     .05       0      60      .1       0
     145    .045       0   181.7      .1       0
#XS Ineff= 2 , 0
                          286.34         2757.68
Permanent Ineff=
       F       F
Bank Sta=145,181.7
XS Rating Curve= 0 ,0
Exp/Cntr(USF)=0,0
Exp/Cntr=0.3,0.1

Type RM Length L Ch R = 1 ,39293   ,254.5,276.9,304.1
XS GIS Cut Line= 4
2210297.11976859604701.361937462      2210507.53604505.039514244
2210498.23921527604388.9507033472210554.89286449604128.023028489
#Sta/Elev= 30
       0 2816.89    15.1 2814.34      37 2812.89    75.3 2787.73   121.2 2770.23
     130 2764.46   149.5 2760.82   163.6 2752.28   176.2 2741.87   193.8 2739.96
   208.9 2732.73     223 2734.62   237.2 2733.32   291.6 2733.97   309.3 2735.47
   336.3 2734.21   363.9 2733.07   371.9 2734.24   383.9 2736.69     449 2734.55
   465.4 2736.98   486.4 2746.08   526.8 2745.25   550.3 2736.46   555.5 2735.77
   600.5 2735.97   620.9 2747.38     625 2747.88   657.8 2745.98   671.2 2743.35
#Mann= 6 ,-1,0
       0     .05       0     120      .1       0   336.3    .045       0
   371.9      .1       0  554.24     .03       0  654.24      .1       0
#XS Ineff= 2 , 0
                          489.09         2759.95
Permanent Ineff=
       F       T
Bank Sta=336.3,371.9
XS Rating Curve= 0 ,0
Exp/Cntr=0.3,0.1

Type RM Length L Ch R = 1 ,39016   ,224.3,237,249.7
XS GIS Cut Line= 3
2210395.38677465604758.3409936372210836.97910621604481.788220336
2211052.57132195604386.630276834
#Sta/Elev= 30
       0 2805.47    19.8 2791.07    81.2 2768.04   109.5 2743.47   123.3  2735.7
   137.8 2731.21     168 2729.23   198.1 2732.58   227.8 2729.85   241.6 2732.49
   285.8 2732.39     303 2730.52   340.7 2732.23   346.8 2730.22   378.7 2728.94
  406.28  2730.1   425.7 2731.34   445.4 2735.05     460 2735.07   474.5 2738.82
   515.4 2741.98   533.3 2746.61   550.8  2754.1   581.6 2752.88   593.7 2754.91
   607.6 2749.53   629.5 2752.05   677.6 2762.06   703.8 2759.67   756.7 2759.66
#Mann= 5 ,-1,0
       0      .1       0   346.8    .045       0  406.28      .1       0
  571.04     .03       0  671.04      .1       0
#XS Ineff= 2 , 0
                          422.25         2739.21
Permanent Ineff=
       F       F
Bank Sta=346.8,406.28
XS Rating Curve= 0 ,0
Exp/Cntr(USF)=0,0
Exp/Cntr=0.3,0.1

Type RM Length L Ch R = 1 ,38779   ,320.3,329.5,316.6
XS GIS Cut Line= 3
2210429.57615288604918.8689659512210660.24023141604788.916084781
 2211052.9909319604757.295259902
#Sta/Elev= 30
       0 2817.06     7.6 2810.49    14.9 2806.93    35.1 2804.12    53.5  2788.9
    76.4 2779.35     103 2770.64   152.9 2757.16   159.1 2754.38   191.2 2733.61
   200.4  2729.2   209.6 2727.56   238.1 2727.93   247.9 2726.58   276.7 2728.42
   295.5 2727.25   324.9 2728.83   336.9 2727.41   361.2 2727.67  401.69 2727.63
   425.2 2729.55   449.3 2739.26   461.3 2745.78   473.4 2745.91   491.9 2740.81
   545.6  2740.6   553.6 2742.67   577.7 2753.24   589.7 2751.66   658.8 2756.31
#Mann= 4 ,-1,0
       0      .1       0   361.2    .045       0  401.69      .1       0
  584.75     .03       0
Bank Sta=361.2,401.69
XS Rating Curve= 0 ,0
Exp/Cntr=0.3,0.1

Type RM Length L Ch R = 1 ,38450   ,170.3,169.8,172.1
XS GIS Cut Line= 2
2210511.49151434605074.8348862292211105.23247651604971.261412099
#Sta/Elev= 30
       0 2795.92    16.9 2795.15    33.2  2784.4    77.8 2765.43   126.6 2748.37
   163.1 2738.39   167.2 2735.79   175.3 2726.78   178.3 2724.56   203.7 2723.61
   219.8 2724.58   260.6 2726.24   276.8 2725.06     289 2726.47   329.6 2725.69
   353.9 2726.44   362.1 2726.16   374.3 2723.79   386.4 2723.55   398.6 2725.38
   426.7    2727   435.2 2729.16   451.4 2736.02   479.8 2738.04   528.5 2755.55
     557 2759.28   565.1 2762.41   569.2 2762.58   573.2 2761.13   602.7 2760.27
#Mann= 3 ,-1,0
       0      .1       0   178.3    .045       0   219.8      .1       0
Bank Sta=178.3,219.8
XS Rating Curve= 0 ,0
Exp/Cntr(USF)=0,0
Exp/Cntr=0.3,0.1

Type RM Length L Ch R = 1 ,38280   ,219.7,220.8,225.4
XS GIS Cut Line= 2
2210554.46434463605244.5555423732211136.49187112605127.014742938
#Sta/Elev= 30
       0 2786.79     1.7 2785.72    21.3 2784.65    46.6 2769.25    58.9 2767.92
      67 2764.21     116  2750.3   124.2 2746.86   140.5 2733.11   144.6 2730.76
     165 2724.29  175.91 2722.41     242 2722.41   279.3 2721.01   296.3 2724.14
   307.8 2724.56   360.8 2721.44   364.9 2722.65   397.6  2723.8     418 2721.83
   434.3 2722.03   454.7 2729.46     471 2740.45   491.4 2751.13   499.6 2752.51
   519.4 2760.29   532.2 2762.58   544.5 2767.15   552.6 2765.22   593.8 2762.35
#Mann= 3 ,-1,0
       0      .1       0  175.91    .045       0     242      .1       0
Bank Sta=175.91,242
XS Rating Curve= 0 ,0
Exp/Cntr=0.3,0.1

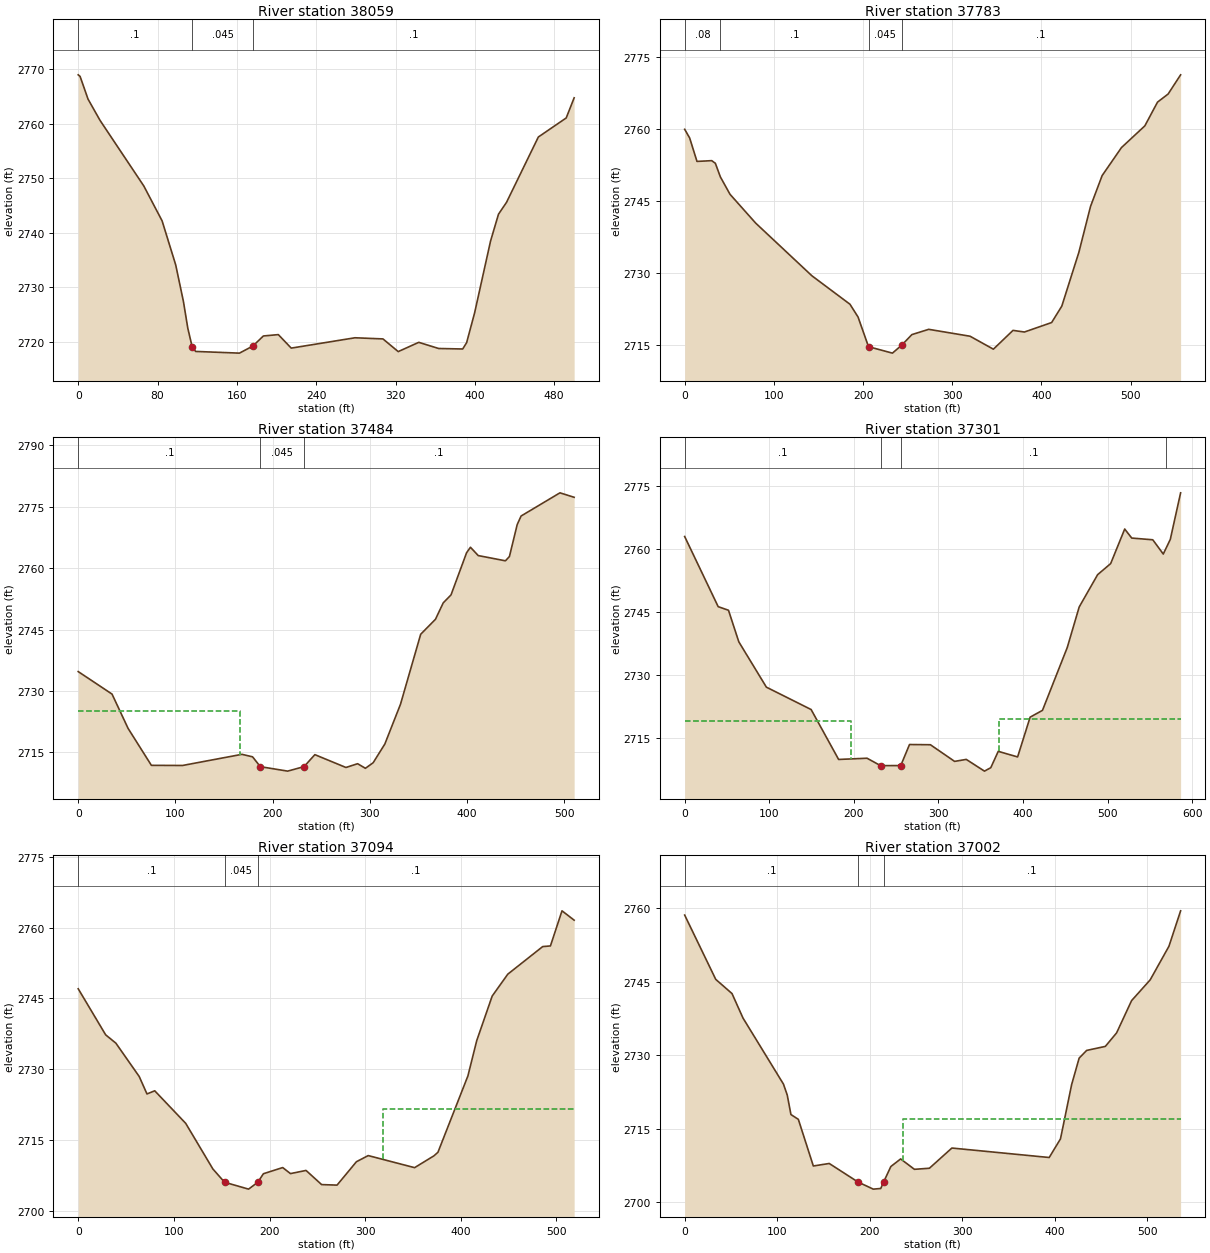
Type RM Length L Ch R = 1 ,38059   ,280.4,276.6,264
XS GIS Cut Line= 2
2210634.32623219605435.6501245582211132.12122413605387.476415661
#Sta/Elev= 30
       0 2768.99     1.9  2768.7     9.9 2764.53      22 2760.63    66.2 2748.56
    84.6 2742.17    98.3 2734.09   106.1 2727.37   110.5 2722.46     115 2718.97
   118.4 2718.19   162.6 2717.88   176.2 2719.19   186.7 2721.03   201.8 2721.28
   214.8  2718.8   279.1  2720.7   307.3 2720.49   322.7 2718.16   343.4 2719.86
   363.5 2718.73   387.7 2718.64   391.7 2719.81   399.7 2725.26   415.8 2738.46
   423.8 2743.39   431.9 2745.57     464 2757.57   492.1 2761.07   500.1 2764.77
#Mann= 3 ,-1,0
       0      .1       0     115    .045       0   176.2      .1       0
Bank Sta=115,176.2
XS Rating Curve= 0 ,0
Exp/Cntr(USF)=0,0
Exp/Cntr=0.3,0.1

Type RM Length L Ch R = 1 ,37783   ,287.4,298.9,303.8
XS GIS Cut Line= 3
2210642.71332384 605747.893485942210776.72359863605716.221246459
2211161.00652118605550.954316866
#Sta/Elev= 30
       0 2759.95     5.6 2758.14    13.8 2753.27    30.3 2753.43    34.4 2752.88
      40 2750.06    50.8 2746.44    79.6 2740.44   142.6 2729.49   185.3 2723.57
   194.4  2720.9   206.1 2714.74   232.9  2713.4   243.1 2715.01   254.7 2717.25
   273.6 2718.35     320 2716.91   346.1 2714.22   368.1 2718.13   380.9 2717.79
   411.4 2719.76   422.8 2723.18   441.9 2734.35     455 2743.91     468 2750.32
   489.7 2756.15   515.9 2760.67   530.1  2765.6     542 2767.29     556 2771.28
#Mann= 4 ,-1,0
       0     .08       0      40      .1       0   206.1    .045       0
   243.1      .1       0
Bank Sta=206.1,243.1
XS Rating Curve= 0 ,0
Exp/Cntr=0.3,0.1

Type RM Length L Ch R = 1 ,37484   ,164.3,183.1,191.5
XS GIS Cut Line= 2
2210752.91340081605963.1608222422211262.75181998605941.750284954
#Sta/Elev= 30
       0 2734.74    34.8 2729.25    51.3 2720.89    75.3 2711.86   107.4 2711.83
   168.5 2714.55   179.4 2713.94   187.4 2711.54   215.5 2710.45   232.4 2711.55
   243.5 2714.47   275.5 2711.34   287.5 2712.26   295.5 2711.14   303.5  2712.5
   315.5 2717.06   331.6 2726.76   352.4 2743.85   367.6  2747.5   375.6 2751.51
   383.6 2753.45   399.6 2763.73   403.6 2765.08   411.6 2763.05   439.6 2761.77
   443.7 2762.82   451.7 2770.61   455.7  2772.7   495.7 2778.36   510.3 2777.27
#Mann= 3 ,-1,0
       0      .1       0   187.4    .045       0   232.4      .1       0
#XS Ineff= 2 , 0
          166.87 2725.04
Permanent Ineff=
       F       F
Bank Sta=187.4,232.4
XS Rating Curve= 0 ,0
Exp/Cntr(USF)=0,0
Exp/Cntr=0.3,0.1

Type RM Length L Ch R = 1 ,37301   ,212.9,207,202.3
XS GIS Cut Line= 4
2210641.21371821606050.7025868012210853.18420189606089.972460106
2210982.07418659606173.0383244942211192.00472304606229.556413199
#Sta/Elev= 30
       0  2762.9    39.6 2746.27    51.8 2745.41      64 2737.92    96.6 2727.17
   149.5 2721.86     182 2710.02   215.6 2710.31   231.6 2708.55  255.45 2708.57
   265.8 2713.56   290.5 2713.51   319.1 2709.56   332.9 2710.03   354.4 2707.25
   361.9 2708.07   370.7 2711.94   393.6 2710.62   408.4 2720.05     423 2721.67
   452.3 2736.58   466.4 2746.19   488.2 2753.86   503.6 2756.48   520.2 2764.68
   528.5 2762.54   553.4 2762.13   565.8 2758.75   574.1 2762.22   586.3 2773.27
#Mann= 4 ,-1,0
       0      .1       0   231.6    .045       0  255.45      .1       0
  568.92     .03       0
#XS Ineff= 2 , 0
          197.06  2719.1  371.06          2719.6
Permanent Ineff=
       F       F
Bank Sta=231.6,255.45
XS Rating Curve= 0 ,0
Exp/Cntr=0.3,0.1

Type RM Length L Ch R = 1 ,37094   ,93.1,91.6,91.6
XS GIS Cut Line= 2
2210633.27392475606247.0636151612211144.68740378606332.596183082
#Sta/Elev= 30
       0 2747.04    28.7 2737.28    39.4 2735.51    63.8 2728.44    71.9 2724.75
      80 2725.42   112.4 2718.52   140.8 2708.85     153 2706.04   178.1 2704.58
  187.74 2706.03   193.6 2707.84   213.8 2709.15   221.9 2707.87   238.2 2708.54
   254.5 2705.54   270.6 2705.43   290.9 2710.39   303.2 2711.69   351.7 2709.13
     372 2711.65   376.1 2712.39   407.4 2728.56   416.6 2736.02   432.8 2745.49
   449.1 2750.13   485.6 2755.98   493.7 2756.12   505.8 2763.56   518.5 2761.58
#Mann= 3 ,-1,0
       0      .1       0     153    .045       0  187.74      .1       0
#XS Ineff= 2 , 0
                          318.15         2721.55
Permanent Ineff=
       F       F
Bank Sta=153,187.74
XS Rating Curve= 0 ,0
Exp/Cntr(USF)=0,0
Exp/Cntr=0.3,0.1

Type RM Length L Ch R = 1 ,37002   ,224.7,218.2,215.4
XS GIS Cut Line= 2
2210602.66896926606336.3135318792211132.57976713606418.208837005
#Sta/Elev= 30
       0  2758.6    33.6 2745.49    51.2 2742.59      63 2737.62   106.8 2724.13
   110.9 2721.89   114.9 2717.92   122.9 2716.94   139.1 2707.43   156.3 2707.94
   187.5 2704.15   203.9 2702.71     212 2702.84   215.2  2704.2   222.9 2707.32
   233.5 2708.87   248.4 2706.75   264.6 2706.97   288.9 2711.09   394.1 2709.16
   406.3 2712.95   418.4 2724.05   426.5 2729.43   434.6    2731   454.8 2731.82
     467 2734.58   483.2 2741.16   503.3 2745.39   523.6 2752.25   536.2 2759.47
#Mann= 3 ,-1,0
       0      .1       0   187.5    .045       0   215.2      .1       0
#XS Ineff= 2 , 0
                          236.07         2717.04
Permanent Ineff=
       F       F
Bank Sta=187.5,215.2
XS Rating Curve= 0 ,0
Exp/Cntr(USF)=0,0
Exp/Cntr=0.3,0.1

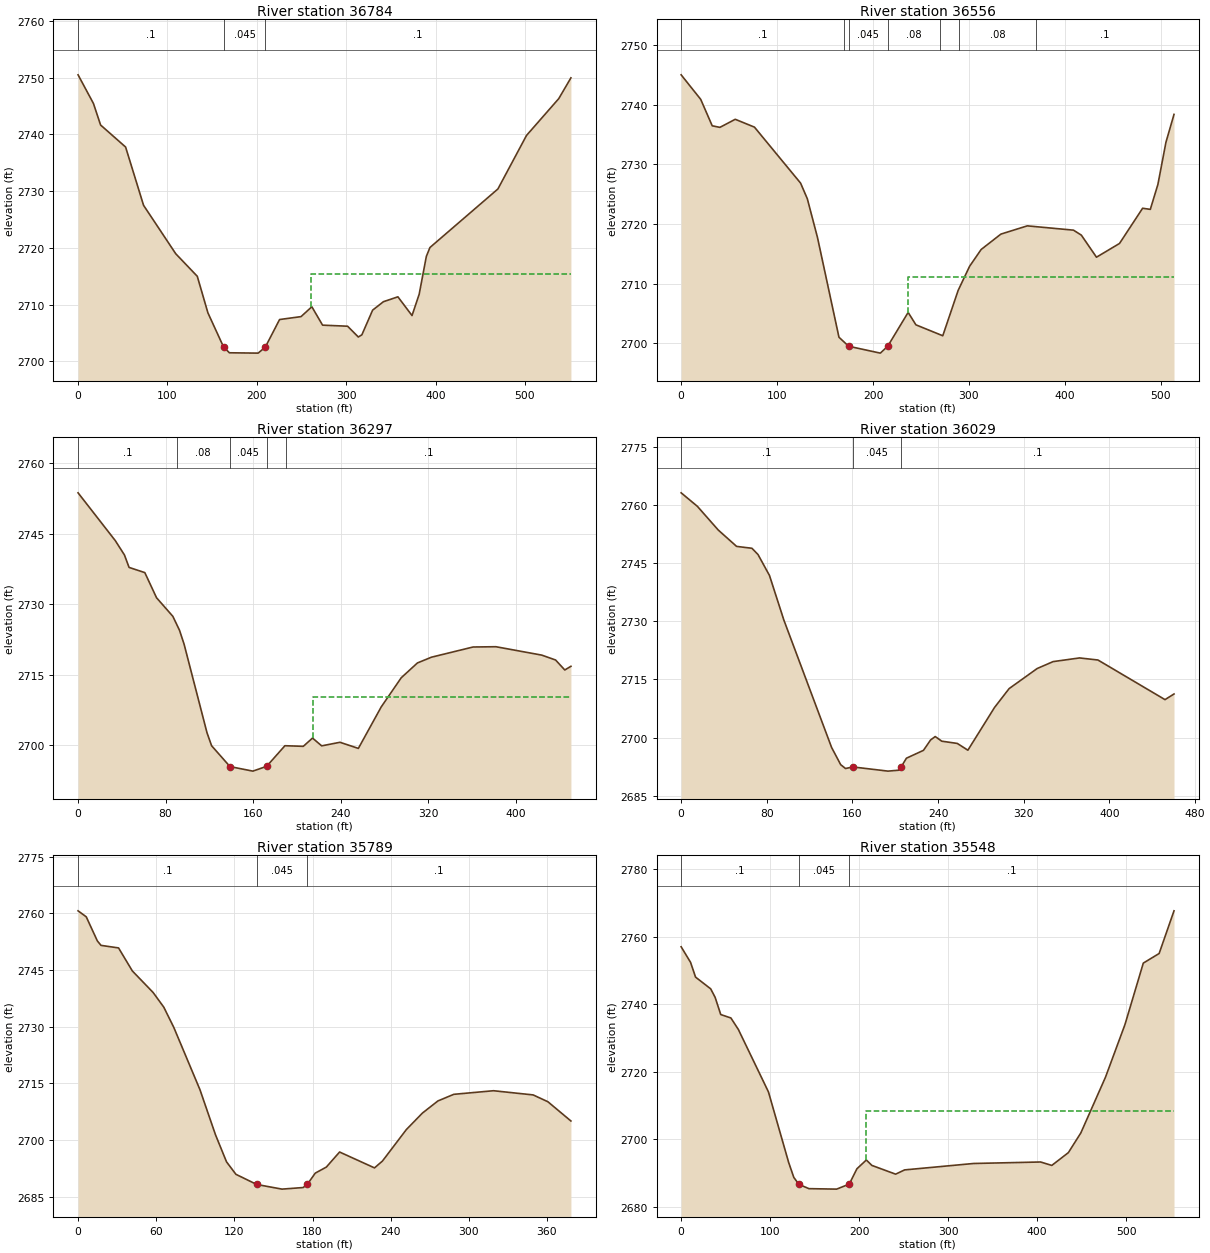
Type RM Length L Ch R = 1 ,36784   ,228.5,227.9,228.2
XS GIS Cut Line= 3
 2210587.0361303606593.3758769072210862.72419767606577.665841419
2211137.84610646 606590.26034322
#Sta/Elev= 30
       0 2750.49    17.2 2745.45    25.2 2741.65    53.2 2737.77    73.3  2727.5
   109.3 2718.97   133.4    2715   145.3 2708.56  162.95  2702.5   169.4 2701.52
   201.5 2701.46   209.5 2702.51   225.5 2707.38   249.5 2707.89   261.6 2709.63
   273.6 2706.39   301.6  2706.2   313.6  2704.3   317.6 2704.69   329.6 2709.03
   341.7 2710.52   357.9 2711.38   373.7 2708.08   381.7 2711.83   389.7 2718.49
   393.7 2720.06   469.8 2730.38   501.8 2739.81   537.9  2746.3   551.5 2749.96
#Mann= 3 ,-1,0
       0      .1       0  162.95    .045       0   209.5      .1       0
#XS Ineff= 2 , 0
                          260.83         2715.38
Permanent Ineff=
       F       F
Bank Sta=162.95,209.5
XS Rating Curve= 0 ,0
Exp/Cntr=0.3,0.1

Type RM Length L Ch R = 1 ,36556   ,264.5,258.6,255.4
XS GIS Cut Line= 2
2210607.84952095606818.9265346972211120.89952071606792.430994803
#Sta/Elev= 30
       0 2744.98    20.4 2740.87    32.4 2736.44    40.4 2736.18    56.4 2737.53
    76.4 2736.22   124.5 2726.84   131.5 2724.23   142.1 2717.74   164.5 2701.02
  174.62 2699.51   207.6 2698.36   215.3 2699.51   236.6 2705.18   244.7  2703.1
   272.7 2701.27   288.7 2708.86   300.7 2712.92   312.7 2715.72   333.3  2718.3
   360.8 2719.68   408.9 2718.96   417.1 2718.13   432.9 2714.43   456.9 2716.73
     481 2722.63     489 2722.44   496.9 2726.61   505.3 2733.68   513.7 2738.35
#Mann= 7 ,-1,0
       0      .1       0     170     .08       0  174.62    .045       0
   215.3     .08       0     270      .1       0     290     .08       0
     370      .1       0
#XS Ineff= 2 , 0
                          236.74         2711.18
Permanent Ineff=
       F       F
Bank Sta=174.62,215.3
XS Rating Curve= 0 ,0
Exp/Cntr(USF)=0,0
Exp/Cntr=0.3,0.1

Type RM Length L Ch R = 1 ,36297   ,274.8,268.2,264.1
XS GIS Cut Line= 2
2210695.71412892607109.1725988352211125.56923898606975.002039089
#Sta/Elev= 30
       0 2753.74      34 2743.57    42.4  2740.5    46.6 2737.86      61 2736.75
    71.7  2731.4    86.6 2727.44    92.7 2724.47    96.9 2721.49   117.8 2702.66
     122 2699.89   138.8 2695.45   159.7 2694.48   172.3  2695.5     189 2699.89
   205.8 2699.76   214.2 2701.52   222.6 2699.86   239.3 2700.62   256.1 2699.32
     277 2708.16   295.3 2714.37   310.1 2717.52   322.9 2718.74   360.9 2720.91
   381.8 2720.97   423.7 2719.18   436.3 2718.14   444.7 2716.02   450.3  2716.8
#Mann= 5 ,-1,0
       0      .1       0      90     .08       0   138.8    .045       0
   172.3     .08       0     190      .1       0
#XS Ineff= 2 , 0
                          214.25         2710.23
Permanent Ineff=
       F       F
Bank Sta=138.8,172.3
XS Rating Curve= 0 ,0
Exp/Cntr=0.3,0.1

Type RM Length L Ch R = 1 ,36029   ,243.9,240.4,234.9
XS GIS Cut Line= 2
2210828.76188075607386.1954323612211198.98575469607112.616344793
#Sta/Elev= 30
       0 2763.25    15.2 2759.75    34.6 2753.65    51.8  2749.4    66.1 2748.92
    71.8  2747.3    82.5 2741.89    95.9 2730.39   140.5 2697.44     149 2692.98
   153.5 2691.99   160.5 2692.39   193.2 2691.31   203.2 2691.55   205.5 2692.42
   210.4 2694.65   226.3 2696.68     233 2699.37   237.3 2700.25   243.4 2699.05
   257.9 2698.47   267.8 2696.72   292.7 2707.77   306.3 2712.64   332.5 2717.83
   347.4 2719.62   372.1 2720.57   389.3 2720.03   451.9 2709.79   460.3 2711.25
#Mann= 3 ,-1,0
       0      .1       0   160.5    .045       0   205.5      .1       0
Bank Sta=160.5,205.5
XS Rating Curve= 0 ,0
Exp/Cntr(USF)=0,0
Exp/Cntr=0.3,0.1

Type RM Length L Ch R = 1 ,35789   ,239.2,240.2,242.9
XS GIS Cut Line= 2
2211030.71676434 607572.621936152211279.18253517607287.236381356
#Sta/Elev= 30
       0 2760.63     6.3 2759.04    14.8 2752.68    17.6 2751.49    31.1 2750.81
    41.7 2744.71    57.6 2739.03    65.8 2735.15    73.5 2729.78    93.6 2713.29
   105.5 2701.38     114 2694.19   121.2  2690.9   137.2 2688.21   156.6 2686.98
   172.8  2687.4  175.94 2688.21   182.1 2691.21   190.6 2692.81   200.8  2696.8
   227.6  2692.6   233.7 2694.41     252 2702.72   264.4 2707.11   276.3 2710.32
   288.5 2712.07     319 2713.02   349.4 2711.91   360.7 2710.11   378.4 2705.01
#Mann= 3 ,-1,0
       0      .1       0   137.2    .045       0  175.94      .1       0
Bank Sta=137.2,175.94
XS Rating Curve= 0 ,0
Exp/Cntr=0.3,0.1

Type RM Length L Ch R = 1 ,35548   ,246.7,248.6,250.8
XS GIS Cut Line= 2
2211180.29520391607740.2506776152211584.41909522607361.551799335
#Sta/Elev= 30
       0 2756.97    10.6 2752.35    16.2 2747.99    33.2 2744.52    38.2    2742
    44.5 2736.91    55.9  2735.9    64.3 2732.49    98.1 2714.02   120.9 2693.06
   126.6 2688.71   132.3 2686.65   143.6 2685.38   174.7 2685.24   188.9 2686.73
   197.5 2691.26   208.1 2693.87   214.3 2692.26     241 2689.67   251.1 2690.93
   328.7 2692.83   403.9 2693.27   416.5 2692.26   435.1 2696.04   449.1 2701.87
   476.8 2718.36   498.7 2733.95   519.3 2752.14   537.1 2754.98   553.8 2767.61
#Mann= 3 ,-1,0
       0      .1       0   132.3    .045       0   188.9      .1       0
#XS Ineff= 2 , 0
                          208.25         2708.39
Permanent Ineff=
       F       F
Bank Sta=132.3,188.9
XS Rating Curve= 0 ,0
Exp/Cntr(USF)=0,0
Exp/Cntr=0.3,0.1

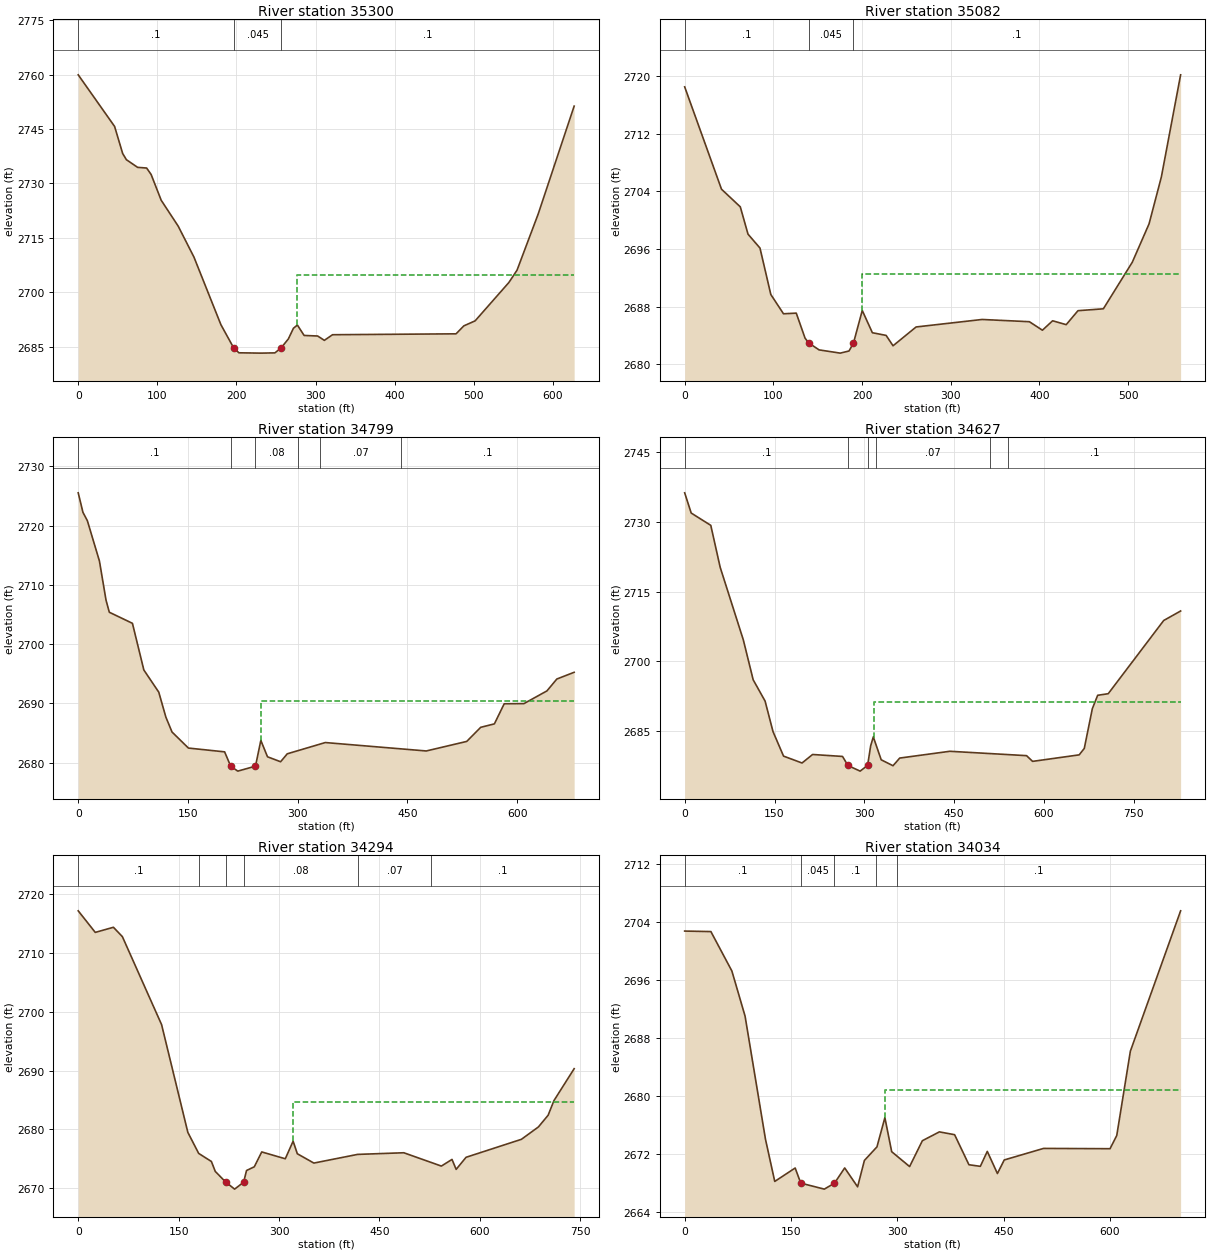
Type RM Length L Ch R = 1 ,35300   ,217.4,217.9,219.1
XS GIS Cut Line= 2
2211276.40162014607967.0814274952211764.32792491607573.333525255
#Sta/Elev= 30
       0 2759.95      46 2745.73    56.2 2738.27    60.9 2736.56    75.1 2734.45
    86.5 2734.26    92.2 2732.48   104.9 2725.39   126.4 2718.25   146.3 2709.73
   180.4 2691.09  196.53  2684.7   203.2 2683.34     231 2683.25   248.7 2683.32
   256.7 2684.74   265.7 2687.17   272.1  2690.1   277.1 2690.99   285.6 2688.12
   302.7 2687.97   311.2 2686.77   321.5 2688.32   477.7 2688.57   487.6 2690.77
   501.8 2692.14   544.5 2702.72   554.8 2706.11   581.5 2721.57     627 2751.33
#Mann= 3 ,-1,0
       0      .1       0  196.53    .045       0   256.7      .1       0
#XS Ineff= 2 , 0
                          276.99         2704.82
Permanent Ineff=
       F       F
Bank Sta=196.53,256.7
XS Rating Curve= 0 ,0
Exp/Cntr=0.3,0.1

Type RM Length L Ch R = 1 ,35082   ,280.4,283,285.7
XS GIS Cut Line= 2
 2211466.6679261608083.3634981422211917.67692915607752.953972094
#Sta/Elev= 30
       0 2718.49    41.5 2704.29    62.7 2701.84    71.4 2698.05    84.9 2696.12
    97.1 2689.68   111.4    2687   125.8 2687.09   135.7 2683.62  139.88 2682.95
   151.5 2681.99   175.4 2681.54   185.3 2681.84   190.3 2682.94   200.2 2687.46
   211.6 2684.37   227.1    2684   234.9 2682.56   260.9 2685.17   335.3 2686.21
   388.6  2685.9   403.3 2684.72   414.8 2686.03   430.1 2685.49   443.4 2687.43
     472 2687.69   504.6 2694.15   523.5 2699.47   537.4 2705.99   559.1 2720.16
#Mann= 3 ,-1,0
       0      .1       0  139.88    .045       0   190.3      .1       0
#XS Ineff= 2 , 0
                          200.28         2692.57
Permanent Ineff=
       F       F
Bank Sta=139.88,190.3
XS Rating Curve= 0 ,0
Exp/Cntr(USF)=0,0
Exp/Cntr=0.3,0.1

Type RM Length L Ch R = 1 ,34799   ,171.8,172.4,173.3
XS GIS Cut Line= 3
2211566.38875159608316.1987538142211914.01980953608136.555692267
     2212169.343      608006.621
#Sta/Elev= 30
       0 2725.52     6.5 2722.22    12.5 2720.82      29 2714.02      38 2707.43
    42.5 2705.38    74.1 2703.51    89.7 2695.64   110.1  2691.9   119.8 2687.69
   128.2 2685.18   150.6 2682.47   200.1 2681.83   208.4 2679.41   218.1 2678.58
  242.28 2679.42   249.6 2683.76   258.7    2681   276.6 2680.16   285.7  2681.5
   337.7  2683.4   475.7 2681.98     531 2683.59   550.1 2685.97   568.8 2686.55
   582.2 2689.94   609.2 2689.97   640.6 2692.11   654.2 2694.12   677.8 2695.25
#Mann= 6 ,-1,0
       0      .1       0   208.4    .045       0  242.28     .08       0
     300      .1       0     330     .07       0   441.3      .1       0
#XS Ineff= 2 , 0
                          249.69         2690.43
Permanent Ineff=
       F       F
Bank Sta=208.4,242.28
XS Rating Curve= 0 ,0
Exp/Cntr=0.3,0.1

Type RM Length L Ch R = 1 ,34627   ,321.4,333.1,314
XS GIS Cut Line= 2
2211570.32113614608493.2378245552212321.92020552608145.301725197
#Sta/Elev= 30
       0 2736.26    10.9 2731.91    43.6 2729.26    59.3 2720.23    97.9 2704.63
   114.4 2696.02   134.3 2691.44   147.5 2684.88   165.1  2679.6     196 2678.12
   213.6 2679.95   263.6 2679.53  272.632677.584     293 2676.37  305.49 2677.61
   310.6 2681.82     315 2683.73   328.2 2678.81   347.9 2677.53   359.1 2679.18
   442.8 2680.64   570.9  2679.7     581 2678.47   658.8 2679.87   667.3 2681.25
   680.8 2689.82   689.7 2692.69   707.3 2693.03   799.9 2708.78   828.2 2710.83
#Mann= 6 ,-1,0
       0      .1       0  272.63    .045       0  305.49      .1       0
     320     .07       0     510     .08       0     540      .1       0
#XS Ineff= 2 , 0
                          315.43         2691.28
Permanent Ineff=
       F       F
Bank Sta=272.63,305.49
XS Rating Curve= 0 ,0
Exp/Cntr(USF)=0,0
Exp/Cntr=0.3,0.1

Type RM Length L Ch R = 1 ,34294   ,259,259.9,264.2
XS GIS Cut Line= 3
2211734.19599838608778.8253191312211941.75166612608580.027783956
2212351.33574959608385.117166937
#Sta/Elev= 30
       0 2717.09    25.5 2713.43    52.6  2714.3      66 2712.71   124.6 2697.78
   163.8 2679.51     180 2675.94     199 2674.57   204.8 2672.88   220.4 2671.08
   233.7 2669.88  247.17 2671.06   251.5 2673.04   263.1 2673.67   274.2 2676.19
   309.4 2675.03   321.1 2678.01   327.4 2675.88   352.1  2674.3   417.4 2675.77
   486.5 2676.05   542.6 2673.79   558.5 2674.92   564.7 2673.23   579.5 2675.28
   662.2 2678.33   687.6 2680.43   702.1 2682.41   710.9 2684.91     741 2690.31
#Mann= 6 ,-1,0
       0      .1       0     180     .08       0   220.4    .045       0
  247.17     .08       0   417.4     .07       0   527.4      .1       0
#XS Ineff= 2 , 0
                          321.09         2684.72
Permanent Ineff=
       F       F
Bank Sta=220.4,247.17
XS Rating Curve= 0 ,0
Exp/Cntr=0.3,0.1

Type RM Length L Ch R = 1 ,34034   ,243.5,247.5,244.7
XS GIS Cut Line= 2
2211909.38235178608922.7018286022212491.07988672608533.699129252
#Sta/Elev= 30
       0 2702.75      37 2702.68    66.6 2697.25    85.2 2691.04     114 2674.07
   127.1 2668.25   155.9  2670.1   163.8 2668.02     197 2667.19   211.4 2668.01
   225.8 2670.11     244 2667.51   253.6 2671.14   271.3 2673.01   282.5 2677.04
   292.1 2672.35   317.4  2670.3   335.4 2673.86   359.4 2675.08   380.9 2674.69
   401.1 2670.55   417.2 2670.33     427 2672.39   441.3 2669.34   450.9 2671.21
   506.4  2672.8   600.2 2672.76   609.7 2674.58   628.9  2686.2   699.8 2705.54
#Mann= 5 ,-1,0
       0      .1       0   163.8    .045       0   211.4      .1       0
     270     .08       0     300      .1       0
#XS Ineff= 2 , 0
                          282.53         2680.85
Permanent Ineff=
       F       F
Bank Sta=163.8,211.4
XS Rating Curve= 0 ,0
Exp/Cntr(USF)=0,0
Exp/Cntr=0.3,0.1

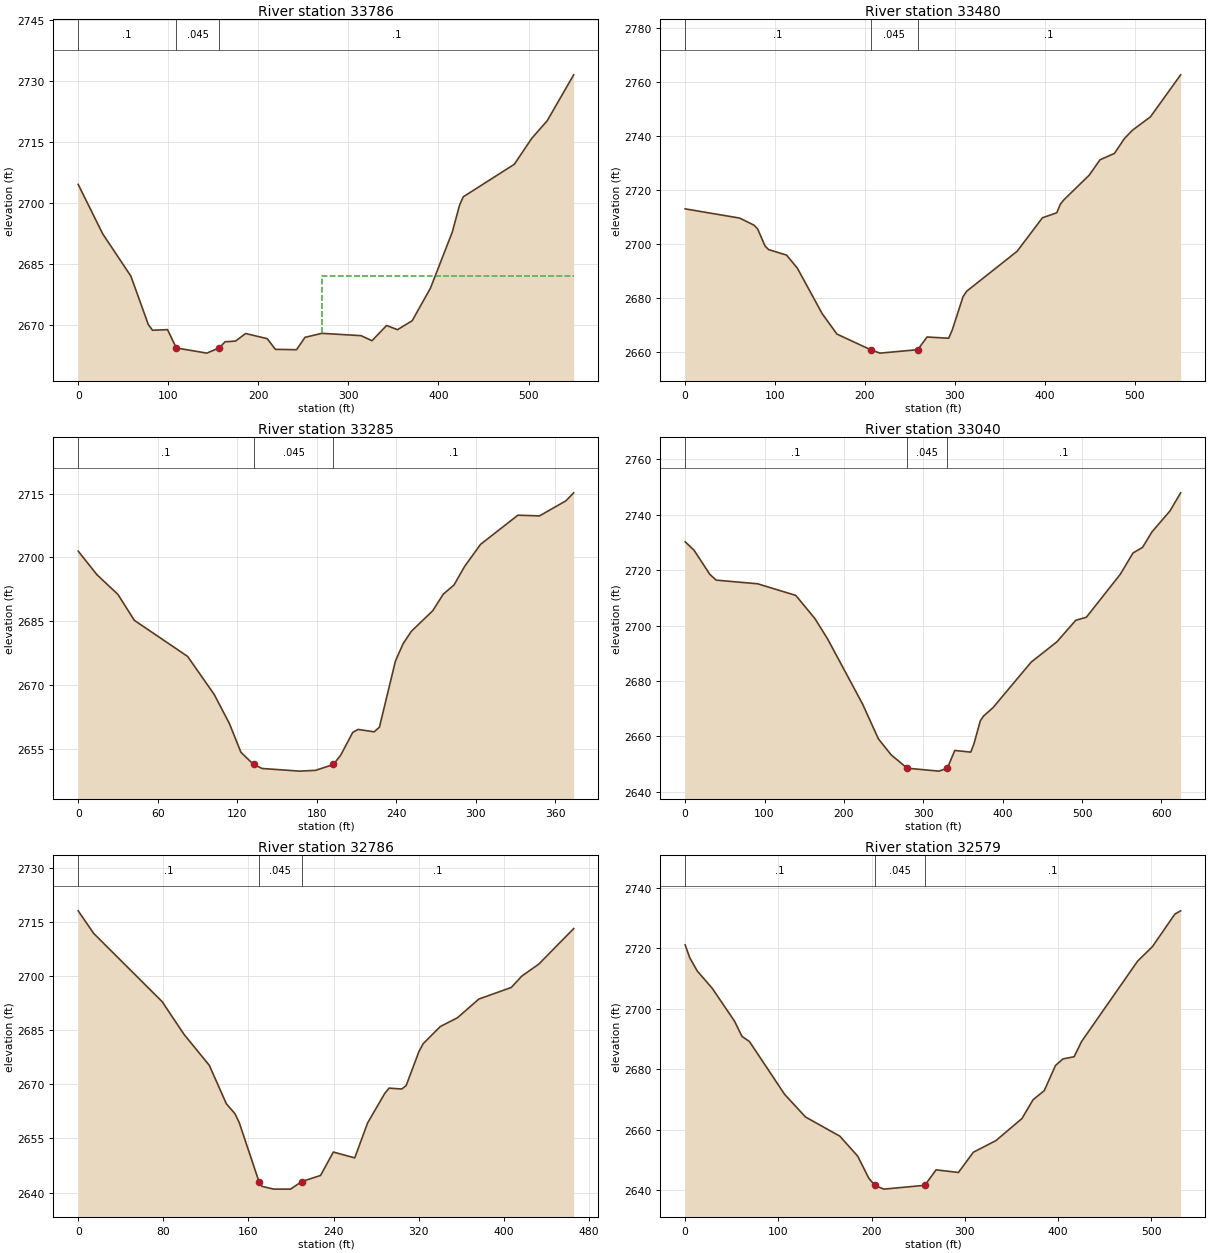
Type RM Length L Ch R = 1 ,33786   ,287.6,305.7,318.2
XS GIS Cut Line= 3
 2212025.9985279609119.496400424 2212274.1800273608966.132848764
2212529.17209993608924.805900777
#Sta/Elev= 30
       0  2704.6    27.2 2692.47    58.5 2682.07    77.8 2670.21    82.5 2668.78
    99.2 2668.93  108.93 2664.43   142.8 2663.16   156.6 2664.45   163.1 2665.95
   174.7 2666.12   185.9 2667.98   209.9 2666.71   218.9 2664.09   242.4    2664
   251.8 2667.04   270.6 2668.02     314 2667.45   326.2 2666.21   342.4 2669.95
   354.5 2668.92   370.8 2671.12     391 2679.08   415.3 2692.87   423.4 2699.49
   427.5 2701.55   484.2 2709.54   503.5  2715.9   520.7 2720.23   550.1 2731.51
#Mann= 3 ,-1,0
       0      .1       0  108.93    .045       0   156.6      .1       0
#XS Ineff= 2 , 0
                          270.66         2682.21
Permanent Ineff=
       F       F
Bank Sta=108.93,156.6
XS Rating Curve= 0 ,0
Exp/Cntr=0.3,0.1

Type RM Length L Ch R = 1 ,33480   ,193.7,195.6,195.5
XS GIS Cut Line= 2
 2211951.6005171 609291.243577622212501.73237797609325.936577855
#Sta/Elev= 30
       0 2712.93    60.7 2709.51    76.7 2706.87    80.7 2705.47    88.8 2699.21
    92.8 2697.83   112.8 2695.79   124.8 2690.97   152.5 2674.04   168.9 2666.49
  206.58 2660.67   216.7 2659.44   258.7 2660.71   269.1 2665.42   293.2 2664.96
   297.2 2668.09   309.2 2680.41   313.2  2682.4   369.3  2697.2   397.4 2709.61
   413.4 2711.49   417.4 2714.68   421.4 2716.32   449.5 2725.43   461.5 2731.13
   477.5 2733.48   488.7 2739.02   497.6  2742.1   517.6 2747.05   551.2 2762.63
#Mann= 3 ,-1,0
       0      .1       0  206.58    .045       0   258.7      .1       0
Bank Sta=206.58,258.7
XS Rating Curve= 0 ,0
Exp/Cntr(USF)=0,0
Exp/Cntr=0.3,0.1

Type RM Length L Ch R = 1 ,33285   ,245.6,244.7,243.2
XS GIS Cut Line= 2
2211998.00373931609482.5069788572212370.01151399609519.745077454
#Sta/Elev= 30
       0 2701.49    14.2 2695.93      30 2691.31    42.4 2685.21    82.6 2676.73
   102.7 2667.76   114.1 2660.96   122.8 2654.21   132.3 2651.34   138.9 2650.39
     167 2649.77   179.1 2649.95  192.58 2651.33   198.1 2653.53   207.2 2658.88
   211.2 2659.57   223.3 2659.01   227.3 2660.09   239.4 2675.65   245.1 2679.67
   251.4 2682.64   267.5 2687.46   275.5 2691.37   283.6 2693.53   291.6  2697.9
   303.7  2703.1   331.8 2709.93   348.1 2709.77     368  2713.3   373.9 2715.19
#Mann= 3 ,-1,0
       0      .1       0   132.3    .045       0  192.58      .1       0
Bank Sta=132.3,192.58
XS Rating Curve= 0 ,0
Exp/Cntr=0.3,0.1

Type RM Length L Ch R = 1 ,33040   ,253,254.1,255.3
XS GIS Cut Line= 2
2211849.17356402609722.4280091122212471.99552062609763.729199869
#Sta/Elev= 30
       0 2730.26      11 2727.31    31.1 2718.52    39.1 2716.43    91.2 2715.12
   139.3 2710.93   163.3 2702.64   179.4 2695.24   223.5 2671.73   243.5 2659.12
   259.6 2653.37   279.8 2648.55   319.7  2647.5  330.28 2648.55   339.7 2654.97
   359.8 2654.36   363.8 2657.34   371.8 2665.61   375.8 2667.34   387.9 2670.43
     436 2686.87   468.3 2694.16   492.1 2701.94   505.4 2703.03   548.2 2718.56
   564.2 2726.23   576.3 2728.28   588.1 2733.86   610.7 2741.38   624.2 2747.94
#Mann= 3 ,-1,0
       0      .1       0   279.8    .045       0  330.28      .1       0
Bank Sta=279.8,330.28
XS Rating Curve= 0 ,0
Exp/Cntr(USF)=0,0
Exp/Cntr=0.3,0.1

Type RM Length L Ch R = 1 ,32786   ,208.4,207,206.7
XS GIS Cut Line= 2
2211929.60548601609975.0626478962212392.89047896610020.558654944
#Sta/Elev= 30
       0 2718.21    14.6 2711.93    78.9 2692.99    99.4 2683.92   123.2 2675.31
   139.2 2664.64   147.3 2661.87   151.3 2659.42   169.9 2642.98   172.6 2641.73
   183.6 2640.94   199.5 2640.94     210 2643.04   227.7 2644.74   239.7 2651.24
   259.8 2649.61   271.9 2659.32   287.9 2667.46     292 2668.98     304 2668.74
   308.1 2669.69   320.1  2679.1   324.1 2681.32   340.2 2686.09   356.3 2688.52
   376.4 2693.71   406.9 2696.94   416.6 2700.05   432.8 2703.43   465.5 2713.28
#Mann= 3 ,-1,0
       0      .1       0   169.9    .045       0     210      .1       0
Bank Sta=169.9,210
XS Rating Curve= 0 ,0
Exp/Cntr=0.3,0.1

Type RM Length L Ch R = 1 ,32579   ,286.1,284,282.6
XS GIS Cut Line= 2
 2211883.2175632610190.9004855712212414.33270379610213.782997297
#Sta/Elev= 30
       0 2721.17       5 2716.88      13 2712.51      29 2706.82      53 2695.91
      61 2690.89      69 2689.18   106.7 2671.72   129.1 2664.23     166 2657.87
   185.1 2651.28   197.1 2643.95   203.6 2641.58   213.2 2640.36   257.2 2641.63
   269.2 2646.74   293.2 2645.87   309.2 2652.57   333.3 2656.39   361.3 2663.69
   373.3 2669.94   385.3 2672.95   397.3 2681.25   405.3 2683.43   417.3 2684.15
   425.4 2689.23   485.4 2715.77   501.4  2720.6   525.4 2731.34   531.6 2732.42
#Mann= 3 ,-1,0
       0      .1       0   203.6    .045       0   257.2      .1       0
Bank Sta=203.6,257.2
XS Rating Curve= 0 ,0
Exp/Cntr(USF)=0,0
Exp/Cntr=0.3,0.1

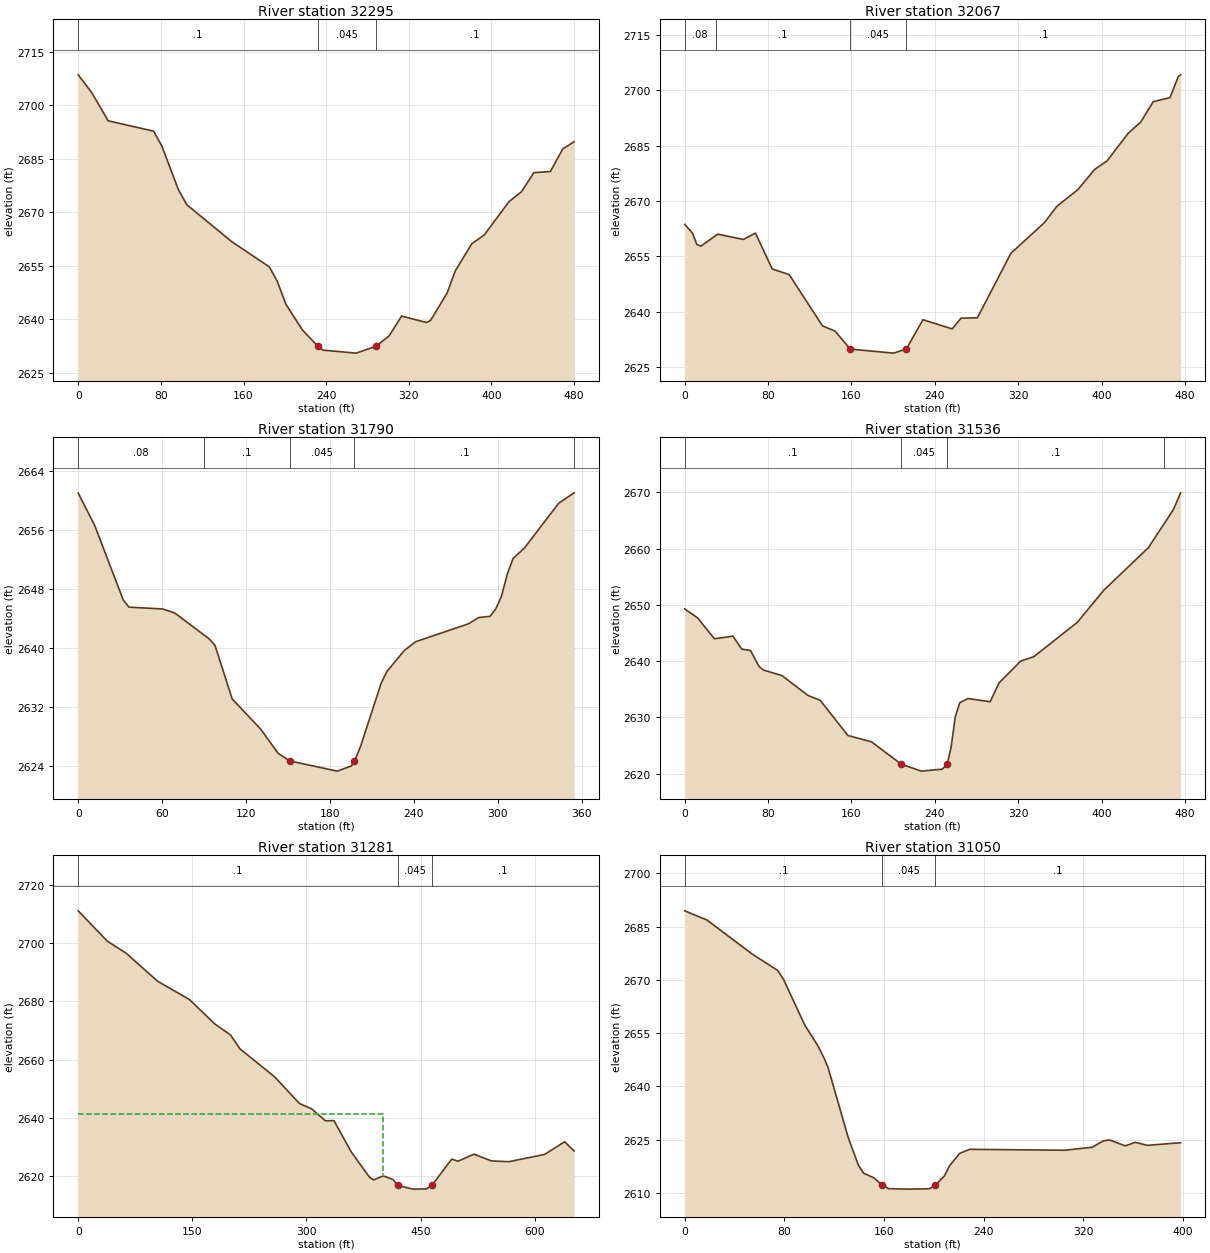
Type RM Length L Ch R = 1 ,32295   ,228.8,228.2,224.9
XS GIS Cut Line= 2
2211831.20839773610488.0381833062212311.15756954610479.897916531
#Sta/Elev= 30
       0 2708.51      13 2703.57      29 2695.62      73 2692.72      81  2688.5
      97 2676.31     105 2672.12   148.6 2661.74     185 2654.67   192.6 2650.68
     201 2644.21     217 2636.98   231.9 2632.43     237 2631.32     269 2630.49
  288.14  2632.4     301 2635.34     313 2640.88     337 2639.08     341 2639.64
     357 2647.31     365 2653.58     381 2661.18     393 2663.62     417 2672.98
     429 2675.72     441 2681.09     457  2681.4     469 2687.75     480 2689.75
#Mann= 3 ,-1,0
       0      .1       0   231.9    .045       0  288.14      .1       0
Bank Sta=231.9,288.14
XS Rating Curve= 0 ,0
Exp/Cntr=0.3,0.1

Type RM Length L Ch R = 1 ,32067   ,276.5,276.7,271.4
XS GIS Cut Line= 2
2211936.60290721610723.0150252452212410.27089995610677.490870337
#Sta/Elev= 30
       0 2663.68     7.6 2661.26    11.6 2658.25    15.6 2657.78    31.7 2661.02
    56.3 2659.58    67.9  2661.3      84 2651.58   100.3 2650.07   132.2 2636.18
   144.3 2634.77   158.9 2629.89   200.5  2628.8  212.76 2629.92   228.6 2637.85
   256.7 2635.36   265.2 2638.27   280.9 2638.37     313 2655.82   345.2 2664.14
   357.2 2668.57   377.3 2673.07   393.4 2678.54   405.4 2680.87   425.5  2688.3
   437.6 2691.37   449.6 2696.88   465.7    2698   473.7 2703.71   475.9 2704.16
#Mann= 4 ,-1,0
       0     .08       0      30      .1       0   158.9    .045       0
  212.76      .1       0
Bank Sta=158.9,212.76
XS Rating Curve= 0 ,0
Exp/Cntr(USF)=0,0
Exp/Cntr=0.3,0.1

Type RM Length L Ch R = 1 ,31790   ,253,254.3,249.2
XS GIS Cut Line= 2
 2211968.6935303611014.6839181562212314.85248119610937.834517181
#Sta/Elev= 30
       0 2661.02    11.8 2656.62    32.2 2646.54    36.3 2645.56    60.5 2645.31
    69.1 2644.76    93.7 2641.25    97.8 2640.38   110.1 2633.12   130.6    2629
   142.9 2625.76  151.22 2624.72   185.2 2623.34   195.3 2624.04   197.5  2624.7
     202 2626.75   216.6 2635.25   220.7 2636.83     233 2639.66   241.2 2640.87
   279.1 2643.31   286.3 2644.15   294.5 2644.32   298.6 2645.34   302.6 2647.02
   306.8 2650.05   310.9 2652.14   319.1 2653.58   343.6 2659.65   354.6 2661.05
#Mann= 5 ,-1,0
       0     .08       0      90      .1       0  151.22    .045       0
   197.5      .1       0  354.59     .08       0
Bank Sta=151.22,197.5
XS Rating Curve= 0 ,0
Exp/Cntr=0.3,0.1

Type RM Length L Ch R = 1 ,31536   ,253.9,254.4,255
XS GIS Cut Line= 2
 2212023.8586733611268.4601276822212478.83259067611129.291635311
#Sta/Elev= 30
       0 2649.28    12.5 2647.66    28.5 2643.96    46.3 2644.44    54.7 2642.14
    63.1 2641.89    71.4 2639.04    75.6 2638.41    93.3 2637.43   118.2 2633.91
     130 2633.03   156.6 2626.78   179.1 2625.67   207.9 2621.67   227.1 2620.45
   247.1  2620.8  251.79 2621.65   255.5 2624.59   259.7 2630.18   263.9  2632.6
   271.9 2633.35   293.1 2632.78   301.5 2636.11   322.4 2640.01     335 2640.79
   376.8 2646.91   401.9 2652.56   444.9 2660.16   468.8  2666.9   475.8  2669.9
#Mann= 4 ,-1,0
       0      .1       0   207.9    .045       0  251.79      .1       0
     460     .08       0
Bank Sta=207.9,251.79
XS Rating Curve= 0 ,0
Exp/Cntr(USF)=0,0
Exp/Cntr=0.3,0.1

Type RM Length L Ch R = 1 ,31281   ,247.1,231.9,196.9
XS GIS Cut Line= 3
     2211895.412      611562.7122212399.48316456611421.603523697
2212482.44937415611323.688710627
#Sta/Elev= 30
       0 2711.09    38.2 2700.68    63.1 2696.51   104.6 2686.85   146.2 2680.62
   179.4 2672.24   200.2 2668.45   212.6 2663.66   258.3 2654.02   290.7 2644.91
   306.9 2643.06   324.8 2638.95   336.1    2639   358.8 2628.27   382.9 2619.54
   388.1 2618.64     401 2620.02     414 2618.75  419.63 2616.78     440 2615.47
   457.7 2615.55  464.86 2616.78   490.9 2625.78   499.2 2625.05     520 2627.48
   543.1 2625.17   565.9 2624.89   613.1 2627.41   639.3 2631.74   651.8 2628.57
#Mann= 3 ,-1,0
       0      .1       0  419.63    .045       0  464.86      .1       0
#XS Ineff= 2 , 0
          400.45 2641.31
Permanent Ineff=
       F       F
Bank Sta=419.63,464.86
XS Rating Curve= 0 ,0
Exp/Cntr=0.3,0.1

Type RM Length L Ch R = 1 ,31050   ,263.7,263.1,258.3
XS GIS Cut Line= 3
2212434.34478359611762.7380937832212478.38102038611504.695743546
2212535.30875671611380.711257332
#Sta/Elev= 30
       0 2689.47    17.8  2686.9    54.3 2677.27    74.6 2672.69    79.2 2670.25
    96.5 2657.22   107.1 2651.36   112.2 2647.75   115.2  2645.2   131.4 2625.47
   139.5 2617.77   143.6 2615.54   151.7 2614.24   158.5 2612.19   163.9 2611.16
   180.1 2611.03   196.4 2611.13   201.1 2612.12   208.5 2614.71   212.6 2617.58
   220.7 2621.09   228.8 2622.25   305.3 2621.99   327.3 2622.84   336.1 2624.63
   341.2  2624.9   353.7 2623.22   361.9 2624.22   371.5 2623.37   398.2 2624.11
#Mann= 3 ,-1,0
       0      .1       0   158.5    .045       0   201.1      .1       0
Bank Sta=158.5,201.1
XS Rating Curve= 0 ,0
Exp/Cntr(USF)=0,0
Exp/Cntr=0.3,0.1