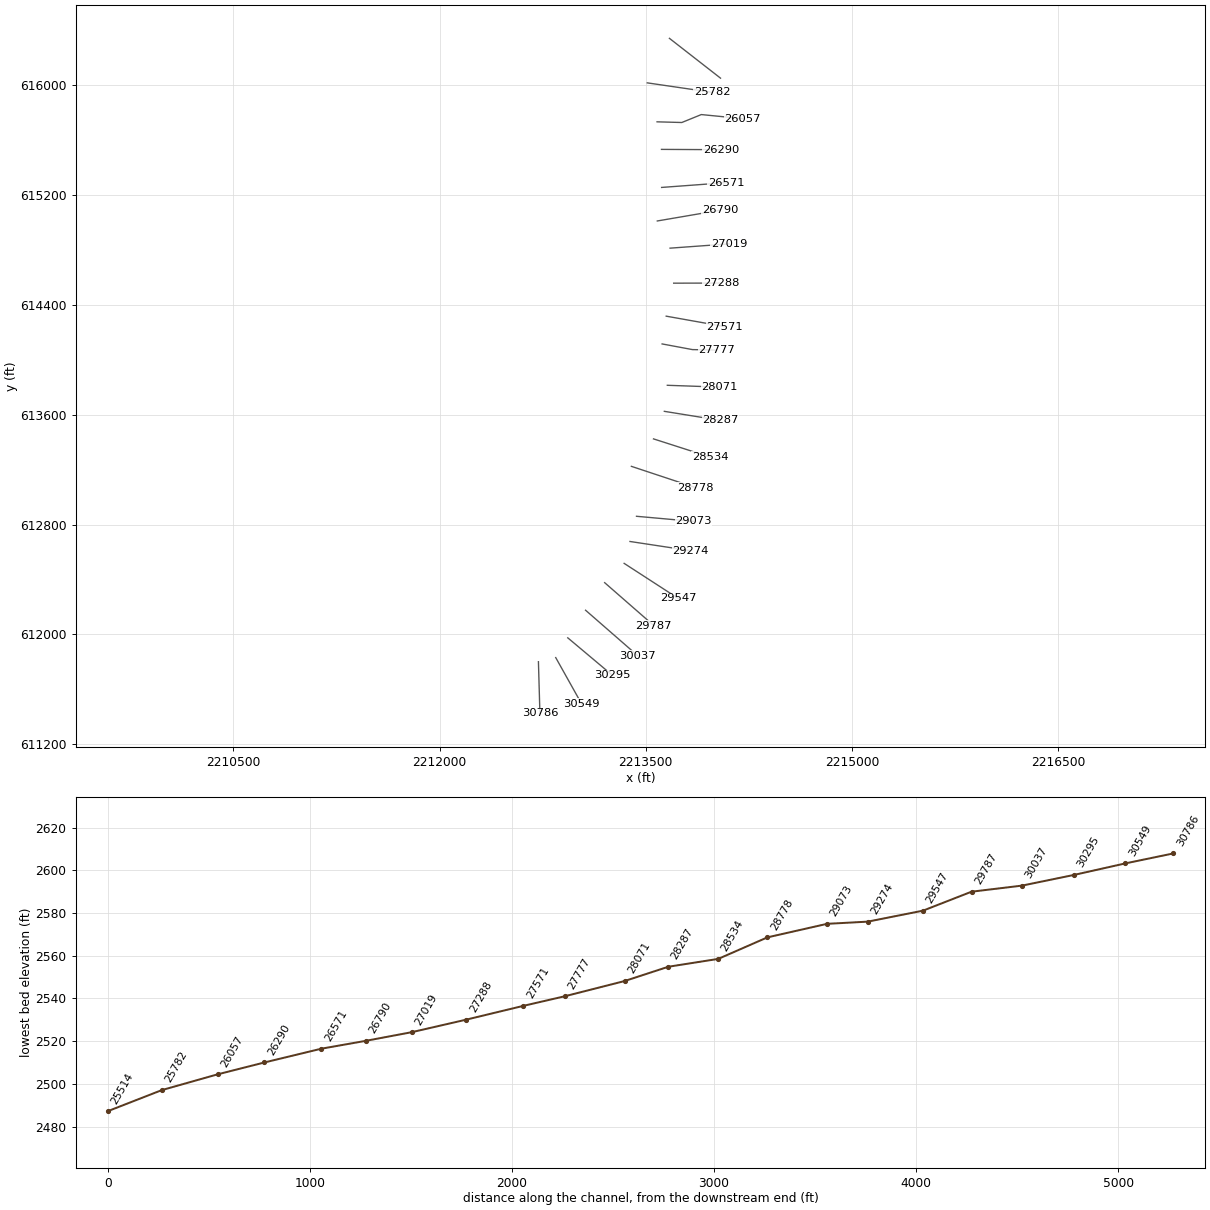
HEC-RAS study LFBUCKRV.prj: LFBUCKRV

--- LFBUCKRV.g01 (geometry) --- (continued)

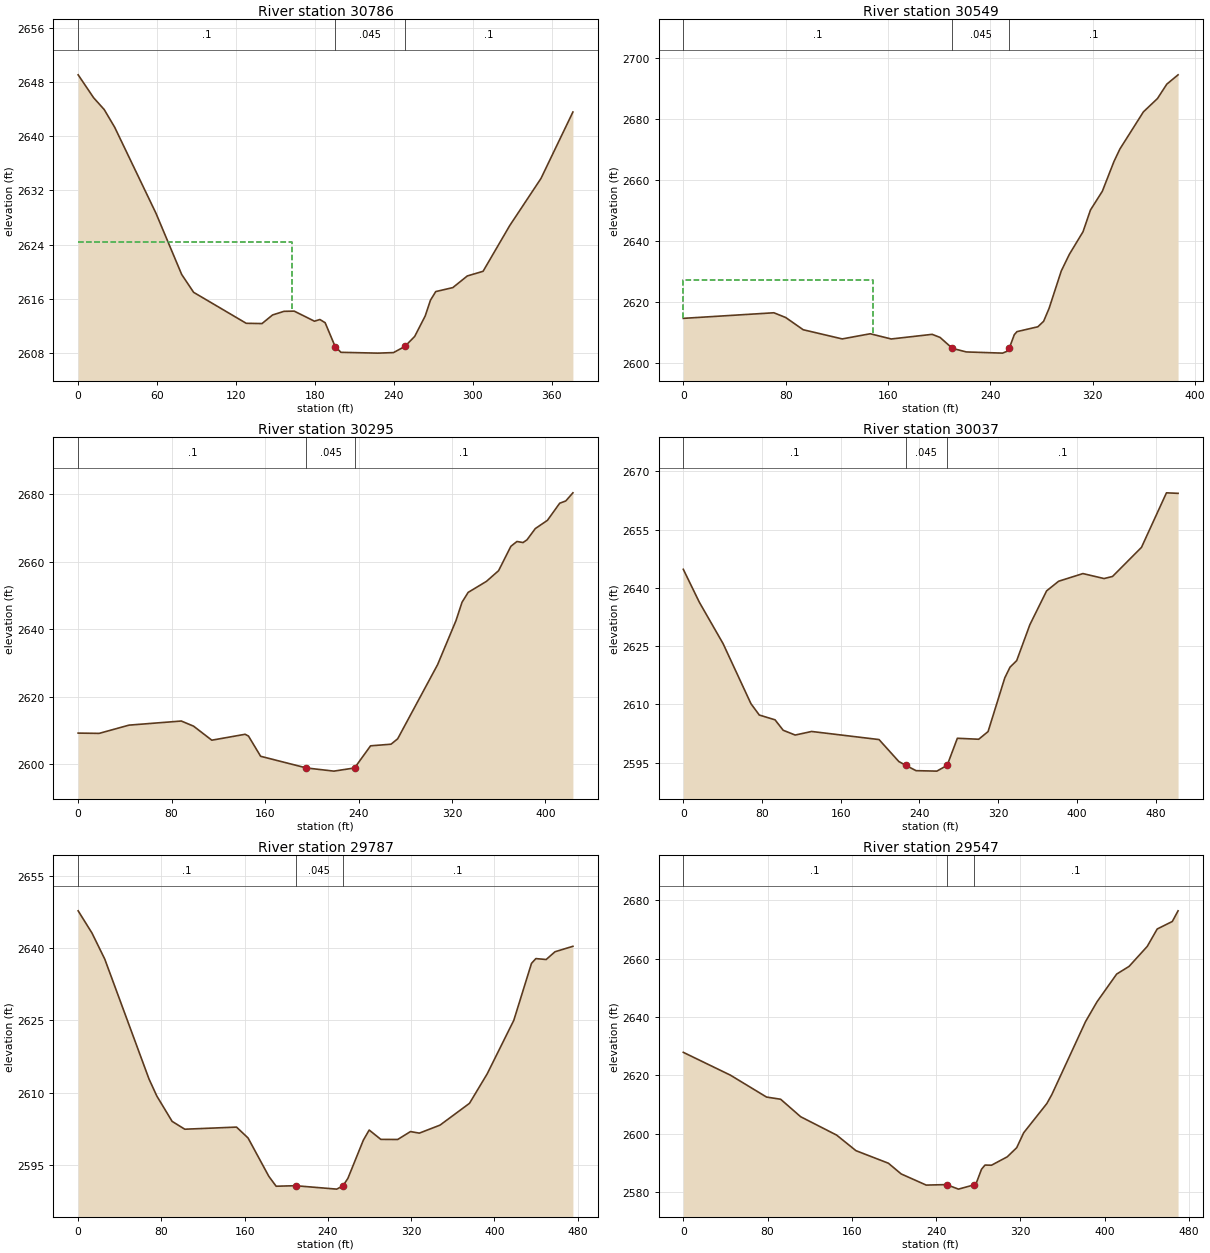
Type RM Length L Ch R = 1 ,30786   ,230.1,237.8,252.9
XS GIS Cut Line= 2
2212719.03448566611800.9267876162212729.79752779611424.851231158
#Sta/Elev= 30
       0  2649.1    11.8  2645.7    19.8 2643.97    27.8 2641.34    59.2 2628.62
    78.7 2619.59    87.8 2616.94   127.8 2612.36   139.8 2612.32   147.8 2613.59
   156.5 2614.13   164.3 2614.16   179.7 2612.67   183.8 2612.92   187.8 2612.45
   195.4 2608.93   199.8 2608.07   227.8 2607.95   239.8 2608.03  248.44 2608.94
   255.9 2610.42   263.9 2613.45   267.9 2615.78   271.9 2617.05   284.9 2617.64
   295.9 2619.36   307.9 2620.05   328.1 2626.79   351.9 2633.77   376.2  2643.6
#Mann= 3 ,-1,0
       0      .1       0   195.4    .045       0  248.44      .1       0
#XS Ineff= 2 , 0
           162.8 2624.31
Permanent Ineff=
       F       F
Bank Sta=195.4,248.44
XS Rating Curve= 0 ,0
Exp/Cntr=0.3,0.1

Type RM Length L Ch R = 1 ,30549   ,247.2,253.2,263.7
XS GIS Cut Line= 2
2212844.86072053 611830.960356312213033.68976467611493.447025451
#Sta/Elev= 30
       0 2614.67    70.8  2616.5      80 2614.95    93.7 2610.94   124.2 2607.93
   146.1 2609.62   162.5 2607.91   194.5 2609.43   200.7 2608.41  210.29 2604.83
   221.2 2603.66   249.5 2603.27   253.6 2603.97  254.71 2604.83   258.7 2609.32
   260.8 2610.32   277.1 2611.91   281.6  2613.7   285.9 2617.96   295.4  2630.2
   301.7 2635.64   312.4 2643.06   318.2 2650.17   327.5 2656.34   336.6  2666.1
   341.2 2670.17   359.6 2682.37   370.6 2686.74   377.9 2691.46   386.7 2694.51
#Mann= 3 ,-1,0
       0      .1       0  210.29    .045       0  254.71      .1       0
#XS Ineff= 2 , 0
          148.33 2627.14
Permanent Ineff=
       F       F
Bank Sta=210.29,254.71
XS Rating Curve= 0 ,0
Exp/Cntr(USF)=0,0
Exp/Cntr=0.3,0.1

Type RM Length L Ch R = 1 ,30295   ,255.9,258.3,255.5
XS GIS Cut Line= 2
2212932.54189714611974.8487632412213256.80443305611702.511505403
#Sta/Elev= 30
       0 2609.16      18 2609.08    43.5 2611.52    88.3 2612.74    98.8 2611.22
   114.4 2607.06   142.9 2608.81   145.8 2608.28   156.2 2602.29   195.4 2598.83
   218.9 2597.89   236.6 2598.83   250.3 2605.39   267.8 2605.87   273.5 2607.47
   307.7 2629.47   323.4 2642.49   328.6 2647.95   333.8 2650.86   349.5 2654.14
   359.9 2657.31   370.4 2664.53   375.6 2665.96   380.8 2665.64   384.2 2666.45
   391.3 2669.78   401.7 2672.23   412.2  2677.3   417.4 2677.97   423.5 2680.38
#Mann= 3 ,-1,0
       0      .1       0   195.4    .045       0   236.6      .1       0
Bank Sta=195.4,236.6
XS Rating Curve= 0 ,0
Exp/Cntr=0.3,0.1

Type RM Length L Ch R = 1 ,30037   ,249.2,249.7,248.6
XS GIS Cut Line= 2
2213061.93977914612175.9079015042213440.86755049611845.404105208
#Sta/Elev= 30
       0 2644.76    16.3 2636.29    40.4 2625.66    68.7 2610.22    77.2 2607.29
    93.2 2606.06   101.5 2603.37   113.7 2602.14   130.4 2603.06   198.9 2600.98
     219 2595.33   225.9 2594.37   236.5 2592.98   257.7 2592.86  268.13 2594.35
   278.5 2601.31   300.2 2601.06   309.7 2603.03   326.7 2616.85     332 2619.59
   338.8 2621.29   352.2 2630.53   369.2 2639.22   381.4  2641.7   406.1 2643.67
   427.6 2642.39   436.2 2642.93   465.6 2650.41     491 2664.44   502.8 2664.31
#Mann= 3 ,-1,0
       0      .1       0   225.9    .045       0  268.13      .1       0
Bank Sta=225.9,268.13
XS Rating Curve= 0 ,0
Exp/Cntr(USF)=0,0
Exp/Cntr=0.3,0.1

Type RM Length L Ch R = 1 ,29787   ,242.4,240,241.9
XS GIS Cut Line= 2
2213200.87418679 612376.582498942213558.95067267612063.790970339
#Sta/Elev= 30
       0 2647.75    13.3 2643.14    25.6 2637.72    68.1 2612.86    75.6 2609.33
    90.3 2604.07   102.5 2602.44   152.2 2602.88   163.3 2600.62   183.3 2592.65
   190.3 2590.61   208.9 2590.72   248.5 2590.01   254.5 2590.68   259.3 2592.27
   274.1 2600.17   279.7 2602.27   290.9 2600.33   307.1 2600.31   319.4 2601.95
   327.9 2601.63   347.8 2603.29   376.1 2607.81   393.1 2613.92   418.7 2625.04
   435.7 2636.85   439.9 2637.84   449.8 2637.65   458.3 2639.26   475.5 2640.39
#Mann= 3 ,-1,0
       0      .1       0   208.9    .045       0   254.5      .1       0
Bank Sta=208.9,254.5
XS Rating Curve= 0 ,0
Exp/Cntr=0.3,0.1

Type RM Length L Ch R = 1 ,29547   ,270.5,273.3,281.3
XS GIS Cut Line= 2
2213342.66820639612517.0023956792213736.77731888612261.416783122
#Sta/Elev= 30
       0 2627.91    44.7 2620.11      79 2612.62    92.4 2611.87   111.4 2605.89
   145.6  2599.6   163.9 2594.28   194.7 2589.99   206.8 2586.33   230.6 2582.51
   249.9 2582.68   261.2 2581.13   275.7 2582.56   278.3 2583.36   283.1 2587.92
   286.4 2589.36   292.6 2589.31   307.5 2592.17   316.5  2595.3   323.1 2600.39
   345.1 2610.39   349.8 2613.43   381.9 2638.45   392.7 2645.17   411.4 2654.68
   423.2 2657.31   440.4 2664.13   449.9  2670.1   464.2 2672.66   469.7 2676.31
#Mann= 3 ,-1,0
       0      .1       0   249.9    .045       0   275.7      .1       0
Bank Sta=249.9,275.7
XS Rating Curve= 0 ,0
Exp/Cntr(USF)=0,0
Exp/Cntr=0.3,0.1

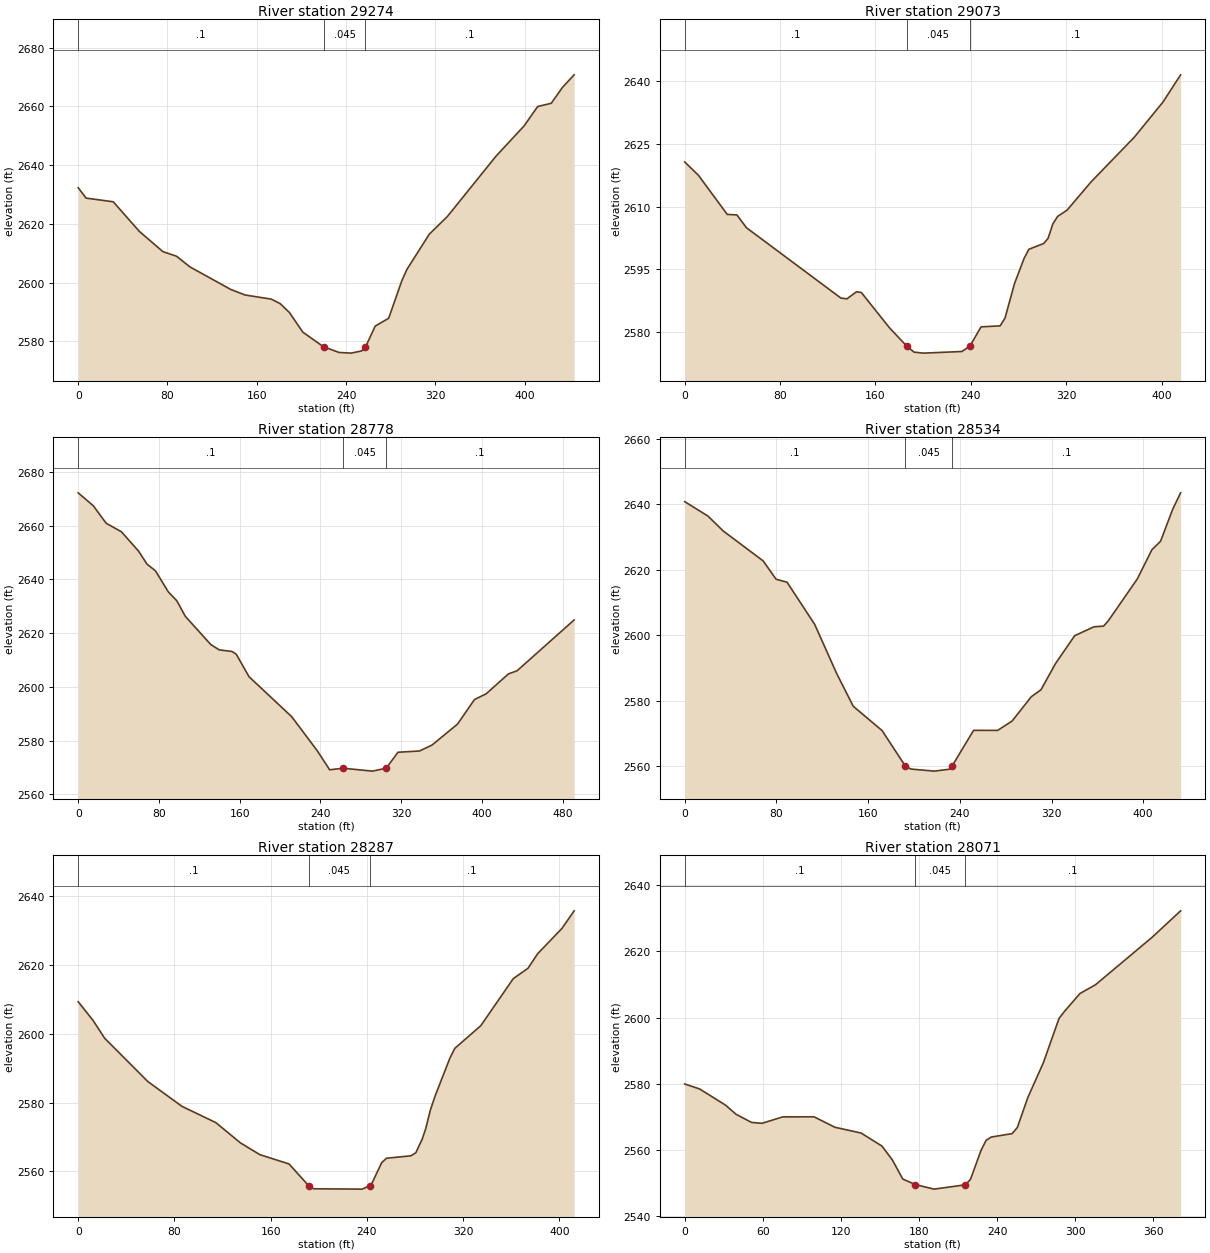
Type RM Length L Ch R = 1 ,29274   ,200.4,201.2,203.1
XS GIS Cut Line= 2
2213385.11748295612676.4225112292213824.45393125612609.689915996
#Sta/Elev= 30
       0 2632.27     7.1 2628.75    31.4  2627.5    54.7 2617.46    75.9 2610.53
    88.1 2608.97   100.2 2605.32   136.6 2597.68   149.5 2595.78     173 2594.37
   181.1  2592.8   189.2 2589.83   201.3 2583.12   219.8 2578.16   233.7 2576.22
   244.4 2575.99   253.9 2576.73   257.4 2578.03   266.1 2585.18   278.2 2587.86
     290 2600.64   294.4 2604.39   314.6 2616.47   330.8 2622.49   374.3 2642.99
   399.6 2653.35   411.7 2659.92   423.9 2661.03     434 2666.47   444.4 2670.71
#Mann= 3 ,-1,0
       0      .1       0   219.8    .045       0   257.4      .1       0
Bank Sta=219.8,257.4
XS Rating Curve= 0 ,0
Exp/Cntr=0.3,0.1

Type RM Length L Ch R = 1 ,29073   ,299.9,295.3,290.5
XS GIS Cut Line= 2
2213432.59394311612859.9018054422213846.88783963612822.567181047
#Sta/Elev= 30
       0 2620.74    11.6 2617.52    35.7 2608.17    43.8 2608.05    51.8 2604.99
   131.1 2588.13   136.1 2587.96   144.2 2589.65   148.2 2589.47   171.6 2581.09
   186.3 2576.63   192.4  2575.2   200.4 2574.96   232.5 2575.35   239.3 2576.63
   248.6 2581.25   264.6 2581.49   268.7 2583.34   276.7 2591.65   284.7 2597.63
   288.7 2599.82   301.1  2601.2   304.8 2602.43   308.8 2605.88   312.8 2607.68
   320.9 2609.23   340.8 2615.93   377.1 2626.64   401.2 2635.07     416 2641.59
#Mann= 3 ,-1,0
       0      .1       0   186.3    .045       0   239.3      .1       0
Bank Sta=186.3,239.3
XS Rating Curve= 0 ,0
Exp/Cntr(USF)=0,0
Exp/Cntr=0.3,0.1

Type RM Length L Ch R = 1 ,28778   ,243.4,243.1,243.6
XS GIS Cut Line= 2
2213395.44366398613223.4536082632213861.89729693 613068.68234322
#Sta/Elev= 30
       0 2672.19      15 2667.36    27.7 2660.87    42.9 2657.67    59.8 2650.51
    68.2 2645.64    76.6 2643.15    89.3 2635.33    97.7 2632.03   106.1 2626.25
   131.4 2615.72   139.8 2613.74   152.5 2613.15   156.7 2612.09   169.3 2603.75
   211.5 2588.91   236.8 2576.27   249.2 2569.12  262.56  2569.7   291.6 2568.62
  305.29 2569.72   316.9 2575.65   338.2 2576.11   350.6 2578.31   375.9 2586.11
   392.7 2595.25   404.3  2597.4   426.4 2604.81   434.9 2605.96   491.5 2624.89
#Mann= 3 ,-1,0
       0      .1       0  262.56    .045       0  305.29      .1       0
Bank Sta=262.56,305.29
XS Rating Curve= 0 ,0
Exp/Cntr=0.3,0.1

Type RM Length L Ch R = 1 ,28534   ,244.9,247.3,253.2
XS GIS Cut Line= 2
2213556.25518888613423.405085265 2213968.1106631613291.076070082
#Sta/Elev= 30
       0 2640.81    20.4 2636.37    33.5 2631.88    68.5  2622.7    79.7 2617.12
    89.3 2616.21   113.4 2603.34   132.6 2588.33     147 2578.36   172.2 2570.92
   192.5 2560.07   197.4 2559.17   217.9 2558.54     231 2559.13  233.27 2560.09
     252 2570.99     273 2570.97   285.6 2573.83   302.4 2581.26   310.8 2583.38
   323.4 2591.33   340.2 2599.88     357  2602.6   365.4  2602.8   369.6 2604.47
   394.8 2617.19   407.5 2626.09   415.1  2628.7   425.7 2638.48   432.6 2643.49
#Mann= 3 ,-1,0
       0      .1       0   192.5    .045       0  233.27      .1       0
Bank Sta=192.5,233.27
XS Rating Curve= 0 ,0
Exp/Cntr(USF)=0,0
Exp/Cntr=0.3,0.1

Type RM Length L Ch R = 1 ,28287   ,214.5,216.5,221.2
XS GIS Cut Line= 2
2213635.12350244613624.0127588682214042.07379921613558.099647576
#Sta/Elev= 30
       0 2609.36    12.4 2603.89      22 2598.74    57.8 2586.17    86.2 2578.94
   114.5 2574.18   134.8 2568.32     151 2564.88   175.3 2562.17   191.5 2555.87
   195.6 2554.95   236.1 2554.85  242.38 2555.85   244.2 2556.56   252.3 2562.55
   256.3 2563.84   276.6 2564.54   280.7 2565.44   285.9 2569.34   288.8 2572.33
   292.9 2578.01   296.9 2582.13     309 2592.94   313.1  2595.8   334.7 2602.39
   361.7 2616.08   373.9 2619.08     382 2623.34   402.2  2630.7   412.3  2635.8
#Mann= 3 ,-1,0
       0      .1       0   191.5    .045       0  242.38      .1       0
Bank Sta=191.5,242.38
XS Rating Curve= 0 ,0
Exp/Cntr=0.3,0.1

Type RM Length L Ch R = 1 ,28071   ,292.9,293.4,281.1
XS GIS Cut Line= 2
2213656.80273769613813.679928695 2214037.4345117 613800.29834289
#Sta/Elev= 30
       0 2579.94    11.4 2578.45    31.4 2573.55    39.4 2570.79    51.4 2568.31
    59.4 2568.05    75.4    2570    99.4 2570.01   115.4 2566.85   135.5 2565.11
   151.5 2561.17   159.5 2556.98   167.5  2551.2   177.2 2549.52   191.5 2548.15
   215.5 2549.45   219.5 2551.08   227.5 2559.77   231.5  2562.9   235.5  2563.9
   251.5 2564.93   255.5 2566.78   263.5  2575.8   275.5 2586.37   287.5 2599.74
   291.6 2601.84   303.6 2607.29   315.6 2609.96   359.5 2624.46   380.9 2632.29
#Mann= 3 ,-1,0
       0      .1       0   177.2    .045       0   215.5      .1       0
Bank Sta=177.2,215.5
XS Rating Curve= 0 ,0
Exp/Cntr(USF)=0,0
Exp/Cntr=0.3,0.1

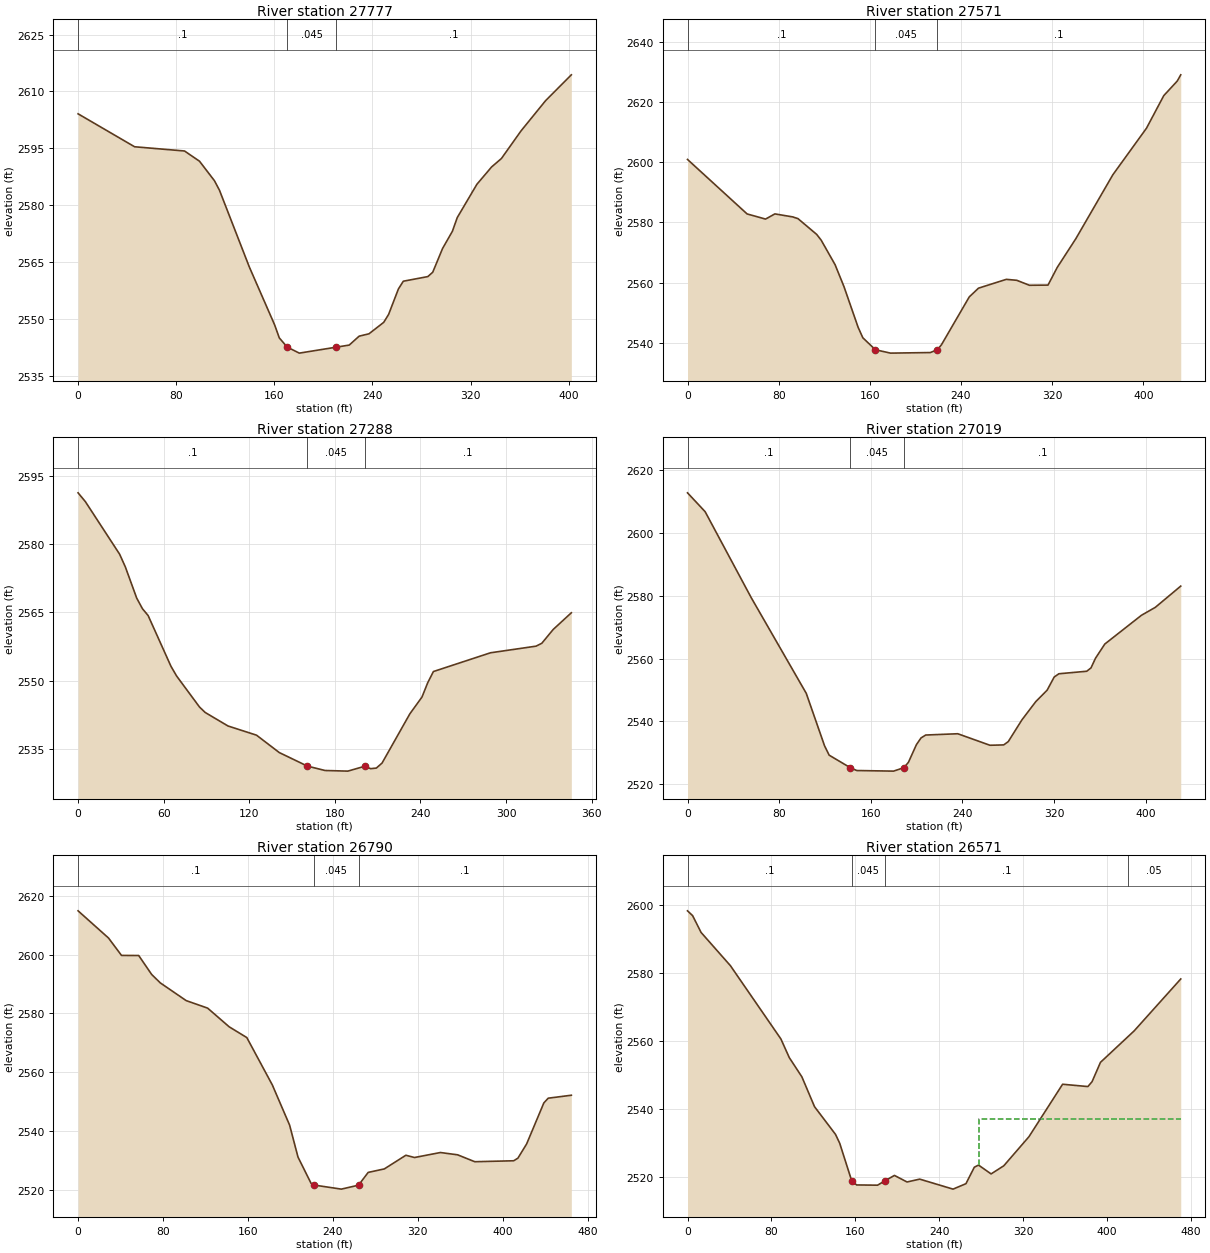
Type RM Length L Ch R = 1 ,27777   ,206.4,206.6,206.3
XS GIS Cut Line= 3
2213618.85452558614114.8302853112213839.52123839 614073.54504763
2214017.23652205614070.140476067
#Sta/Elev= 30
       0 2604.11    46.1 2595.43    86.8 2594.32      99 2591.63   111.2 2586.49
   115.3 2583.98   139.7 2563.72   160.2 2548.58   164.1 2545.08   170.5 2542.68
   180.4 2541.08  210.69 2542.66   221.1  2543.2   229.2 2545.55   237.2 2546.17
   249.2 2549.18   253.2 2551.27   261.2 2557.98   265.2 2560.02   285.2 2561.24
   289.2 2562.39   297.2 2568.64   305.2 2573.16   309.2 2576.79   325.2 2585.55
   337.2 2590.12   345.2 2592.34   361.2 2599.62   381.2 2607.57   402.2 2614.38
#Mann= 3 ,-1,0
       0      .1       0   170.5    .045       0  210.69      .1       0
Bank Sta=170.5,210.69
XS Rating Curve= 0 ,0
Exp/Cntr=0.3,0.1

Type RM Length L Ch R = 1 ,27571   ,277.6,282.5,285.1
XS GIS Cut Line= 2
2213648.70538496614316.9461004092214074.93367357614240.951909418
#Sta/Elev= 30
       0 2600.89    52.3 2582.79    68.5 2581.08    76.7  2582.8    92.4  2581.8
      97 2581.22   113.4 2575.98   117.3 2574.09   129.5 2565.95   137.3 2558.68
   149.8 2545.08   153.9 2541.64   164.9 2537.67   178.2 2536.55   213.1 2536.74
  219.38 2537.69   222.9 2539.34   247.3 2555.23   255.4 2558.13   279.8 2561.06
     289 2560.74   300.1 2559.09   316.4 2559.15   324.5 2565.03   340.8 2574.55
   373.3  2595.8   402.8 2611.25     418 2622.09   429.8 2626.92   432.9    2629
#Mann= 3 ,-1,0
       0      .1       0   164.9    .045       0  219.38      .1       0
Bank Sta=164.9,219.38
XS Rating Curve= 0 ,0
Exp/Cntr(USF)=0,0
Exp/Cntr=0.3,0.1

Type RM Length L Ch R = 1 ,27288   ,269,269.5,271.3
XS GIS Cut Line= 2
2213703.04366541 614557.215952372214048.79652181614557.884571328
#Sta/Elev= 30
       0 2591.24     5.1 2589.31    29.1 2577.77    33.1 2574.99    41.1 2568.11
    45.1 2565.79    49.1 2564.28    65.1 2553.14    69.1 2550.98    85.1 2544.19
    89.1 2542.98   105.1 2540.01   125.1 2537.99   141.1 2534.16   160.8 2531.19
   173.1 2530.23   189.1 2530.09   201.1 2531.17   205.1 2530.63   209.1 2530.76
   213.1 2531.86   232.6 2542.68   241.1 2546.37   245.1  2549.5   249.1 2551.97
   289.1 2556.09   321.1 2557.55   325.1 2558.18   333.1 2561.22   345.8 2564.88
#Mann= 3 ,-1,0
       0      .1       0   160.8    .045       0   201.1      .1       0
Bank Sta=160.8,201.1
XS Rating Curve= 0 ,0
Exp/Cntr=0.3,0.1

Type RM Length L Ch R = 1 ,27019   ,225.7,228.8,229.8
XS GIS Cut Line= 2
2213676.76764749614812.1511943762214106.30003135614843.356538503
#Sta/Elev= 30
       0 2612.66    15.4 2606.67    55.6 2579.37   103.7 2548.94   119.7 2532.24
   123.7 2529.29  142.15 2525.31   147.8 2524.41   179.9 2524.22  188.89  2525.3
   192.9 2527.01   199.9 2532.64   203.9 2534.76     208 2535.69     236  2536.1
   264.1 2532.44   276.1 2532.55   280.1 2533.61     292  2540.5   304.2 2546.35
     314 2549.93   320.2 2554.13   324.3 2555.16   348.6 2555.96   352.3 2557.01
   356.3 2560.12   364.4 2564.61   396.4 2573.75   408.5 2576.27   430.7 2583.02
#Mann= 3 ,-1,0
       0      .1       0  142.15    .045       0  188.89      .1       0
Bank Sta=142.15,188.89
XS Rating Curve= 0 ,0
Exp/Cntr(USF)=0,0
Exp/Cntr=0.3,0.1

Type RM Length L Ch R = 1 ,26790   ,220.5,218.6,217.4
XS GIS Cut Line= 2
2213583.87781776615010.0593338752214041.72376773615088.496584535
#Sta/Elev= 30
       0 2614.87    28.7  2605.6    40.9 2599.69    57.1 2599.66    69.3 2593.21
    77.4 2590.35   101.8 2584.31     122 2581.75   142.3 2575.39   158.9 2571.73
   182.9 2555.62   199.2 2541.93   207.1 2531.05   219.4 2522.12   221.8 2521.55
   247.9 2520.14   264.1 2521.49   273.2 2525.83   288.4 2527.02   308.7 2531.67
   316.8  2530.9   341.2  2532.6   357.4 2531.82   373.6 2529.47   410.2 2529.79
   414.2 2530.68   422.4 2535.52   438.6 2549.47   442.7 2551.09   464.5  2552.1
#Mann= 3 ,-1,0
       0      .1       0   221.8    .045       0   264.1      .1       0
Bank Sta=221.8,264.1
XS Rating Curve= 0 ,0
Exp/Cntr=0.3,0.1

Type RM Length L Ch R = 1 ,26571   ,281.5,281.6,284
XS GIS Cut Line= 2
2213615.32642288615254.2620005092214084.50794987615288.955000744
#Sta/Elev= 30
       0 2598.29     4.9 2596.87    12.9 2591.96    40.9 2582.18    89.1 2560.62
    97.1 2555.14   109.1 2549.49   121.2  2540.7   141.2 2532.57   145.2 2529.96
   156.6 2518.95   161.3 2517.71   181.3 2517.64   188.3 2518.92   197.4 2520.51
   209.4 2518.58   221.5 2519.42   253.3 2516.48   265.6 2518.08   273.6 2522.92
   277.6 2523.55   289.6 2520.95   301.7 2523.34   325.7 2531.89   357.8 2547.31
   381.9 2546.63   385.9 2548.06   393.9 2553.74     426 2562.98   470.5 2578.26
#Mann= 4 ,-1,0
       0      .1       0   156.6    .045       0   188.3      .1       0
     420     .05       0
#XS Ineff= 2 , 0
                          278.12         2537.19
Permanent Ineff=
       F       F
Bank Sta=156.6,188.3
XS Rating Curve= 0 ,0
Exp/Cntr(USF)=0,0
Exp/Cntr=0.3,0.1

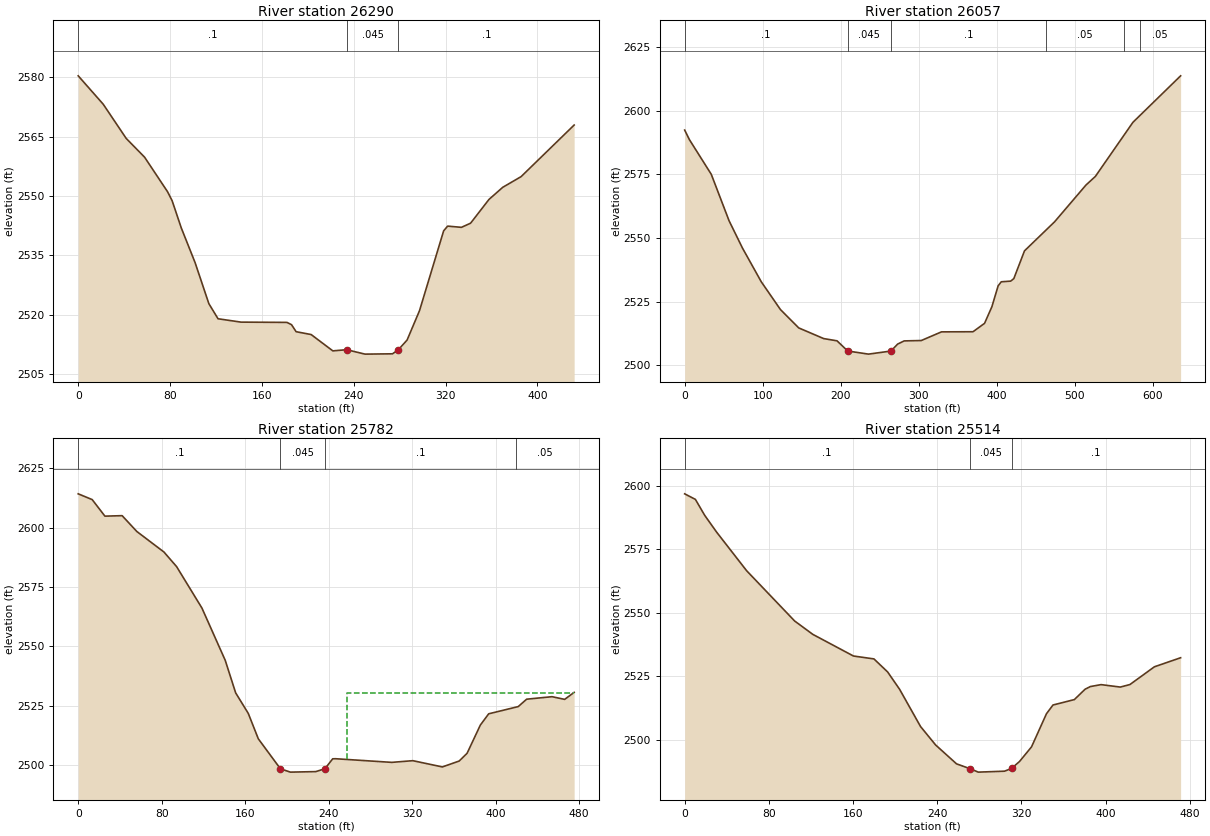
Type RM Length L Ch R = 1 ,26290   ,221.2,232.4,239.9
XS GIS Cut Line= 2
2213614.34406385615531.2867332252214046.34947388615529.068590554
#Sta/Elev= 30
       0 2580.38    21.8  2573.2    41.8 2564.56    57.8 2559.82    77.8  2551.1
    81.8 2548.82    89.8 2541.92   101.8 2533.17   113.8 2522.79   121.8 2518.97
   141.8 2518.12   181.8 2518.05   185.8 2517.48   189.8  2515.7   202.9 2514.98
   221.8 2510.85   233.8 2511.15   249.8 2510.03   273.8 2510.11  278.96 2511.17
   286.5  2513.6   297.3 2521.02   318.3 2541.18   321.8 2542.39   333.8 2542.08
   341.8 2543.13   357.8 2549.13   369.8  2552.2   385.8  2554.9     432 2567.94
#Mann= 3 ,-1,0
       0      .1       0   233.8    .045       0  278.96      .1       0
Bank Sta=233.8,278.96
XS Rating Curve= 0 ,0
Exp/Cntr=0.3,0.1

Type RM Length L Ch R = 1 ,26057   ,277.7,275.2,255.2
XS GIS Cut Line= 4
2213582.07099421615731.9481963682213762.14418591615726.992053477
2213904.22028211615784.8137205352214204.89295081615755.076863191
#Sta/Elev= 30
       0  2592.4     6.1 2588.63    34.1 2575.04    56.9 2556.81    74.1 2546.07
    98.2 2532.84   122.8 2521.93   146.2 2514.74   178.2 2510.55   195.3 2509.67
     209 2505.67   235.6 2504.45   264.4 2505.66     273  2508.4   281.4 2509.64
   303.3 2509.79   329.2 2513.19   369.6 2513.24   384.4 2516.54   393.8 2523.06
   401.8 2531.26   405.8 2532.85   417.9 2533.11   421.9  2534.1   435.6    2545
   474.2 2556.41   514.4 2570.83   526.4  2574.2   574.6 2595.46   635.7  2613.7
#Mann= 6 ,-1,0
       0      .1       0     209    .045       0   264.4      .1       0
  463.53     .05       0  563.53      .1       0  583.53     .05       0
Bank Sta=209,264.4
XS Rating Curve= 0 ,0
Exp/Cntr(USF)=0,0
Exp/Cntr=0.3,0.1

Type RM Length L Ch R = 1 ,25782   ,271.8,268.4,247.8
XS GIS Cut Line= 2
2213510.87286905616015.668749594 2213981.1675368615946.854666125
#Sta/Elev= 30
       0  2614.3    13.4 2611.87    25.6  2604.9    42.1  2605.1    56.2 2598.43
    82.2 2589.78    94.3 2583.64   118.6 2566.17   140.9 2544.18   150.9 2530.47
     163 2521.81   172.6 2511.13   193.8 2498.49   203.4 2497.09   227.7 2497.31
  236.42 2498.51   243.9  2502.7   246.7 2502.73   300.5  2501.2   320.7 2501.91
     349 2499.28   365.1 2501.76   372.7 2505.03   385.4 2516.91   393.4 2521.65
   421.7 2524.69   429.8 2527.81   454.1 2528.86   466.2 2527.73   475.3 2530.68
#Mann= 4 ,-1,0
       0      .1       0   193.8    .045       0  236.42      .1       0
     420     .05       0
#XS Ineff= 2 , 0
                          257.74         2530.61
Permanent Ineff=
       F       F
Bank Sta=193.8,236.42
XS Rating Curve= 0 ,0
Exp/Cntr=0.3,0.1

Type RM Length L Ch R = 1 ,25514   ,221.4,223.5,227.2
XS GIS Cut Line= 2
2213672.10393899616339.8445157592214043.81465579616049.910156651
#Sta/Elev= 30
       0 2596.82    10.2 2594.62      19 2588.37    30.4 2581.71    58.9 2566.52
   104.5 2546.73   121.8 2541.45   160.4 2532.93   179.9 2531.78   192.9 2526.65
   204.3 2519.81   224.2 2505.14   238.5 2497.89   258.4 2490.44     271 2488.57
   279.1 2487.18     304 2487.55  310.65 2488.62   318.3 2491.38   329.7 2497.14
   343.9 2510.19   350.1 2513.62   370.4 2515.76   380.6 2519.84   385.6 2520.89
   395.8 2521.65   414.1 2520.69   423.2 2521.68   446.5 2528.68   471.4 2532.24
#Mann= 3 ,-1,0
       0      .1       0     271    .045       0  310.65      .1       0
Bank Sta=271,310.65
XS Rating Curve= 0 ,0
Exp/Cntr(USF)=0,0
Exp/Cntr=0.3,0.1