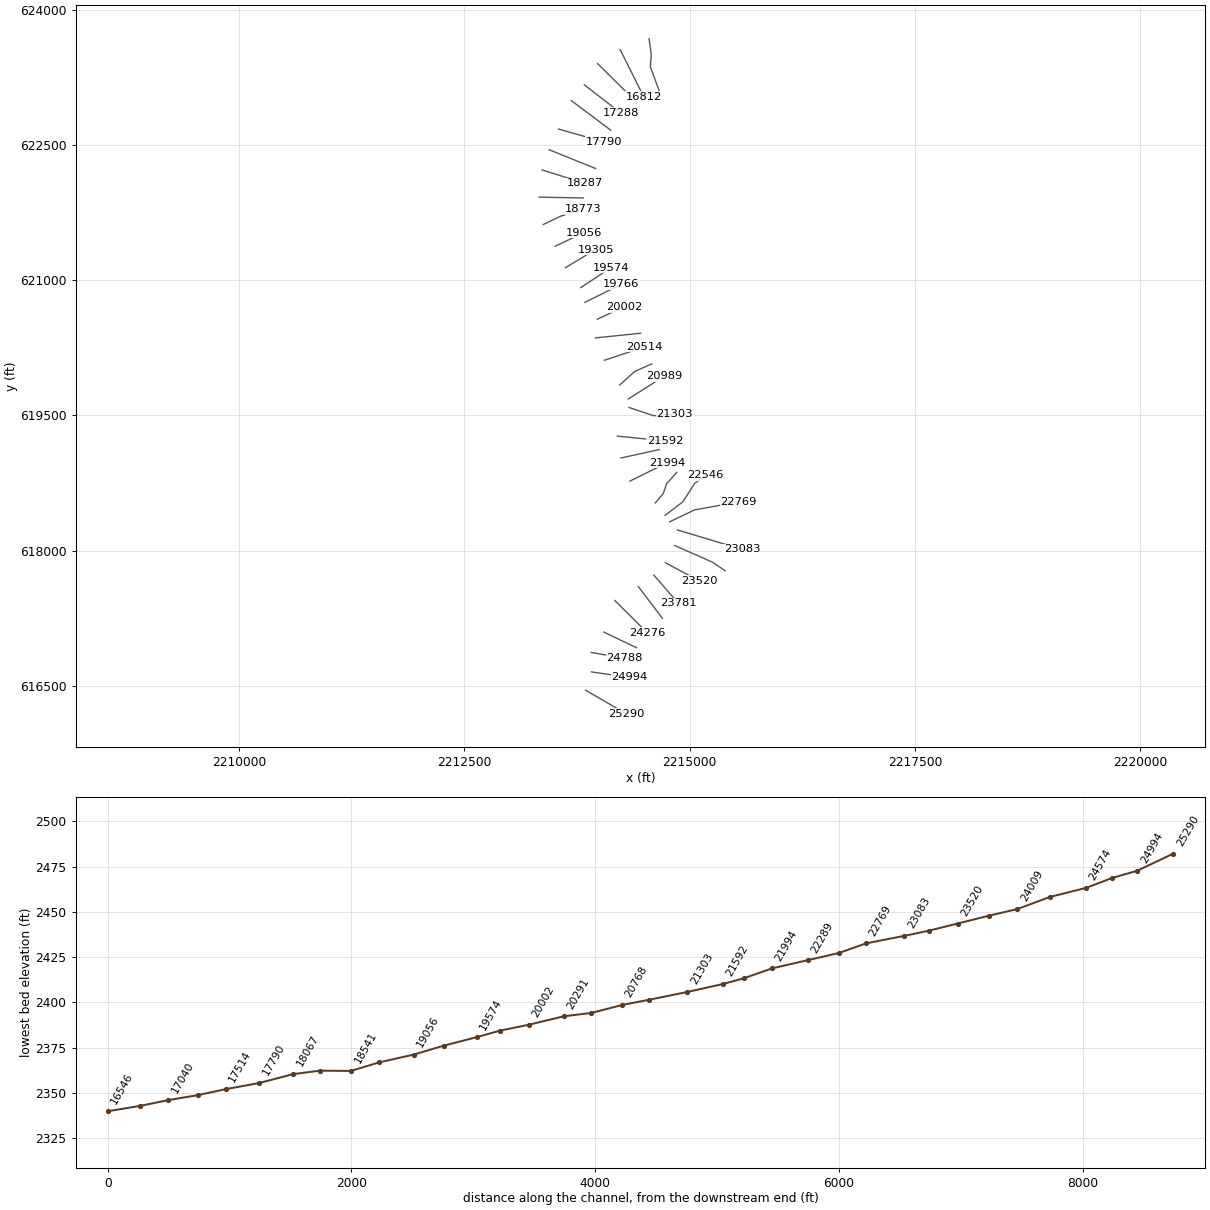
HEC-RAS study LFBUCKRV.prj: LFBUCKRV

--- LFBUCKRV.g01 (geometry) --- (continued)

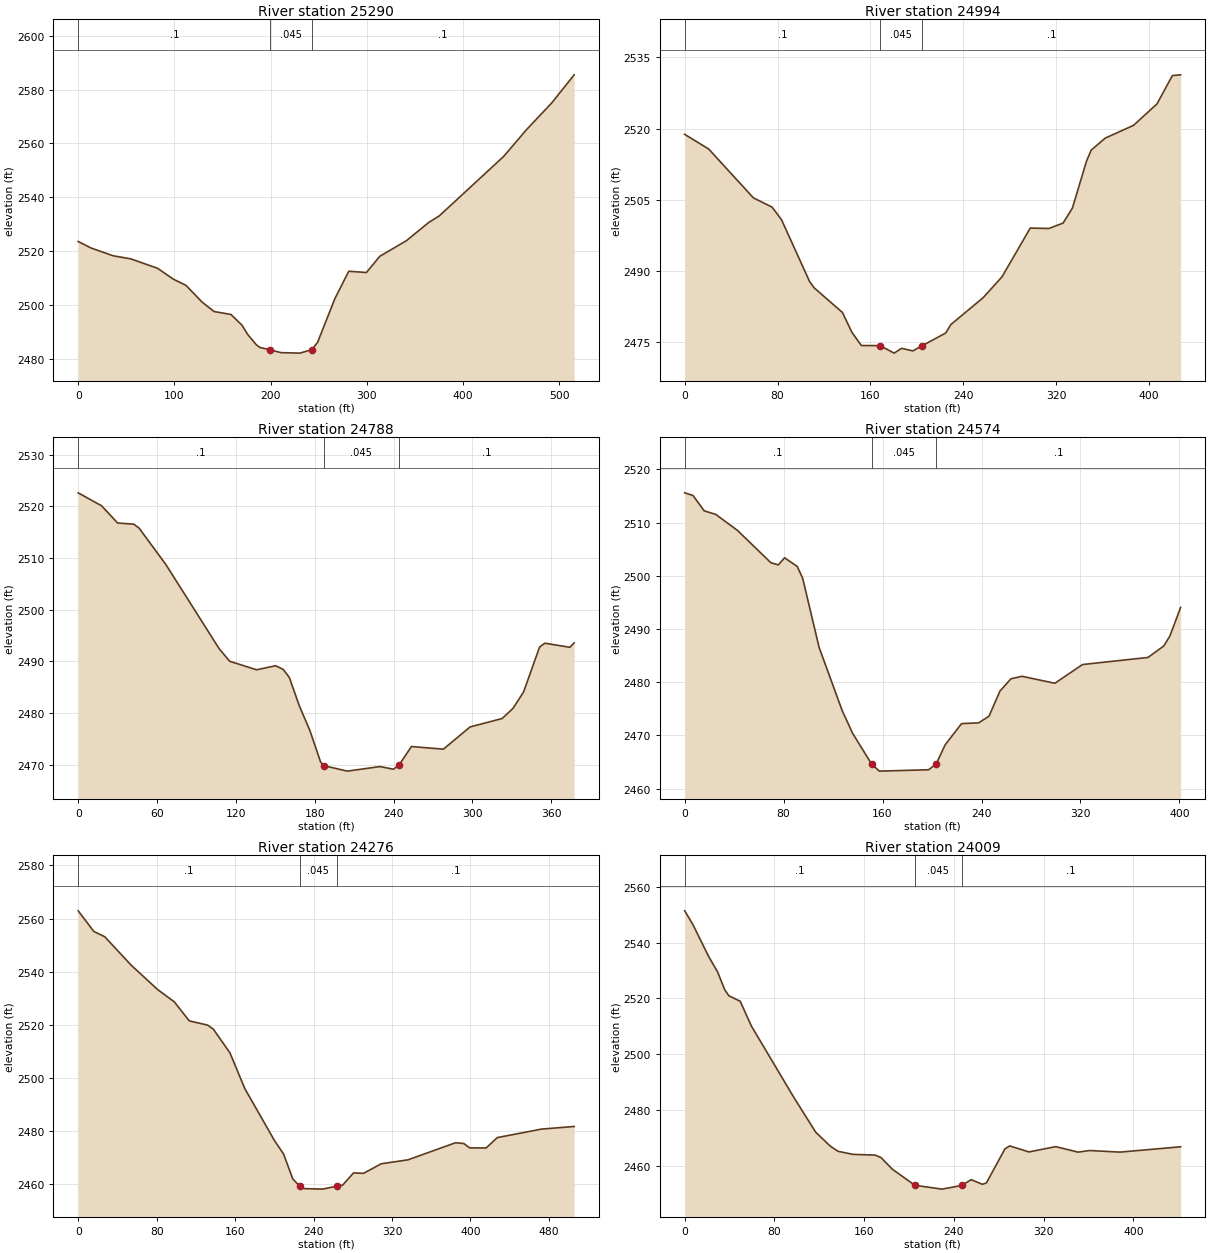
Type RM Length L Ch R = 1 ,25290   ,290.3,296.4,306.4
XS GIS Cut Line= 2
2213844.78051393616450.8576513812214291.01483469616192.446432088
#Sta/Elev= 30
       0 2523.66    13.2 2521.26    36.3 2518.36    54.8  2517.2    82.5 2513.72
    99.1 2509.65     112  2507.4   128.7 2501.22   141.3 2497.68   158.9 2496.59
   170.3 2492.62   176.4 2489.12   185.2 2485.35   188.8 2484.38   199.8 2483.46
   210.9 2482.44   230.4 2482.26   242.8 2483.52   248.9 2486.23   266.8 2502.38
   281.3 2512.62   299.7 2512.15   313.6 2518.16   341.3 2523.96   364.5 2530.71
   375.5 2533.16   442.4 2555.19   465.9 2565.02   492.6 2575.12   515.7 2585.45
#Mann= 3 ,-1,0
       0      .1       0   199.8    .045       0   242.8      .1       0
Bank Sta=199.8,242.8
XS Rating Curve= 0 ,0
Exp/Cntr=0.3,0.1

Type RM Length L Ch R = 1 ,24994   ,207.6,206.1,205
XS GIS Cut Line= 2
2213909.62466266616654.0722488662214332.34895824616593.373375655
#Sta/Elev= 30
       0 2518.81    20.7 2515.71    59.2 2505.43    75.3 2503.48    83.4 2500.83
   107.6 2487.81   111.7 2486.45   135.9  2481.3     144 2477.14   152.1 2474.36
   168.3 2474.32   180.4 2472.75   186.8 2473.76   196.5 2473.22   204.5 2474.31
   224.8 2476.98   229.2 2478.75   257.2 2484.46   273.3 2488.82   297.6 2499.07
   313.7 2498.99   325.9 2500.13   333.9 2503.28   346.1  2513.2   350.1 2515.48
   362.2 2518.01   386.5 2520.69   406.7 2525.19     420 2531.17   427.1 2531.33
#Mann= 3 ,-1,0
       0      .1       0   168.3    .045       0   204.5      .1       0
Bank Sta=168.3,204.5
XS Rating Curve= 0 ,0
Exp/Cntr(USF)=0,0
Exp/Cntr=0.3,0.1

Type RM Length L Ch R = 1 ,24788   ,218.7,214.1,203.6
XS GIS Cut Line= 2
2213906.67606385616870.3511505692214278.07301474  616803.2960671
#Sta/Elev= 30
       0  2522.6    17.8 2520.09      30 2516.76    42.2 2516.54    46.2 2515.81
    66.6 2508.77   107.2 2492.47   115.3 2490.01   135.7 2488.37   150.3 2489.15
     156 2488.44   160.7 2486.86   168.2 2481.43   176.3 2476.62   184.4 2470.57
   186.7 2469.83   204.8 2468.76   229.5 2469.64   239.9 2469.14  243.91 2469.85
   253.6 2473.52   277.9 2473.01   298.2 2477.31   322.6 2478.94   330.8 2480.88
   338.9 2484.06   351.1 2492.76   355.1 2493.51   374.1 2492.72   377.4 2493.57
#Mann= 3 ,-1,0
       0      .1       0   186.7    .045       0  243.91      .1       0
Bank Sta=186.7,243.91
XS Rating Curve= 0 ,0
Exp/Cntr=0.3,0.1

Type RM Length L Ch R = 1 ,24574   ,304.8,297.3,292.1
XS GIS Cut Line= 2
2214046.08092011617095.9861655752214407.99795164616923.319549458
#Sta/Elev= 30
       0 2515.59     6.7  2515.1    15.8  2512.2    25.1 2511.54    42.7 2508.52
    69.7 2502.45    75.7 2502.05    80.8 2503.38      91 2501.75    95.4 2499.54
   108.7 2486.53   127.3 2474.69   135.7 2470.42  151.13 2464.61   157.4 2463.27
   197.3 2463.53  203.33 2464.61   210.6 2468.21   223.9 2472.21   237.7 2472.34
   246.1 2473.61   254.9 2478.31   263.8 2480.63   272.7  2481.1   299.3 2479.79
   321.7 2483.31   374.6 2484.64   387.4  2486.8   392.3 2488.66     401 2494.04
#Mann= 3 ,-1,0
       0      .1       0  151.13    .045       0  203.33      .1       0
Bank Sta=151.13,203.33
XS Rating Curve= 0 ,0
Exp/Cntr(USF)=0,0
Exp/Cntr=0.3,0.1

Type RM Length L Ch R = 1 ,24276   ,270.4,266.9,265.5
XS GIS Cut Line= 2
2214168.92932945 617446.22449894  2214527.802756617089.770386653
#Sta/Elev= 30
       0 2562.94    15.9  2555.2    27.1 2553.18    53.9 2542.54    80.9 2533.35
      98  2528.7   113.3 2521.54     132 2519.95   137.7 2518.47   154.7 2509.56
   169.9 2496.08   200.1 2476.57   209.5 2471.41   218.8 2462.13  225.87 2459.39
   230.1 2458.45   249.1 2458.25   263.9 2459.37   269.6 2459.71   280.8 2464.35
     291 2464.19     309 2467.78   336.4 2469.28   384.9 2475.71   393.4 2475.39
   399.2 2473.78     416 2473.73   427.4 2477.63   472.5 2480.83   505.8 2481.82
#Mann= 3 ,-1,0
       0      .1       0  225.87    .045       0   263.9      .1       0
Bank Sta=225.87,263.9
XS Rating Curve= 0 ,0
Exp/Cntr=0.3,0.1

Type RM Length L Ch R = 1 ,24009   ,227.3,228.5,229.8
XS GIS Cut Line= 2
2214429.54289567617600.6009573042214696.83471949617248.439101833
#Sta/Elev= 30
       0 2551.39     7.2 2546.57    21.4 2534.99    29.4 2529.43    35.7 2523.09
    39.4 2520.92    49.5 2518.95    59.5 2510.04      97 2484.67   116.8 2471.98
   129.8 2466.98   136.7 2465.12   149.9 2464.03   169.8 2463.75     175 2462.88
   185.1 2458.71   205.2 2452.93   229.3 2451.55     247 2452.86   255.4 2454.95
   265.4 2453.28     269 2453.78   285.5    2466   289.8 2467.05   306.9 2464.89
   330.7  2466.8   350.8 2464.82   360.8  2465.4   388.1 2464.83   442.1 2466.74
#Mann= 3 ,-1,0
       0      .1       0   205.2    .045       0     247      .1       0
Bank Sta=205.2,247
XS Rating Curve= 0 ,0
Exp/Cntr(USF)=0,0
Exp/Cntr=0.3,0.1

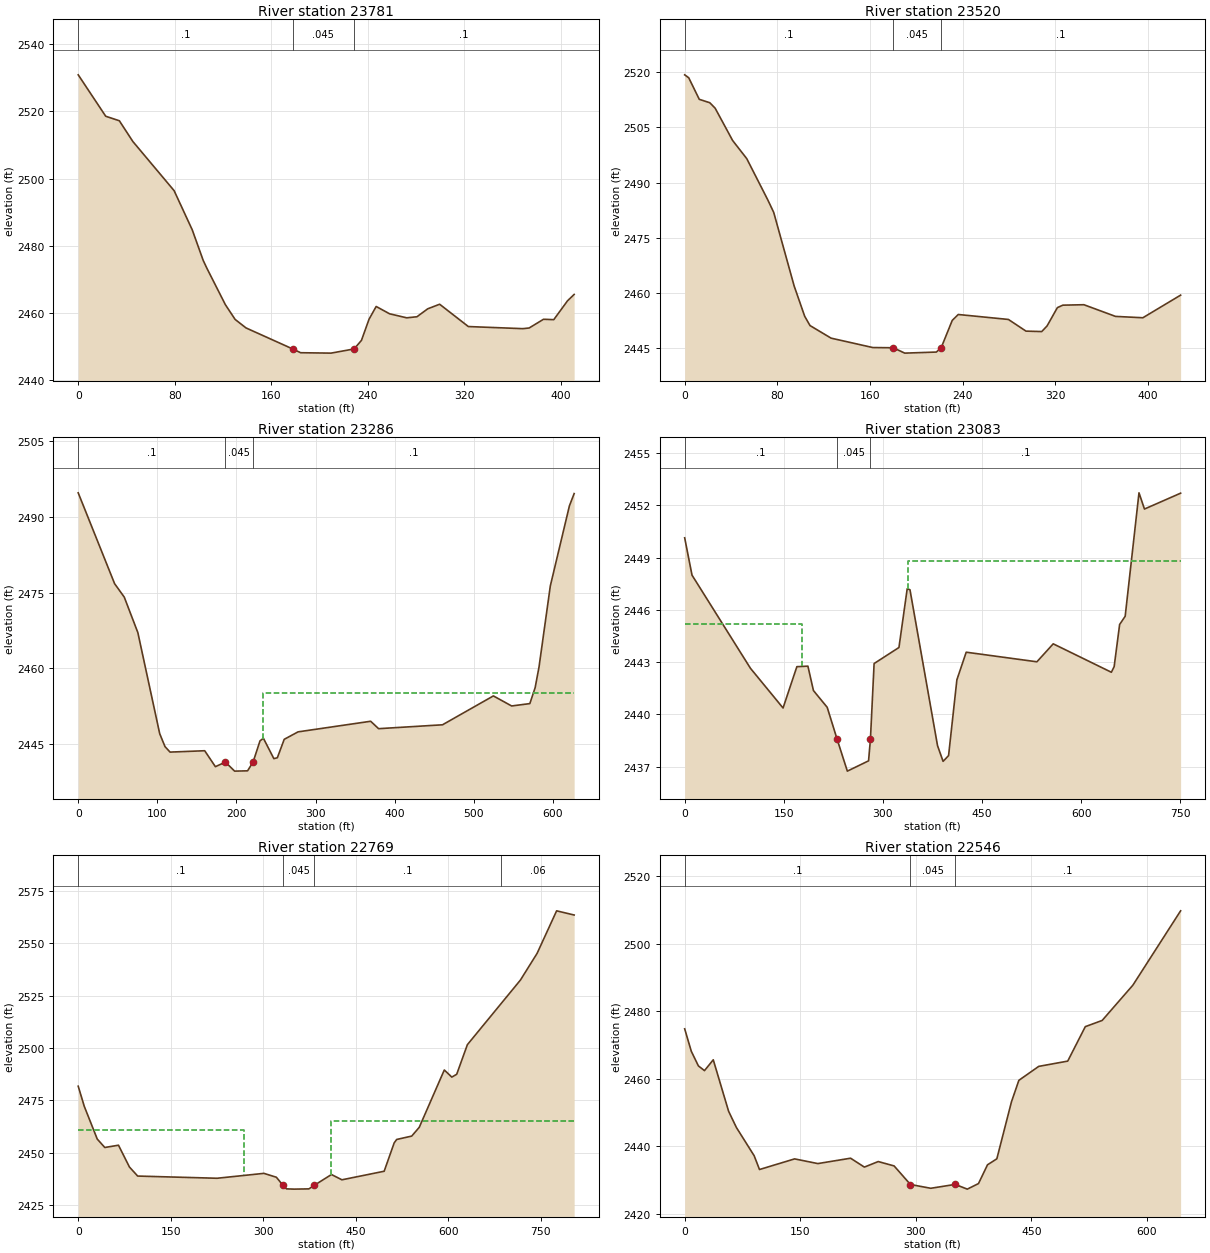
Type RM Length L Ch R = 1 ,23781   ,254.4,261.3,270.5
XS GIS Cut Line= 2
2214602.24104917617727.4186173012214871.80385841617416.984808059
#Sta/Elev= 30
       0  2530.9    22.8 2518.56    34.1 2517.21    45.3 2511.03    79.5 2496.38
    94.5 2484.73   103.6 2475.61   106.7 2473.24     122  2462.4   130.1    2458
   139.1 2455.48  177.81 2449.21   184.4 2448.09   209.6 2447.97   228.7 2449.22
   234.8 2451.78   241.1 2458.09     247 2461.87   258.1 2459.69   272.3 2458.49
   280.8 2458.81   289.7 2461.17   299.6 2462.54   323.4 2455.89   368.5 2455.26
   373.8 2455.46   385.7 2458.06   394.2 2457.94   405.6 2463.56   411.1 2465.46
#Mann= 3 ,-1,0
       0      .1       0  177.81    .045       0   228.7      .1       0
Bank Sta=177.81,228.7
XS Rating Curve= 0 ,0
Exp/Cntr=0.3,0.1

Type RM Length L Ch R = 1 ,23520   ,231.7,233.4,234.4
XS GIS Cut Line= 2
2214729.06099784617866.2472921232215105.61079344617662.364112639
#Sta/Elev= 30
       0 2519.34     3.5 2518.54    12.6 2512.67    21.7 2511.74    26.3 2510.26
    41.4 2501.46    53.6 2496.52    71.8 2485.26    76.9 2481.86    94.5 2461.87
   103.6 2453.61   108.2 2451.07   126.4 2447.64   162.4 2445.08   180.1 2445.02
     190 2443.56   217.3 2443.85   221.5 2445.05     231 2452.46   236.2 2454.08
   279.5 2452.73   294.7 2449.55   308.3 2449.43   312.9 2450.97   321.8 2455.95
   326.5 2456.62   344.7 2456.74     372 2453.56   395.6 2453.19   428.2 2459.35
#Mann= 3 ,-1,0
       0      .1       0   180.1    .045       0   221.5      .1       0
Bank Sta=180.1,221.5
XS Rating Curve= 0 ,0
Exp/Cntr(USF)=0,0
Exp/Cntr=0.3,0.1

Type RM Length L Ch R = 1 ,23286   ,198.7,203.5,205.4
XS GIS Cut Line= 3
2214833.92566156618055.611480195 2215252.1927123617871.053621267
2215393.11878527617776.533214732
#Sta/Elev= 30
       0 2494.79      46 2476.79    58.2 2474.13    75.4 2467.09     103 2447.08
   109.7 2444.51   116.1 2443.42   159.9 2443.69   173.4 2440.53   186.1 2441.44
   197.7 2439.65   214.1 2439.71   221.1 2441.46   229.8 2445.65   234.1 2446.16
   247.3 2442.13   251.7 2442.29   260.4 2445.95   277.9 2447.43   369.7 2449.53
   379.7 2448.06   460.5 2448.83   524.8 2454.55   547.9 2452.56   570.9 2453.03
   577.6 2456.19   582.5 2460.29   596.8 2476.36   620.9  2492.2   626.9 2494.64
#Mann= 3 ,-1,0
       0      .1       0   186.1    .045       0   221.1      .1       0
#XS Ineff= 2 , 0
                          233.47         2455.06
Permanent Ineff=
       F       F
Bank Sta=186.1,221.1
XS Rating Curve= 0 ,0
Exp/Cntr=0.3,0.1

Type RM Length L Ch R = 1 ,23083   ,298,313.7,321.9
XS GIS Cut Line= 2
2214861.56538614 618229.055859412215580.55799144618013.478512091
#Sta/Elev= 30
       0 2450.13    11.1 2447.99    99.5 2442.65   148.9 2440.37   169.8 2442.74
   186.5 2442.77   194.9 2441.37   215.7 2440.41   230.7 2438.58   246.2 2436.75
   278.3 2437.34  281.15 2438.58   286.7 2442.92   324.3 2443.84   336.8 2447.21
     341 2447.15   382.7 2438.21   391.1 2437.31   399.4 2437.64     412 2441.99
   426.1 2443.57   533.1 2443.02   557.8 2444.05   645.8 2442.42     650 2442.74
   658.3 2445.16   666.7 2445.63   687.6 2452.71   695.9 2451.78   750.6 2452.69
#Mann= 3 ,-1,0
       0      .1       0   230.7    .045       0  281.15      .1       0
#XS Ineff= 2 , 0
          177.28  2445.2  337.37          2448.8
Permanent Ineff=
       F       F
Bank Sta=230.7,281.15
XS Rating Curve= 0 ,0
Exp/Cntr(USF)=0,0
Exp/Cntr=0.3,0.1

Type RM Length L Ch R = 1 ,22769   ,196.3,222.6,240
XS GIS Cut Line= 3
2214777.31362585618318.7669425962215052.32811949618450.923841419
     2215543.385      618538.954
#Sta/Elev= 30
       0 2481.78     9.9 2472.11    30.9 2456.52    43.1 2452.51    65.3 2453.59
    83.1 2443.16    96.4 2438.86   225.1 2437.81   301.1 2440.15   321.2  2438.3
   331.8 2434.52   337.5 2432.75   349.7 2432.62     374 2432.74   382.7 2434.43
   410.6  2439.6   427.5 2437.07     496 2441.16   512.2 2454.68   516.3 2456.34
   540.7 2457.96   552.9 2462.15   593.5 2489.52   605.7 2486.12   613.6 2487.48
   630.9 2501.61     717 2532.51   743.9  2545.2   775.6 2565.54     804 2563.54
#Mann= 4 ,-1,0
       0      .1       0   331.8    .045       0   382.7      .1       0
  685.12     .06       0
#XS Ineff= 2 , 0
          268.51  2460.8  409.84         2465.23
Permanent Ineff=
       F       F
Bank Sta=331.8,382.7
XS Rating Curve= 0 ,0
Exp/Cntr=0.3,0.1

Type RM Length L Ch R = 1 ,22546   ,253.8,257.2,261.8
XS GIS Cut Line= 4
2214726.89325968618390.3947486972214923.48692768618540.731083049
 2215055.6507381  618745.58498922215177.90226274618836.447608863
#Sta/Elev= 30
       0 2474.78     8.6 2468.13    17.8  2463.8    25.7  2462.4    37.1 2465.61
      57 2450.37    67.1 2445.56    90.2 2437.17    97.1  2433.1   142.7 2436.25
   172.8 2434.86   215.3 2436.45   233.2 2433.82   251.2 2435.46   271.8 2434.16
     293 2428.66   319.4 2427.54  350.99 2428.69   366.8 2427.29   381.3 2428.94
     393  2434.5   405.1 2436.27   424.1 2453.17   433.7 2459.53   459.5 2463.66
   497.1 2465.22   519.9 2475.43   541.8 2477.27   581.6 2487.71   643.6 2509.75
#Mann= 3 ,-1,0
       0      .1       0     293    .045       0  350.99      .1       0
Bank Sta=293,350.99
XS Rating Curve= 0 ,0
Exp/Cntr(USF)=0,0
Exp/Cntr=0.3,0.1

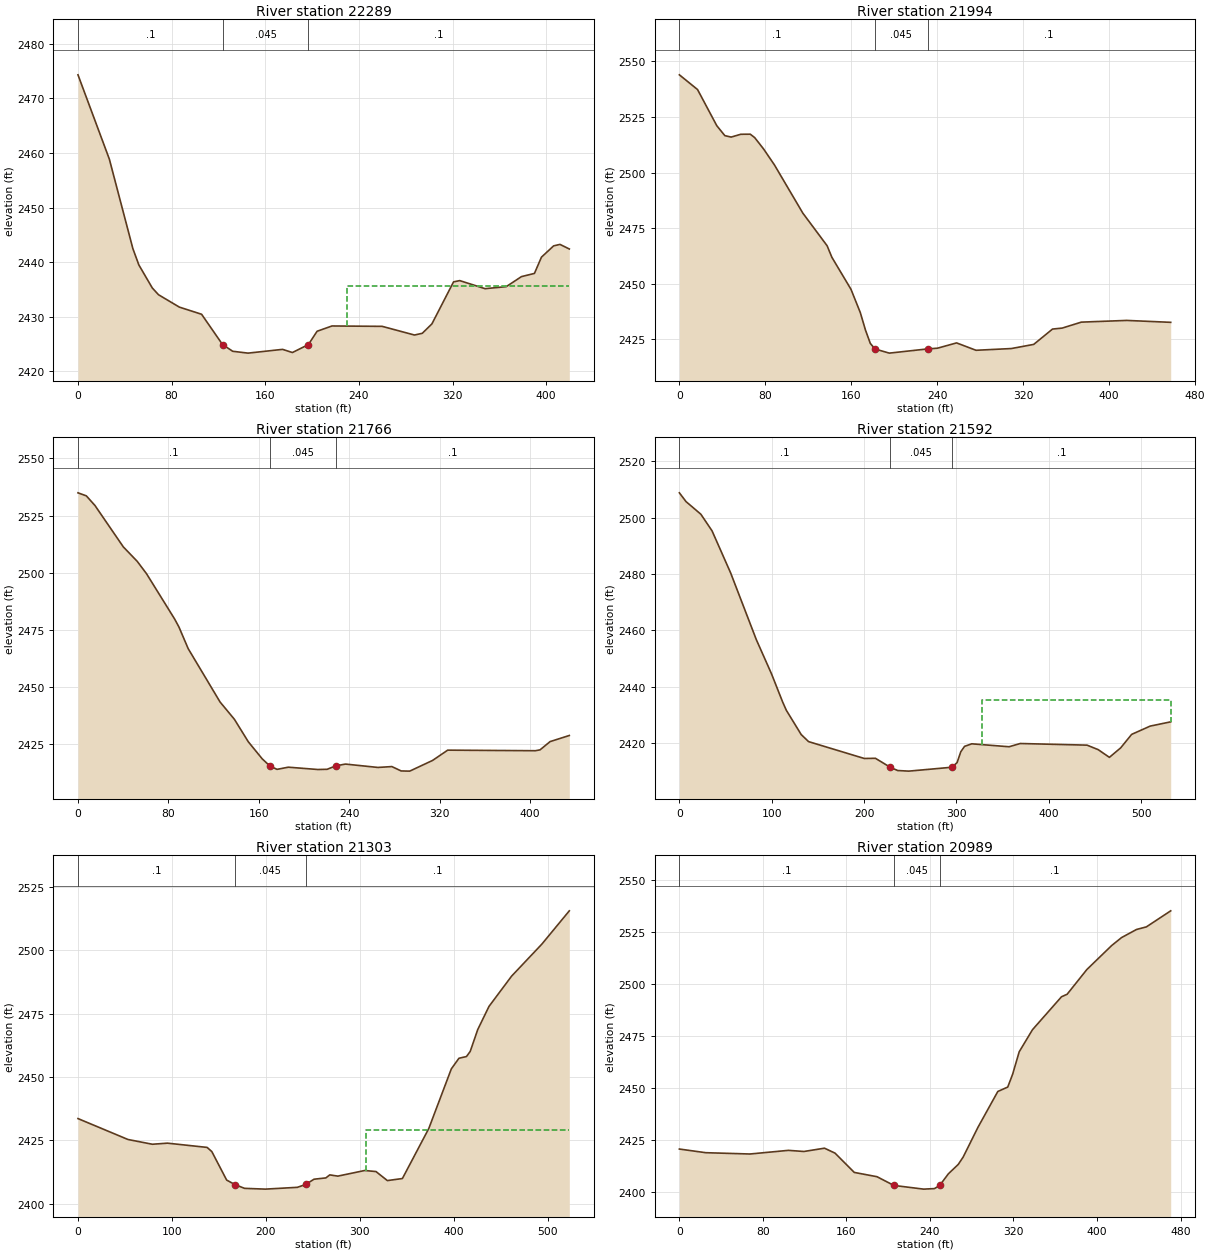
Type RM Length L Ch R = 1 ,22289   ,320.4,295.2,274.4
XS GIS Cut Line= 4
2214618.46540142618528.8016308032214706.49115564618632.141219843
2214742.01681451618738.6931720372214855.97889876618867.228455215
#Sta/Elev= 30
       0 2474.34    26.8 2458.88    46.9 2442.47      52 2439.48    63.5 2435.25
    68.8 2434.01    86.6 2431.74   105.6 2430.43   123.5 2424.88   132.2 2423.64
   145.3  2423.3   174.8 2423.99   183.2 2423.41  196.83 2424.86   204.3 2427.31
     217 2428.28   259.9 2428.21   287.5 2426.62   294.2 2426.94   302.4 2428.66
   320.9 2436.37   326.2  2436.6   347.8 2435.12   365.9 2435.49   378.9 2437.33
     390 2437.92     396  2440.9   406.4 2442.97   411.8 2443.24   419.8  2442.4
#Mann= 3 ,-1,0
       0      .1       0   123.5    .045       0  196.83      .1       0
#XS Ineff= 2 , 0
                          229.69         2435.68
Permanent Ineff=
       F       F
Bank Sta=123.5,196.83
XS Rating Curve= 0 ,0
Exp/Cntr=0.3,0.1

Type RM Length L Ch R = 1 ,21994   ,234.4,227.6,220.6
XS GIS Cut Line= 2
2214337.01001895618770.3657036532214746.71783125618973.567562173
#Sta/Elev= 30
       0 2543.98    16.9 2537.36    34.8  2521.1    42.3 2516.61    48.2 2515.96
    57.1 2517.22      66 2517.26    70.1 2515.72    78.4 2510.59    88.4 2503.49
   114.9 2481.74   137.5 2467.05   141.9 2461.89   159.7 2447.46   168.4 2436.96
   173.2 2429.11   177.7  2423.1   182.1 2420.58   195.4 2418.72   231.1 2420.62
   240.2 2420.94     258 2423.32   276.1    2420   308.9 2420.78   329.8 2422.65
   347.3 2429.55   356.3 2429.99   374.1 2432.67   416.3 2433.44   457.3 2432.58
#Mann= 3 ,-1,0
       0      .1       0   182.1    .045       0   231.1      .1       0
Bank Sta=182.1,231.1
XS Rating Curve= 0 ,0
Exp/Cntr(USF)=0,0
Exp/Cntr=0.3,0.1

Type RM Length L Ch R = 1 ,21766   ,185.4,174.6,167.5
XS GIS Cut Line= 2
2214236.98606385619026.5263158822214661.50638246619120.099000471
#Sta/Elev= 30
       0 2534.98     7.4 2533.65      15 2529.46    40.1 2511.35    52.4 2505.03
    60.6 2499.65    85.5 2479.82    89.3 2476.35    97.5 2466.86   125.7 2443.54
   138.4 2435.96   150.7 2426.14     163 2418.68  169.73 2415.58   176.1 2414.08
   186.1 2415.03   212.2 2414.02   220.4 2414.11   228.5 2415.67   236.7 2416.39
   265.4 2414.92   277.7  2415.3   285.9 2413.39   293.5 2413.31   313.7 2417.98
   327.1 2422.48   404.7 2422.23   408.8 2422.61   417.7 2426.22   434.7 2428.89
#Mann= 3 ,-1,0
       0      .1       0  169.73    .045       0   228.5      .1       0
Bank Sta=169.73,228.5
XS Rating Curve= 0 ,0
Exp/Cntr=0.3,0.1

Type RM Length L Ch R = 1 ,21592   ,294.9,289.2,279.2
XS GIS Cut Line= 2
2214196.98216916619269.2458398492214726.29822989619215.719496629
#Sta/Elev= 30
       0 2508.85     7.2 2505.74    23.3 2501.24    35.4 2495.34    55.5 2480.43
    83.3 2456.76    99.7 2444.66   111.8 2434.64   115.8 2431.69   131.9 2423.07
   139.9 2420.56   200.2 2414.58   212.3 2414.64   228.4 2411.44   236.4  2410.3
   248.5 2410.09   295.1 2411.47   300.7 2413.12   304.7 2416.96   308.8 2418.89
   316.6 2419.78     357 2418.74   369.1 2419.89   441.4 2419.31   453.5 2417.71
   465.6 2414.98   477.8 2418.33   489.7 2423.13   509.8 2426.07     532 2427.58
#Mann= 3 ,-1,0
       0      .1       0   228.4    .045       0   295.1      .1       0
#XS Ineff= 2 , 0
                          327.87         2435.46
Permanent Ineff=
       F       F
Bank Sta=228.4,295.1
XS Rating Curve= 0 ,0
Exp/Cntr(USF)=0,0
Exp/Cntr=0.3,0.1

Type RM Length L Ch R = 1 ,21303   ,287.6,313.6,337
XS GIS Cut Line= 3
2214325.70983051619586.8147574152214600.95820056619495.371713983
2214833.35684216619512.358072387
#Sta/Elev= 30
       0 2433.59    53.2 2425.34    79.2 2423.46    95.3 2423.89   137.5 2422.21
   142.5 2420.56   158.3 2409.32     167 2407.57   177.3 2406.06   199.4 2405.75
   233.6 2406.46  242.46  2407.6   251.3 2409.66   263.9 2410.18   268.1 2411.37
   276.6 2410.88   305.3  2413.1   317.3 2412.68   329.4 2409.12   345.4 2409.93
   373.5 2429.68   397.5 2453.21   405.6 2457.39   413.6 2458.07   417.6 2460.09
   425.6 2468.71   437.6 2477.86   461.7 2489.82   493.8  2502.4   523.1 2515.57
#Mann= 3 ,-1,0
       0      .1       0     167    .045       0  242.46      .1       0
#XS Ineff= 2 , 0
                          306.27         2429.25
Permanent Ineff=
       F       F
Bank Sta=167,242.46
XS Rating Curve= 0 ,0
Exp/Cntr=0.3,0.1

Type RM Length L Ch R = 1 ,20989   ,216.8,220.8,223.8
XS GIS Cut Line= 2
2214318.90328427619681.1013140692214715.89032982619933.864601496
#Sta/Elev= 30
       0 2420.69    25.2 2418.94    67.6 2418.31   104.4 2420.06   119.3 2419.52
     139  2421.1   149.1 2418.72   167.5 2409.47   189.3  2407.4   205.4 2403.22
   233.9 2401.44   244.3 2401.69  249.36 2403.23   257.6 2408.77   267.1 2413.31
   271.8 2416.84     286 2431.15     305 2448.34   314.5 2450.46   319.2 2456.64
   325.5 2467.42   338.2 2478.01     366 2493.83   371.4 2495.05   390.3 2506.92
   414.1 2518.46   423.5 2522.25   437.8 2526.14   447.3  2527.4   470.6 2535.11
#Mann= 3 ,-1,0
       0      .1       0   205.4    .045       0  249.36      .1       0
Bank Sta=205.4,249.36
XS Rating Curve= 0 ,0
Exp/Cntr(USF)=0,0
Exp/Cntr=0.3,0.1

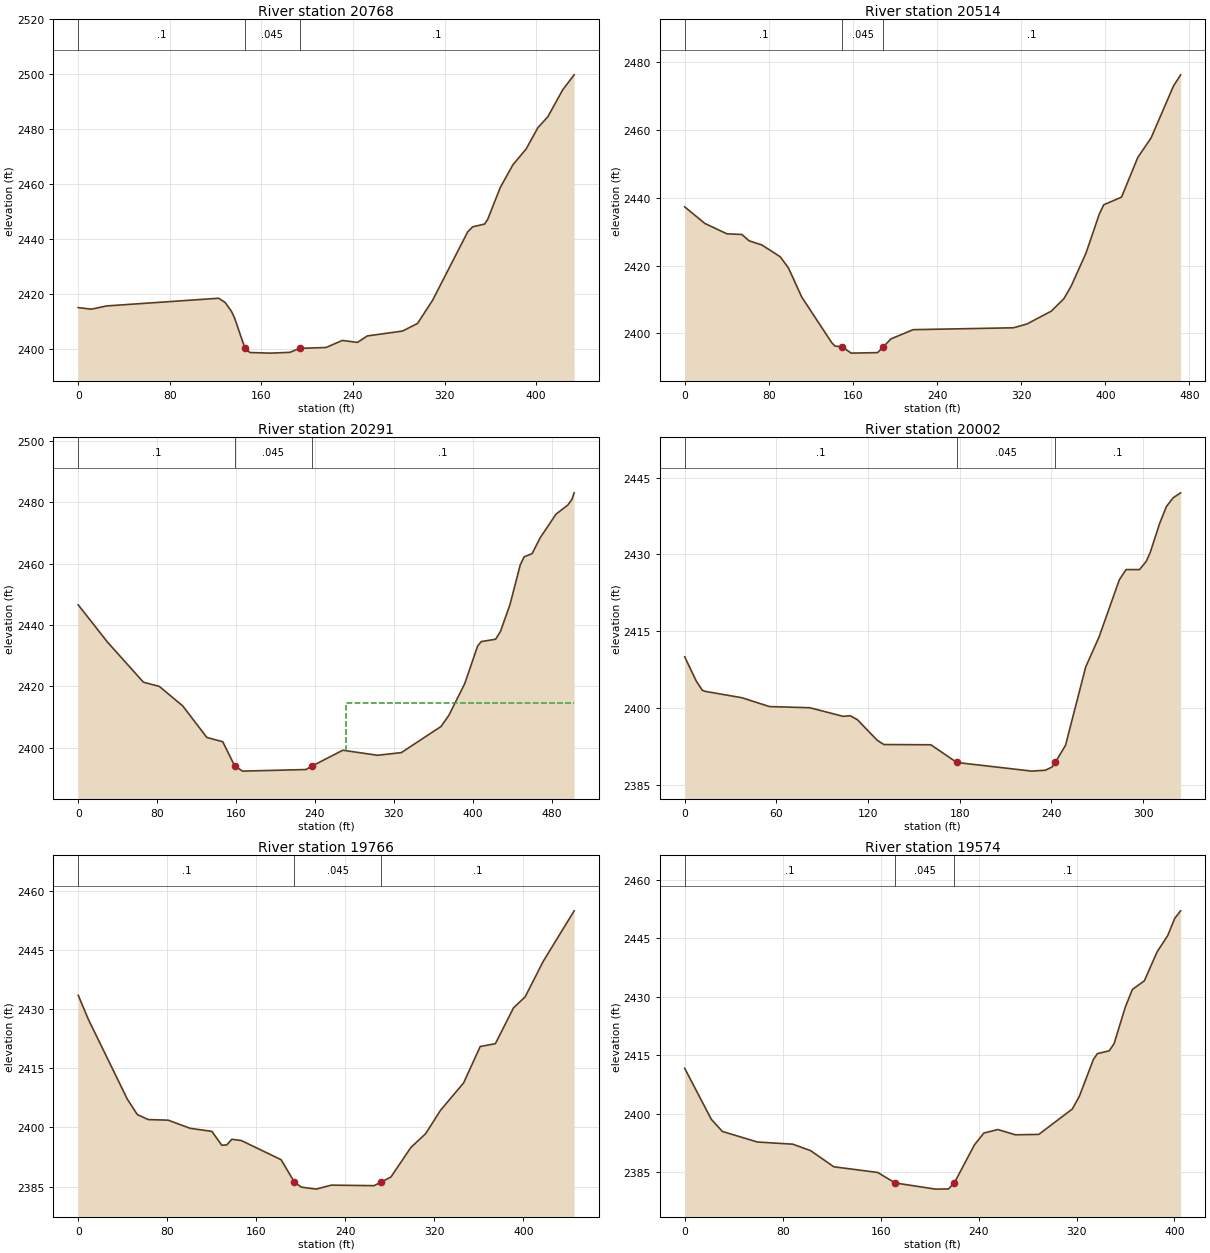
Type RM Length L Ch R = 1 ,20768   ,264.7,254.4,247
XS GIS Cut Line= 3
2214223.68134917619836.5207572442214388.58787016619985.770703222
2214581.14076049620071.406539534
#Sta/Elev= 30
       0 2415.12    11.5 2414.56    24.8 2415.73   122.6 2418.53   128.3 2417.03
   133.9 2413.73   136.7 2411.23  145.66 2400.31     150 2398.78   167.9 2398.56
   184.9 2398.85   193.4 2400.28   216.5 2400.61   230.7 2403.18   243.9 2402.46
   252.6 2404.82   283.3 2406.59   296.4 2409.36   309.6 2417.83   340.2 2442.67
   344.5  2444.5     355 2445.53   357.7 2447.25   368.6 2458.76   379.6 2467.02
   391.3 2472.87   401.5 2480.57   410.2 2484.56   423.3 2494.43   433.2 2499.82
#Mann= 3 ,-1,0
       0      .1       0  145.66    .045       0   193.4      .1       0
Bank Sta=145.66,193.4
XS Rating Curve= 0 ,0
Exp/Cntr=0.3,0.1

Type RM Length L Ch R = 1 ,20514   ,233.7,222.9,218.1
XS GIS Cut Line= 2
 2214053.9935313620110.6230972312214501.53323433620259.307383953
#Sta/Elev= 30
       0 2437.32    19.2 2432.42    40.2 2429.36    54.4 2429.16    61.3 2427.29
    73.4 2426.07    90.8  2422.6    98.7 2419.29   111.3  2410.7   139.8 2397.24
     143  2396.2   149.8    2396   158.3 2394.13   183.5 2394.28   188.8 2395.98
   196.2 2398.34   217.3 2401.06   312.6 2401.61   325.3 2402.71   348.6 2406.52
   360.6  2410.2   367.6 2413.97   381.6 2423.65   394.3 2435.21   398.5 2437.94
   415.4 2440.19   430.9 2451.93   443.5 2457.67   464.8    2473   471.6 2476.31
#Mann= 3 ,-1,0
       0      .1       0   149.8    .045       0   188.8      .1       0
Bank Sta=149.8,188.8
XS Rating Curve= 0 ,0
Exp/Cntr(USF)=0,0
Exp/Cntr=0.3,0.1

Type RM Length L Ch R = 1 ,20291   ,269.4,288.7,289.9
XS GIS Cut Line= 2
2213954.44021933      620358.7552214454.52469741 620410.19016571
#Sta/Elev= 30
       0 2446.53    29.9 2434.31    66.1 2421.32    82.2 2419.95   105.9 2413.61
   130.4 2403.31   146.5 2401.92   158.6 2394.04   166.6 2392.33   230.9 2392.85
   237.1    2394   268.2 2399.14   303.3  2397.5   327.5 2398.36   367.7 2406.87
   375.6 2410.46   391.8 2420.85   404.9 2433.15   408.5 2434.55   423.1 2435.33
     428 2437.86   437.7 2446.66   448.1 2459.61   452.1 2462.21   460.1 2463.23
   468.2 2468.37   484.3 2476.09   496.3 2479.07   500.4  2480.9   502.7 2483.05
#Mann= 3 ,-1,0
       0      .1       0   158.6    .045       0   237.1      .1       0
#XS Ineff= 2 , 0
                          271.34         2414.67
Permanent Ineff=
       F       F
Bank Sta=158.6,237.1
XS Rating Curve= 0 ,0
Exp/Cntr=0.3,0.1

Type RM Length L Ch R = 1 ,20002   ,234.7,236.1,235.9
XS GIS Cut Line= 2
2213973.76137516620566.0065275962214268.58447361620701.495083872
#Sta/Elev= 30
       0 2409.98     7.6 2405.23    11.5 2403.45    13.3 2403.23    37.4 2401.98
    55.5 2400.25    81.9 2400.02   103.7 2398.34   108.3 2398.46     113 2397.69
   125.9 2393.69   130.3 2392.83   161.1 2392.78  178.08 2389.32   227.2 2387.63
     236 2387.81   240.4 2388.43   242.5 2389.34   249.2 2392.68   262.4 2407.99
   271.2 2413.91   284.4 2425.03   288.8 2427.03   297.6 2427.03     302 2428.63
   304.6 2430.37   310.8 2436.07   315.2 2439.35   319.6 2441.06   324.5 2442.03
#Mann= 3 ,-1,0
       0      .1       0  178.08    .045       0   242.5      .1       0
Bank Sta=178.08,242.5
XS Rating Curve= 0 ,0
Exp/Cntr(USF)=0,0
Exp/Cntr=0.3,0.1

Type RM Length L Ch R = 1 ,19766   ,188.8,192.5,195.1
XS GIS Cut Line= 2
2213836.67885688620752.271639244 2214235.5667154620950.914000707
#Sta/Elev= 30
       0 2433.49     9.2 2427.34    44.1  2407.2    53.1 2403.27    62.9    2402
    80.8 2401.85   100.7 2399.78   120.1 2399.01     129  2395.5   133.5 2395.58
     138 2397.01   146.5 2396.69   182.3 2391.84   194.2 2386.18   200.5 2384.88
   213.9 2384.38   227.3 2385.39   265.8 2385.26   271.8  2386.1     281 2387.46
   298.8  2394.9   312.2 2398.44   325.6 2404.38   346.3 2411.29   361.2 2420.51
   374.8 2421.22   391.1 2430.29   401.6  2433.1   417.9 2442.13   445.6 2454.88
#Mann= 3 ,-1,0
       0      .1       0   194.2    .045       0   271.8      .1       0
Bank Sta=194.2,271.8
XS Rating Curve= 0 ,0
Exp/Cntr=0.3,0.1

Type RM Length L Ch R = 1 ,19574   ,269.7,268.9,267.8
XS GIS Cut Line= 2
 2213790.4035742620916.6995110112214128.97136016621139.012093353
#Sta/Elev= 30
       0 2411.68    21.8  2398.6    30.8 2395.51    59.4 2392.81    88.3 2392.25
   102.9 2390.59   121.8 2386.46   157.6 2385.01     172 2382.31   204.9 2380.74
   215.4 2380.79   220.2 2382.34   236.6 2392.06   244.3  2395.1   255.8    2396
   270.1 2394.65   289.2 2394.76   316.5 2401.24   322.3 2404.51   333.8 2413.97
   337.1 2415.45   346.7 2416.16   350.7 2418.02   359.8 2427.33   365.6 2431.87
   375.4 2434.09   385.8  2441.5   394.5 2445.69   400.2 2450.08     405 2452.01
#Mann= 3 ,-1,0
       0      .1       0     172    .045       0   220.2      .1       0
Bank Sta=172,220.2
XS Rating Curve= 0 ,0
Exp/Cntr(USF)=0,0
Exp/Cntr=0.3,0.1

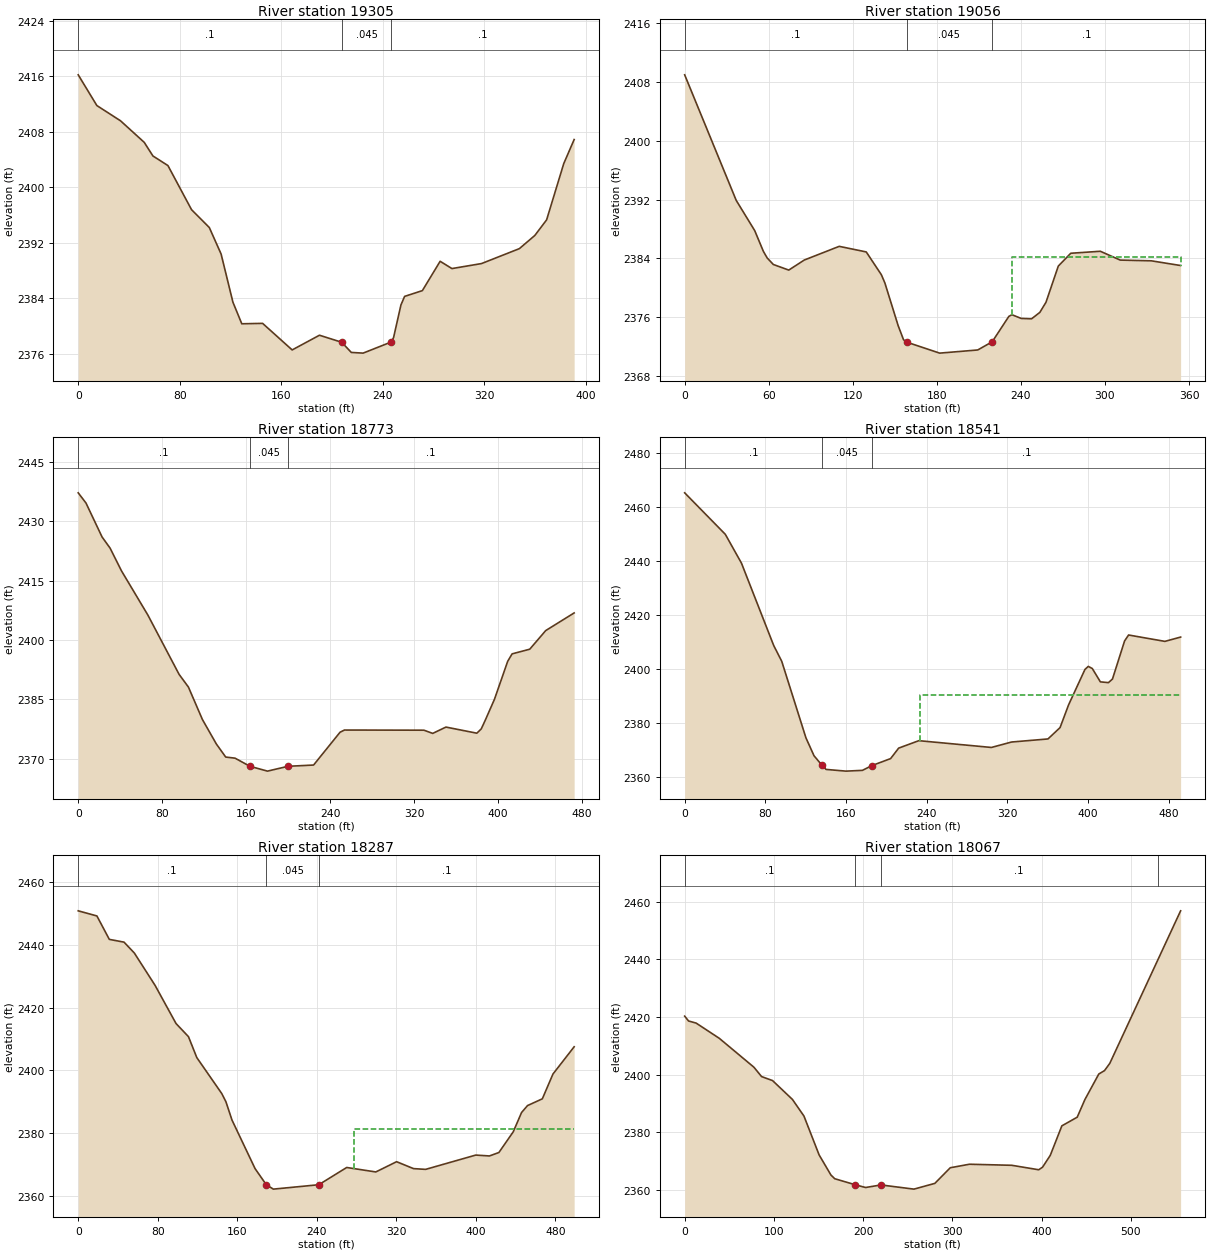
Type RM Length L Ch R = 1 ,19305   ,251.4,248.2,244.6
XS GIS Cut Line= 2
2213619.56755826 621136.966672672213954.77503547621337.815333312
#Sta/Elev= 30
       0 2416.19    14.7 2411.76    33.3 2409.57      52 2406.46    58.9 2404.49
    70.7 2403.11    89.3 2396.75   103.3 2394.18   112.6 2390.36   121.9 2383.42
   128.9  2380.3   145.3 2380.36   168.6 2376.53   190.1 2378.65   207.6 2377.64
   215.2 2376.17   224.5 2376.07  246.73 2377.68   248.5 2378.31   254.3 2383.01
   257.2 2384.25   271.2 2385.08   285.2 2389.31   294.5 2388.26   317.8 2388.98
   347.6 2391.13   359.8 2393.03   369.1 2395.28   382.6 2403.39   390.8 2406.86
#Mann= 3 ,-1,0
       0      .1       0   207.6    .045       0  246.73      .1       0
Bank Sta=207.6,246.73
XS Rating Curve= 0 ,0
Exp/Cntr=0.3,0.1

Type RM Length L Ch R = 1 ,19056   ,282.2,283.3,283.3
XS GIS Cut Line= 2
2213506.90404259621375.6016305242213827.11574376621526.529438719
#Sta/Elev= 30
       0 2408.97    36.8 2391.88      50 2387.77    56.2 2384.94    58.9 2384.05
    63.3 2383.16    74.3  2382.4    85.4 2383.77   110.3 2385.63   129.6 2384.87
   140.4 2381.77   142.9 2380.65   152.4 2374.83   156.2 2372.93   158.4  2372.6
     182  2371.1   209.2 2371.53   219.5 2372.64   231.4  2376.1   233.6 2376.33
   240.2 2375.82   247.6 2375.77   253.5 2376.64   257.9 2378.02   266.7 2382.95
   275.6 2384.69   296.7 2384.96   310.9 2383.76   333.1 2383.66     354 2383.02
#Mann= 3 ,-1,0
       0      .1       0   158.4    .045       0   219.5      .1       0
#XS Ineff= 2 , 0
                           233.8         2384.17
Permanent Ineff=
       F       F
Bank Sta=158.4,219.5
XS Rating Curve= 0 ,0
Exp/Cntr(USF)=0,0
Exp/Cntr=0.3,0.1

Type RM Length L Ch R = 1 ,18773   ,241.6,232.2,222.9
XS GIS Cut Line= 3
2213373.45876303621615.3782772712213567.00648356621708.061511727
 2213812.4050936621787.087523105
#Sta/Elev= 30
       0 2437.25     7.4 2434.67    22.7 2426.09    30.4 2423.24    41.2 2417.51
    66.4 2406.29    96.1  2391.3     105 2388.08   118.3 2379.88   131.6 2373.67
   140.5 2370.37   149.4 2370.09   163.6 2368.03   180.3 2366.81  199.78 2368.03
   224.2 2368.35   249.4 2376.65   253.6 2377.21   329.3 2377.17   337.7 2376.36
   350.3 2377.96   379.7 2376.41   383.9 2377.49   388.1 2379.91   396.5    2385
   409.1 2394.61   413.3 2396.49   430.1 2397.67   445.3 2402.38   472.4 2406.85
#Mann= 3 ,-1,0
       0      .1       0   163.6    .045       0  199.78      .1       0
Bank Sta=163.6,199.78
XS Rating Curve= 0 ,0
Exp/Cntr=0.3,0.1

Type RM Length L Ch R = 1 ,18541   ,260.6,253.5,246.8
XS GIS Cut Line= 2
2213327.88311036621919.8088639892213819.82618247621910.630821598
#Sta/Elev= 30
       0 2465.09    40.3 2449.74    56.3  2439.1    88.3  2408.6    96.3 2402.73
   120.3 2374.41   128.3 2367.79   136.4 2364.18   140.3 2362.72     160 2362.09
   176.3 2362.37  185.83 2364.15   204.3 2366.73   212.3 2370.61   232.3 2373.36
   304.3 2370.85   324.3 2372.86   360.4    2374   372.4  2378.2   380.8 2386.56
   397.1 2399.73   400.4 2400.85   404.4 2400.06   412.4 2395.13   420.4 2394.84
   424.4 2396.18   436.4 2410.26   440.4 2412.47   476.4 2410.11     492  2411.7
#Mann= 3 ,-1,0
       0      .1       0   136.4    .045       0  185.83      .1       0
#XS Ineff= 2 , 0
                          233.75         2390.45
Permanent Ineff=
       F       F
Bank Sta=136.4,185.83
XS Rating Curve= 0 ,0
Exp/Cntr(USF)=0,0
Exp/Cntr=0.3,0.1

Type RM Length L Ch R = 1 ,18287   ,222.3,220.4,220.9
XS GIS Cut Line= 2
2213362.23484225622220.8690959022213838.75770673622073.063271023
#Sta/Elev= 30
       0 2450.83    18.8  2449.2    31.3 2441.74    46.1 2440.86    56.5 2437.38
    77.4 2427.06    98.4 2414.95   110.9 2410.78   119.3 2404.11   144.4 2392.66
   148.6 2390.05   154.7 2384.22   177.9 2368.77  189.16 2363.65   196.3 2362.23
     242 2363.63   270.1 2369.12   299.4  2367.7   320.3 2370.96   337.3 2368.76
   349.5 2368.52   399.9 2373.07   413.7 2372.79   423.2 2373.89   437.6 2380.46
     446 2386.62     452 2388.83   466.9 2390.98   477.6 2398.88   498.9 2407.55
#Mann= 3 ,-1,0
       0      .1       0  189.16    .045       0     242      .1       0
#XS Ineff= 2 , 0
                          277.56         2381.36
Permanent Ineff=
       F       F
Bank Sta=189.16,242
XS Rating Curve= 0 ,0
Exp/Cntr=0.3,0.1

Type RM Length L Ch R = 1 ,18067   ,273.6,277.3,283.3
XS GIS Cut Line= 2
2213440.17468787622445.400580219 2213955.6135485622237.242578809
#Sta/Elev= 30
       0 2420.28     4.3 2418.61    12.9 2417.86    38.8 2412.59    77.6 2402.58
    86.2 2399.33    98.5 2397.94   120.8  2391.4   133.7 2385.64   150.7 2372.17
   163.9 2365.22   168.2 2363.92  191.43  2361.8   202.8 2360.87     220 2361.76
     257 2360.31   280.4  2362.3   297.7 2367.72   319.2 2368.94   366.7 2368.57
   396.9 2367.02   401.2 2367.95   409.8 2372.02   422.8 2382.25     440 2385.25
   448.6 2391.35   464.2 2400.22   470.6  2401.4   476.5  2403.9   555.9 2456.79
#Mann= 4 ,-1,0
       0      .1       0  191.43    .045       0     220      .1       0
     530     .06       0
Bank Sta=191.43,220
XS Rating Curve= 0 ,0
Exp/Cntr(USF)=0,0
Exp/Cntr=0.3,0.1

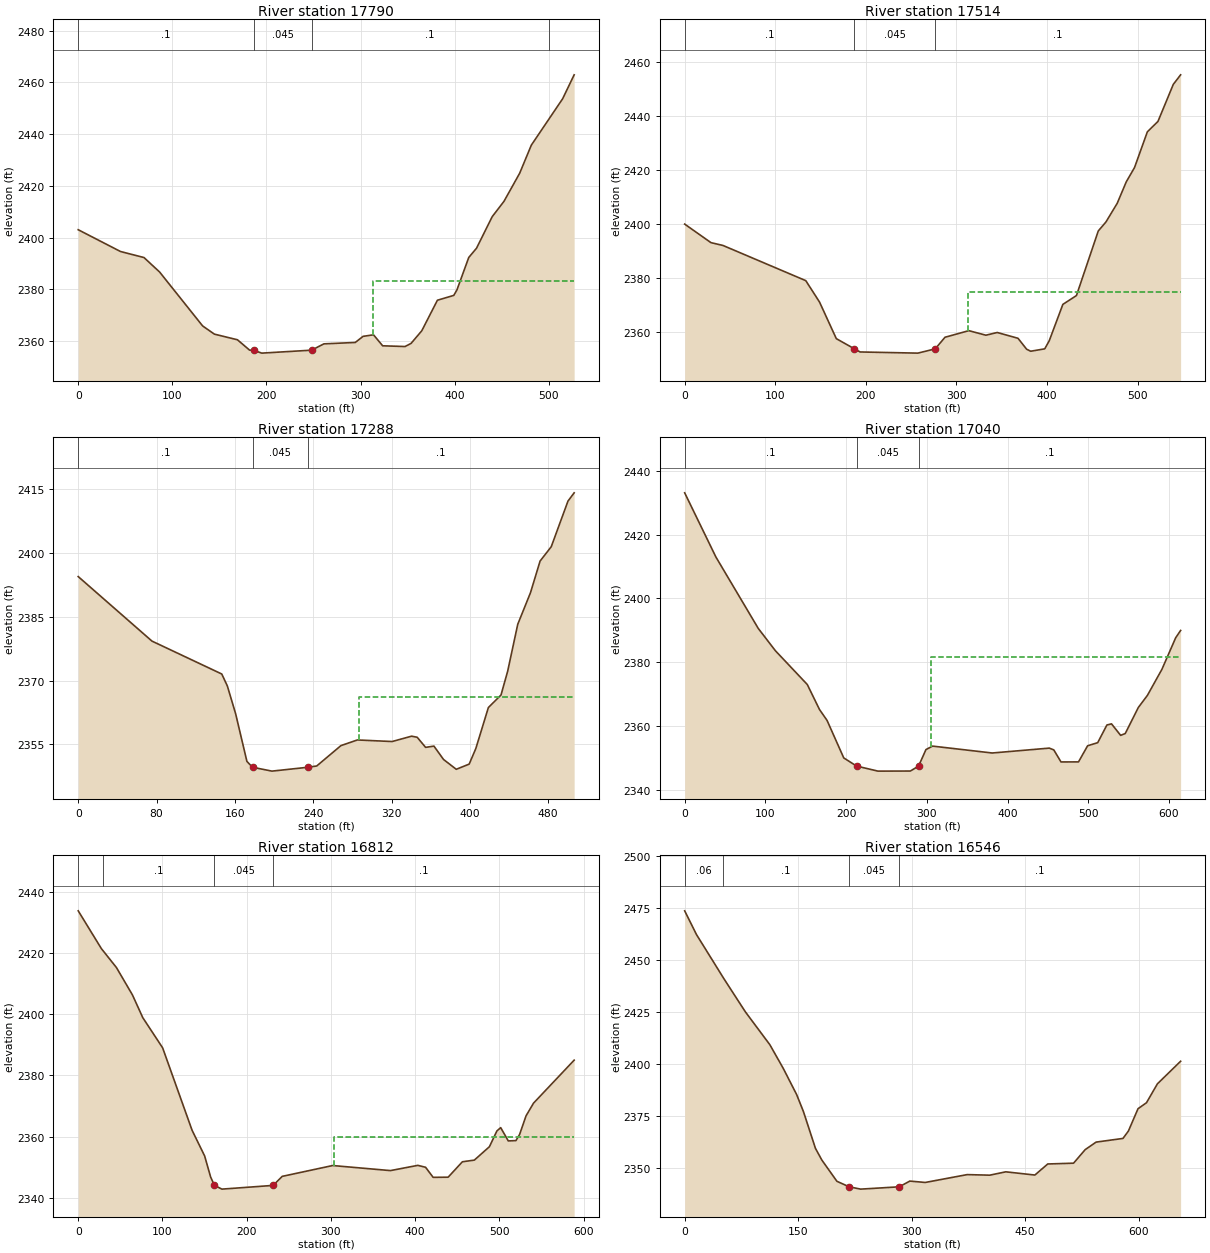
Type RM Length L Ch R = 1 ,17790   ,289.3,275.8,263.8
XS GIS Cut Line= 2
2213544.97217302 622674.912556852214051.93557345622530.918270833
#Sta/Elev= 30
       0 2403.08    44.9 2394.67    69.9 2392.33    86.5 2386.74   132.2 2365.91
   144.7 2362.74   169.2 2360.56   182.1 2356.56   186.3 2356.51   195.1  2355.4
  247.97 2356.54   261.1 2358.98   294.4 2359.52   302.7 2361.88   313.8 2362.48
   323.5 2358.23   347.3 2357.95   353.7 2359.16   365.1 2364.04   381.7 2375.84
   399.1 2377.71   402.5 2379.87     415 2392.35   423.3 2395.96   439.9 2408.11
   452.4 2414.03   469.1  2424.9   481.5 2435.76   514.8  2453.7     527 2462.93
#Mann= 4 ,-1,0
       0      .1       0   186.3    .045       0  247.97      .1       0
     500     .06       0
#XS Ineff= 2 , 0
                          312.72         2383.27
Permanent Ineff=
       F       F
Bank Sta=186.3,247.97
XS Rating Curve= 0 ,0
Exp/Cntr=0.3,0.1

Type RM Length L Ch R = 1 ,17514   ,223.8,225.7,225.9
XS GIS Cut Line= 2
2213686.32978477622990.5762982012214124.12240679622661.818819782
#Sta/Elev= 30
       0 2399.79      29 2392.93    42.3 2391.88   133.7 2378.85   148.9 2370.91
   167.4 2357.37   187.4  2353.6   193.7 2352.44   257.4 2352.01   276.6 2353.59
   287.4 2357.89   313.7 2360.33   332.5 2358.65   345.1 2359.65     368  2357.5
   377.5 2353.46     382 2352.71   397.5  2353.6   402.5 2356.62   417.5 2370.06
   432.5 2373.33   456.6 2397.25   465.1 2400.59   477.5 2407.49   487.5 2415.44
   496.6 2420.72   510.8 2433.97   522.5 2437.82   539.4 2451.52   547.5 2455.07
#Mann= 3 ,-1,0
       0      .1       0   187.4    .045       0   276.6      .1       0
#XS Ineff= 2 , 0
                          312.72         2374.52
Permanent Ineff=
       F       F
Bank Sta=187.4,276.6
XS Rating Curve= 0 ,0
Exp/Cntr(USF)=0,0
Exp/Cntr=0.3,0.1

Type RM Length L Ch R = 1 ,17288   ,250.9,247.8,242.9
XS GIS Cut Line= 2
 2213830.3847422623164.9841676282214231.47577048622855.725986229
#Sta/Elev= 30
       0 2394.42    75.3 2379.27   146.6 2371.54   152.3 2368.74   160.8 2362.19
   172.3 2351.01     178 2349.64   197.9 2348.73   234.6 2349.64   243.6 2349.94
   268.3 2354.72   285.1 2356.05   320.6 2355.68   340.5 2356.94   346.2 2356.68
   354.8 2354.31   363.3 2354.61   373.1 2351.47   386.1 2349.16   399.3 2350.38
   406.1 2354.05   418.9 2363.66   431.8 2366.61   438.6 2372.19   448.9 2383.22
   461.9 2390.63   471.7 2398.06   483.1 2401.43   500.2 2412.15   506.5 2414.09
#Mann= 3 ,-1,0
       0      .1       0     178    .045       0   234.6      .1       0
#XS Ineff= 2 , 0
                           286.6         2366.03
Permanent Ineff=
       F       F
Bank Sta=178,234.6
XS Rating Curve= 0 ,0
Exp/Cntr=0.3,0.1

Type RM Length L Ch R = 1 ,17040   ,236.4,228,213.6
XS GIS Cut Line= 2
2213977.54818265623401.3117719572214414.01508743622968.923997127
#Sta/Elev= 30
       0 2433.11    38.7 2412.99    91.1 2390.65   112.3 2383.66   151.9 2373.05
     167 2365.23   176.4  2361.8   197.1 2350.04  213.07 2347.49   239.5 2345.91
   279.6 2345.94  289.78 2347.49   298.9 2352.66   307.1 2353.75     381 2351.59
   451.7 2353.12   457.3 2352.56   466.2 2348.79   487.9  2348.8   499.2 2353.86
   511.7 2354.83   523.1 2360.37   528.8 2360.72   540.1 2357.12   545.8 2357.69
     562 2365.84   573.3 2369.66   591.3 2377.84   608.3  2387.7   614.4 2389.99
#Mann= 3 ,-1,0
       0      .1       0  213.07    .045       0  289.78      .1       0
#XS Ineff= 2 , 0
                          304.69         2381.58
Permanent Ineff=
       F       F
Bank Sta=213.07,289.78
XS Rating Curve= 0 ,0
Exp/Cntr(USF)=0,0
Exp/Cntr=0.3,0.1

Type RM Length L Ch R = 1 ,16812   ,280.2,266.7,243.2
XS GIS Cut Line= 2
2214227.33888217 623557.735386232214490.89845692  623031.1998863
#Sta/Elev= 30
       0 2433.95    27.5 2421.57    45.4 2415.36    64.4 2406.39    76.7 2398.93
   100.2 2389.07   135.2 2362.04   150.1 2353.63   157.2 2346.74   161.7    2344
   170.6 2342.76  231.44 2343.98   242.2 2346.94   302.1 2350.49   370.7 2348.83
   403.2 2350.55   412.4 2349.92   421.4 2346.62   439.2 2346.67   456.1 2351.72
   470.3 2352.27   488.2 2356.66   497.1 2361.83   501.6 2362.91   510.6 2358.56
   519.7 2358.66     524 2360.65   531.7 2366.78   540.6 2370.94   588.8 2385.02
#Mann= 4 ,-1,0
       0     .06       0      30      .1       0   161.7    .045       0
  231.44      .1       0
#XS Ineff= 2 , 0
                           303.9         2359.72
Permanent Ineff=
       F       F
Bank Sta=161.7,231.44
XS Rating Curve= 0 ,0
Exp/Cntr=0.3,0.1

Type RM Length L Ch R = 1 ,16546   ,257.2,265.3,269
XS GIS Cut Line= 4
2214548.62637582623676.6530436652214573.10115553623501.250455762
2214562.90333065623366.6391673722214681.19809924623044.387901225
#Sta/Elev= 30
       0  2473.8    15.6 2462.37      52 2441.02    80.2 2425.16   112.6 2409.31
   130.3 2397.91     148  2385.3     157 2377.08   172.8 2359.45   181.2 2353.83
   201.2 2343.56   217.3 2340.91   232.6 2339.79  283.53  2340.9   297.5 2343.66
   317.9    2343   373.3 2346.78   403.1 2346.51   424.4 2348.12   462.8 2346.57
   479.8  2351.9   513.9 2352.28   529.3 2358.82   543.7 2362.43   579.2  2364.2
   586.4 2367.75   599.1 2378.51   610.3 2381.39   624.7 2390.48   655.4 2401.37
#Mann= 4 ,-1,0
       0     .06       0      50      .1       0   217.3    .045       0
  283.53      .1       0
Bank Sta=217.3,283.53
XS Rating Curve= 0 ,0
Exp/Cntr(USF)=0,0
Exp/Cntr=0.3,0.1