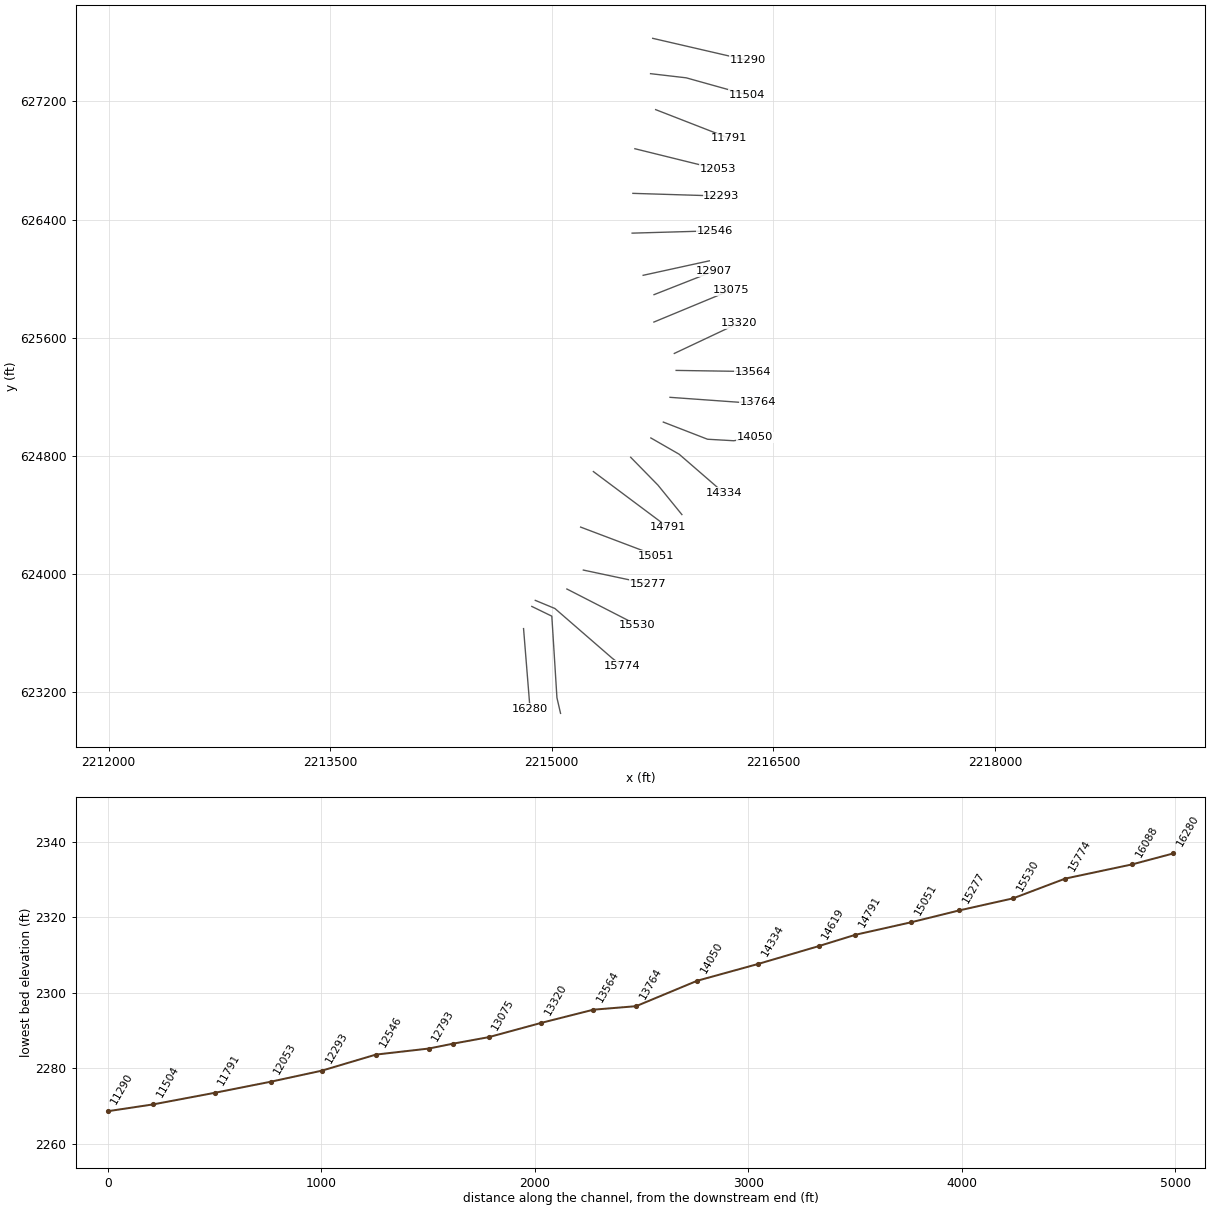
HEC-RAS study LFBUCKRV.prj: LFBUCKRV

--- LFBUCKRV.g01 (geometry) --- (continued)

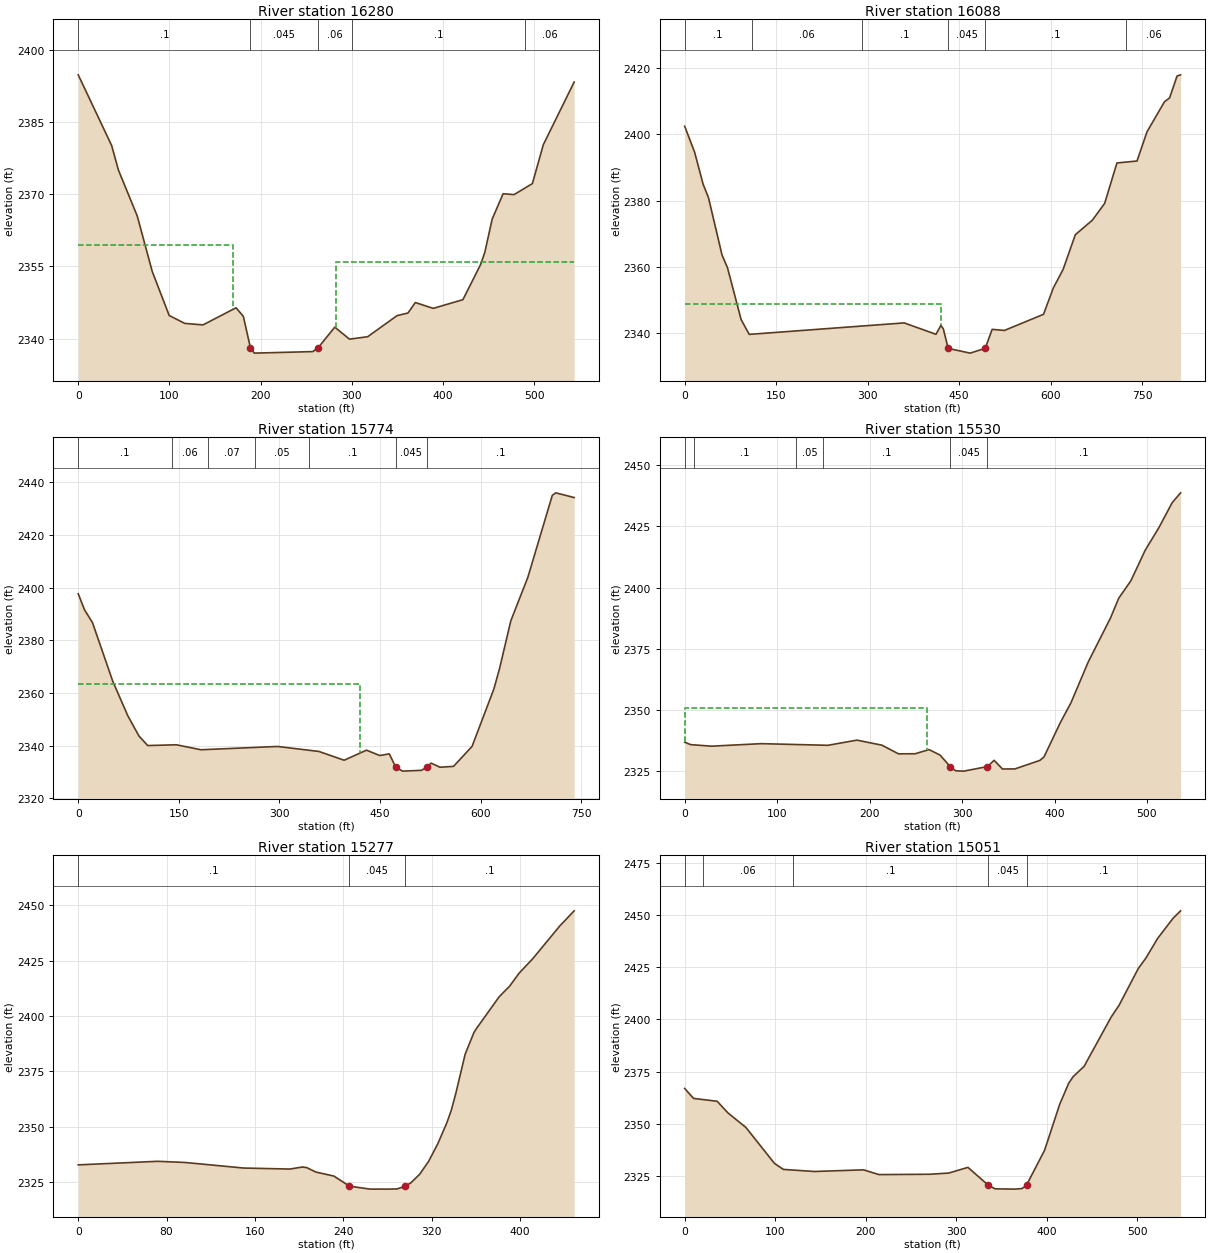
Type RM Length L Ch R = 1 ,16280   ,194.7,192.7,192.2
XS GIS Cut Line= 2
2214809.14542867623629.6680413132214852.92887995623087.577348008
#Sta/Elev= 30
       0 2394.91    36.7 2380.18    44.1 2375.08    64.7 2365.54    81.2 2353.96
    99.8 2344.79   116.9 2343.15   136.9 2342.84   173.1  2346.4   181.1 2344.62
   188.9 2338.05   193.1 2336.96   257.3 2337.28   263.2  2338.1   281.4 2342.37
   297.5 2339.87   317.5 2340.38   349.6 2344.76   361.7 2345.32   369.7 2347.49
   389.4 2346.28   421.9 2348.09   441.4 2355.44   445.9 2357.93     454 2364.87
     466 2370.15     478 2369.97   498.1 2372.26   510.1 2380.36   543.9 2393.41
#Mann= 5 ,-1,0
       0      .1       0   188.9    .045       0   263.2     .06       0
     300      .1       0     490     .06       0
#XS Ineff= 2 , 0
          170.27 2359.46  282.53         2356.03
Permanent Ineff=
       F       F
Bank Sta=188.9,263.2
XS Rating Curve= 0 ,0
Exp/Cntr=0.3,0.1

Type RM Length L Ch R = 1 ,16088   ,293.2,313.9,334.9
XS GIS Cut Line= 4
2214864.98484815623779.7645464732215000.45981264623713.888573532
2215035.06091276623161.5178702432215059.53569247623055.460491511
#Sta/Elev= 30
       0 2402.37    16.3 2394.56    30.2 2384.93    39.1 2380.83    61.2 2363.61
    70.2 2359.78    92.5 2344.17   105.8  2339.7   359.8 2343.16   411.9 2339.73
   419.9 2342.39   423.9  2341.4   431.9 2335.48     468 2334.06   492.7 2335.52
     504 2341.22   524.1 2340.89   588.2 2345.75   604.2 2353.66   620.3 2359.26
   640.3 2369.71   668.4 2374.12   688.4 2379.15   708.5 2391.32   741.4 2391.91
   757.8  2400.7   786.5 2409.76   794.8  2410.9   807.1 2417.51   812.9 2417.86
#Mann= 6 ,-1,0
       0      .1       0     110     .06       0  290.64      .1       0
   431.9    .045       0   492.7      .1       0   724.1     .06       0
#XS Ineff= 2 , 0
          419.94  2348.9
Permanent Ineff=
       F       F
Bank Sta=431.9,492.7
XS Rating Curve= 0 ,0
Exp/Cntr(USF)=0,0
Exp/Cntr=0.3,0.1

Type RM Length L Ch R = 1 ,15774   ,235.3,244.3,246.8
XS GIS Cut Line= 4
2214888.49867232623820.8545996542215021.38914542623765.713588023
 2215408.4396199623429.6943327052215473.89666541623378.748619665
#Sta/Elev= 30
       0 2397.66     9.6 2391.48    21.3  2386.7    51.5 2364.44      74 2351.29
    90.6 2343.63   103.6    2340   146.2  2340.3   183.1 2338.41   297.2 2339.66
   358.9 2337.76   396.5 2334.43   429.8 2338.25   449.6 2336.21   463.8 2336.85
   473.52331.751   483.7 2330.29     512  2330.6   519.32331.807   526.2 2333.32
   539.5 2331.77   559.6  2332.1   587.2 2339.69   619.8 2361.54   628.3 2369.38
     645 2387.41   670.3 2403.86   706.8 2435.02   711.9    2436   739.4 2434.21
#Mann= 7 ,-1,0
       0      .1       0     140     .06       0  193.88     .07       0
  263.88     .05       0  343.88      .1       0   473.5    .045       0
   519.3      .1       0
#XS Ineff= 2 , 0
          419.67 2363.38
Permanent Ineff=
       F       F
Bank Sta=473.5,519.3
XS Rating Curve= 0 ,0
Exp/Cntr=0.3,0.1

Type RM Length L Ch R = 1 ,15530   ,243.3,253,256.1
XS GIS Cut Line= 2
2215102.36655696623897.8008264392215579.62476125623653.053029365
#Sta/Elev= 30
       0 2336.88     6.5 2335.88      29 2335.25    82.9 2336.28   154.9 2335.61
   186.3 2337.72   213.3 2335.66   231.3 2332.12   249.3 2332.16   264.3 2333.86
   276.2 2331.62  287.13 2326.94     293 2325.21   301.9 2325.06  327.49 2326.92
   334.7 2329.48   343.7 2325.93   357.2 2325.97   384.1 2329.43   388.6 2330.83
   406.6  2345.1   417.8 2352.97   436.4 2369.58   460.6 2387.65   469.5 2395.71
   482.6 2402.81     498 2415.22   512.9 2424.51   527.3 2434.74   536.4 2438.74
#Mann= 6 ,-1,0
       0     .06       0      10      .1       0     120     .05       0
     150      .1       0  287.13    .045       0  327.49      .1       0
#XS Ineff= 2 , 0
          261.84  2350.9
Permanent Ineff=
       F       F
Bank Sta=287.13,327.49
XS Rating Curve= 0 ,0
Exp/Cntr(USF)=0,0
Exp/Cntr=0.3,0.1

Type RM Length L Ch R = 1 ,15277   ,230.2,225.9,223.6
XS GIS Cut Line= 2
2215213.78118864624026.0539528412215652.92359834623932.665559415
#Sta/Elev= 30
       0  2332.8      72 2334.41    96.5 2333.89   149.7 2331.37   191.6 2330.91
   202.8 2331.82   206.9 2331.57   215.2 2329.55   231.5 2327.74   245.6 2323.18
   264.2 2321.86   280.5 2321.85   288.7 2321.94   296.1 2323.18     301 2324.62
   309.2 2328.59   317.3 2334.43   325.5 2342.27   333.7 2351.73   337.8 2357.49
   341.9 2365.12   350.3 2382.72   358.2 2392.46   360.2  2394.1   381.1 2408.67
   390.6 2413.48   399.1  2419.3   411.4  2425.8   435.9 2440.59     449 2447.48
#Mann= 3 ,-1,0
       0      .1       0   245.6    .045       0   296.1      .1       0
Bank Sta=245.6,296.1
XS Rating Curve= 0 ,0
Exp/Cntr=0.3,0.1

Type RM Length L Ch R = 1 ,15051   ,266.3,259.4,251.1
XS GIS Cut Line= 2
2215195.40961604624317.1031476152215707.92435237624123.070153442
#Sta/Elev= 30
       0 2366.92     9.8 2362.16    35.9 2360.79    47.9 2355.17    67.6 2348.28
    99.2 2331.03   109.1 2328.14   143.2 2327.15   197.6 2327.94   214.7 2325.66
   270.5 2325.82   291.7 2326.39     313 2329.12   335.6 2320.54     343 2318.84
   364.4  2318.7   372.9 2318.98  377.72 2320.62   397.7 2337.33   414.4 2359.35
   424.2  2369.3   429.1  2372.5   441.4 2377.56   471.3 2401.16   479.8 2406.62
   501.2 2424.37   509.8  2429.5   522.6  2438.8   539.7 2448.48     548 2452.02
#Mann= 5 ,-1,0
       0      .1       0      20     .06       0     120      .1       0
   335.6    .045       0  377.72      .1       0
Bank Sta=335.6,377.72
XS Rating Curve= 0 ,0
Exp/Cntr(USF)=0,0
Exp/Cntr=0.3,0.1

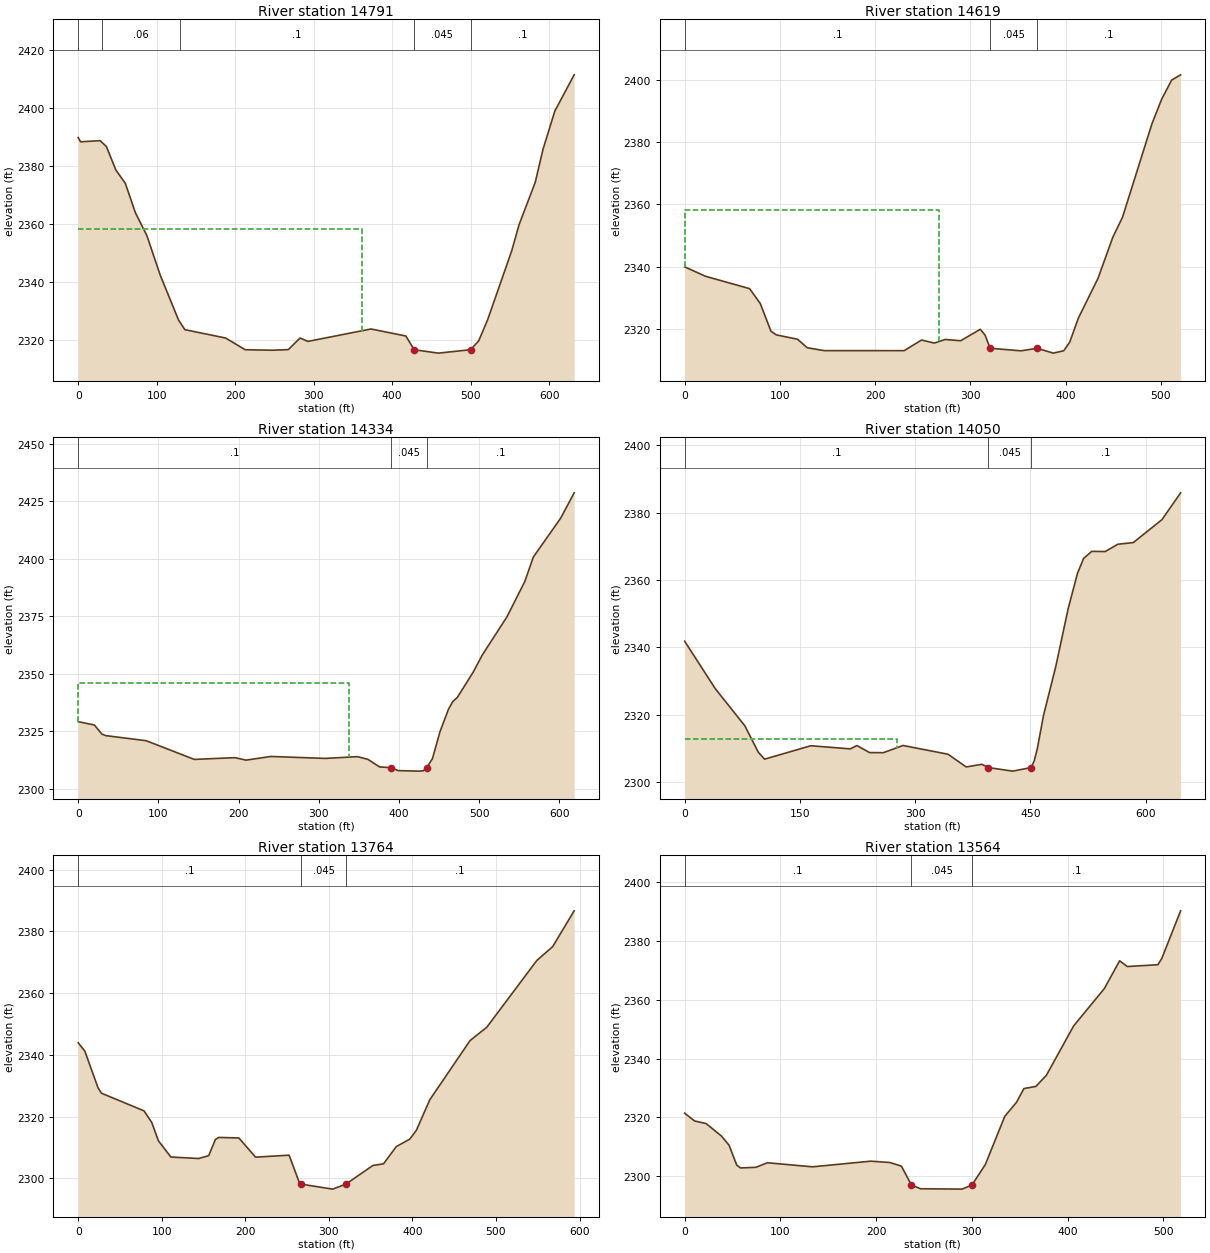
Type RM Length L Ch R = 1 ,14791   ,178.5,172.8,163.6
XS GIS Cut Line= 2
     2215281.797      624693.0822215787.88965095624314.642837817
#Sta/Elev= 30
       0  2389.9       3 2388.41    27.9  2388.8    35.9 2386.79    47.9 2378.69
      60 2374.07    72.9 2363.89    87.4 2356.08   104.5 2342.35   127.8 2326.87
   135.9 2323.51   187.8 2320.63   212.7 2316.59     247 2316.41   267.7 2316.62
   282.7 2320.63   292.7 2319.46   373.1 2323.75   417.5 2321.32   428.1 2316.58
   458.9 2315.41  499.96 2316.59   510.3 2319.66   521.7 2326.96   552.4  2350.8
   561.7 2359.76   582.3  2374.4   592.3 2385.89   607.3 2399.04   631.9 2411.54
#Mann= 5 ,-1,0
       0      .1       0      30     .06       0     130      .1       0
   428.1    .045       0  499.96      .1       0
#XS Ineff= 2 , 0
          362.11 2358.26
Permanent Ineff=
       T       F
Bank Sta=428.1,499.96
XS Rating Curve= 0 ,0
Exp/Cntr=0.3,0.1

Type RM Length L Ch R = 1 ,14619   ,277.8,284.2,284.7
XS GIS Cut Line= 3
2215534.16610707  624789.94054952215718.83199118624601.260189649
2215880.74917942624401.874561155
#Sta/Elev= 30
       0 2340.02    21.8 2337.01    68.2 2333.04    79.4 2328.29    90.6 2319.42
    96.2 2318.24   118.6 2316.83   128.7 2314.12   146.6 2313.19   230.5 2313.18
   248.8 2316.58   262.2 2315.61   273.6 2316.76   289.9 2316.36   310.5 2320.03
   315.6 2318.14   320.8 2313.95   353.2 2313.13   370.2 2313.93   387.3 2312.39
   398.1 2313.15   404.4  2315.9   413.5  2323.6   434.2 2336.39   449.6 2349.43
   459.9 2355.94   490.8 2385.85     501 2393.72   511.5 2399.84   520.9 2401.52
#Mann= 3 ,-1,0
       0      .1       0   320.8    .045       0   370.2      .1       0
#XS Ineff= 2 , 0
          266.67 2358.26
Permanent Ineff=
       T       F
Bank Sta=320.8,370.2
XS Rating Curve= 0 ,0
Exp/Cntr(USF)=0,0
Exp/Cntr=0.3,0.1

Type RM Length L Ch R = 1 ,14334   ,257.7,284.1,293.8
XS GIS Cut Line= 3
 2215670.6540313624920.8325799482215861.91678414624810.858144611
2216162.63705092624550.227910574
#Sta/Elev= 30
       0 2329.16    20.2  2327.7    29.4 2323.79    34.1  2323.1    84.8 2320.88
   144.8 2312.75   195.5 2313.51   209.4 2312.44   240.4 2314.03   308.5 2313.18
   348.2 2313.96   361.2  2312.8   375.9  2309.5   390.7 2309.12   399.2 2307.88
   424.7 2307.66   430.4 2307.79  434.43 2309.07   441.8 2313.04   451.2 2324.73
   461.8 2334.51   467.1 2337.82     473 2339.75   492.8 2350.77   504.1 2358.16
   534.7 2374.65   557.1  2390.1   567.7 2400.69   601.9 2417.64   618.6 2428.59
#Mann= 3 ,-1,0
       0      .1       0   390.7    .045       0  434.43      .1       0
#XS Ineff= 2 , 0
          337.89 2346.17
Permanent Ineff=
       F       F
Bank Sta=390.7,434.43
XS Rating Curve= 0 ,0
Exp/Cntr=0.3,0.1

Type RM Length L Ch R = 1 ,14050   ,281.8,286,281.9
XS GIS Cut Line= 4
2215755.14139836 625028.280496022216054.38844909 624912.12164044
2216231.17391731624901.9891036672216377.06034014624923.970713811
#Sta/Elev= 30
       0 2341.82    39.7 2327.77    78.3  2316.7    95.9 2308.83   104.1 2306.79
   164.2 2310.77   215.6 2309.84   224.2 2310.83   240.7 2308.74   258.6 2308.71
   284.3 2310.85   342.8 2308.25   366.5 2304.47   386.9 2305.25  395.38 2304.29
     427 2303.23     451 2304.29     455 2306.28     459 2309.84     467 2319.65
   483.1 2334.33   499.1 2351.38   511.2  2361.9   519.3 2366.41   529.9 2368.52
   547.5 2368.47   563.8 2370.63     584 2371.13   621.3 2377.94   645.6 2385.91
#Mann= 3 ,-1,0
       0      .1       0  395.38    .045       0     451      .1       0
#XS Ineff= 2 , 0
          276.68 2312.66
Permanent Ineff=
       F       F
Bank Sta=395.38,451
XS Rating Curve= 0 ,0
Exp/Cntr(USF)=0,0
Exp/Cntr=0.3,0.1

Type RM Length L Ch R = 1 ,13764   ,198.2,199.9,201.9
XS GIS Cut Line= 3
 2215800.4050681625195.9909096592216264.54689298625162.702824878
2216392.70397034 625167.25582839
#Sta/Elev= 30
       0 2343.87     7.8 2341.28    23.8 2329.27    27.8 2327.57    78.8 2321.84
      88  2318.1      96 2312.16   110.9  2306.9   144.1 2306.41   156.2 2307.34
   164.2 2312.58   168.2 2313.24   192.3 2313.07   212.3 2306.85   252.4  2307.5
   264.3 2298.88  267.03  2298.1   304.6  2296.5   320.5 2298.14   352.7 2304.16
   365.4 2304.69   380.7 2310.27   396.8 2312.68   404.8 2315.58   420.8 2325.43
     469 2344.61     489 2348.91     549 2370.57   567.9 2375.03   593.6 2386.62
#Mann= 3 ,-1,0
       0      .1       0  267.03    .045       0   320.5      .1       0
Bank Sta=267.03,320.5
XS Rating Curve= 0 ,0
Exp/Cntr=0.3,0.1

Type RM Length L Ch R = 1 ,13564   ,235.7,244.2,253.9
XS GIS Cut Line= 2
2215841.78545407625378.2547214152216359.78530242625370.450580574
#Sta/Elev= 30
       0 2321.42    10.4 2318.77    22.4 2317.89    38.4 2313.65    46.4 2310.51
    54.4 2303.73    58.4 2302.78    74.4    2303    86.4 2304.55   133.5 2303.16
   194.4 2305.09   214.4 2304.63   226.4  2303.4   236.9 2296.96   246.4  2295.7
   289.7 2295.57   300.1 2296.96   314.1 2303.95   334.4 2320.35   346.6  2325.1
   354.4  2329.8   366.9 2330.54   377.8 2334.29   406.4 2351.15   438.4 2363.83
   454.4  2373.3   462.4 2371.34   494.4 2371.96   498.4 2374.07   518.1  2390.3
#Mann= 3 ,-1,0
       0      .1       0   236.9    .045       0   300.1      .1       0
Bank Sta=236.9,300.1
XS Rating Curve= 0 ,0
Exp/Cntr(USF)=0,0
Exp/Cntr=0.3,0.1

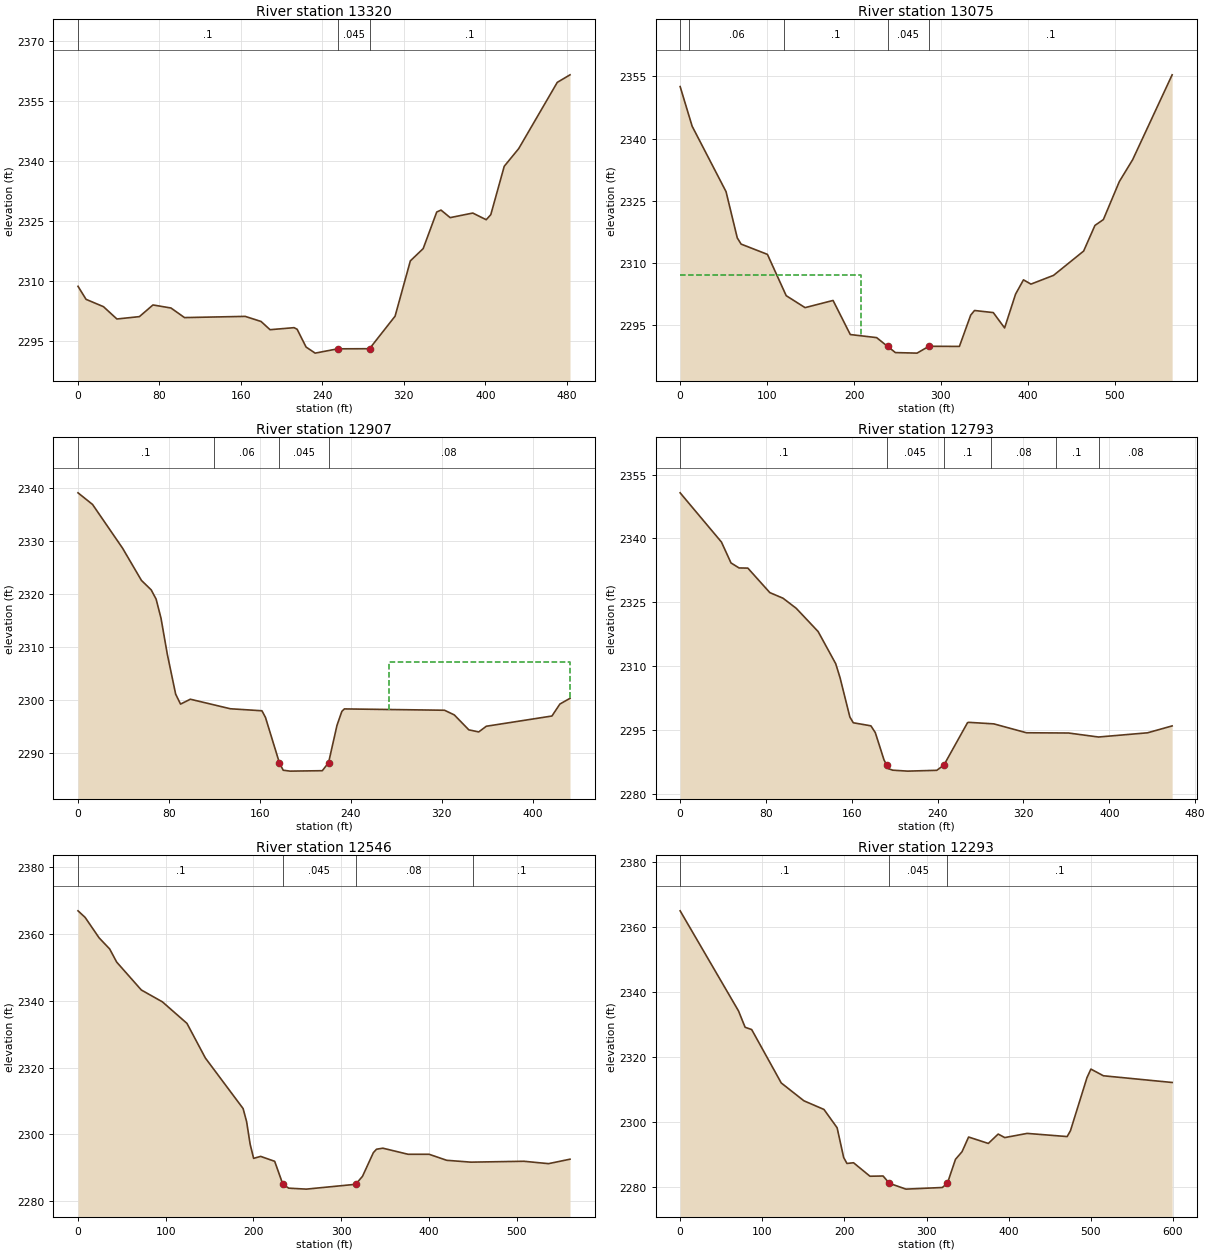
Type RM Length L Ch R = 1 ,13320   ,249,245.6,244.4
XS GIS Cut Line= 2
2215829.60168461625493.2244362352216266.52386791 625699.47270301
#Sta/Elev= 30
       0 2308.74     7.9 2305.49      25 2303.66    38.2 2300.59    60.3 2301.18
    73.6 2304.09    91.3 2303.33   104.6 2300.94   164.2 2301.24   179.8 2299.97
   188.6 2297.92   212.2 2298.43   215.2 2298.03     224 2293.59   232.9 2292.08
     255 2293.15  286.29 2293.18   311.4 2301.29   326.4 2315.08     339 2318.14
   352.3 2327.26   356.5 2327.74   365.5 2325.86   387.7    2327   400.9 2325.34
   405.4  2326.6   418.6 2338.66   432.8 2343.06   470.7 2359.58   483.2 2361.46
#Mann= 3 ,-1,0
       0      .1       0     255    .045       0  286.29      .1       0
Bank Sta=255,286.29
XS Rating Curve= 0 ,0
Exp/Cntr=0.3,0.1

Type RM Length L Ch R = 1 ,13075   ,168.3,167.7,167.3
XS GIS Cut Line= 2
2215691.44418254625705.7867162052216214.12892408625922.568406246
#Sta/Elev= 30
       0 2352.57    13.8 2343.01    52.8 2327.23    65.7 2316.09    70.1 2314.59
   100.4 2312.11     122 2302.15   143.7 2299.27   175.9    2301   195.7 2292.78
     226 2292.04   238.6 2289.92   247.6 2288.43   272.5  2288.3   286.1 2289.95
   321.2 2289.92   334.2 2297.46   338.6 2298.58   360.2 2298.07   373.2 2294.37
   385.8 2302.52   394.9 2305.97   403.5 2304.94   429.5 2307.05   464.1 2312.91
   477.1 2319.09   486.8  2320.5   505.1 2329.64   520.5 2334.95   565.9  2355.4
#Mann= 5 ,-1,0
       0      .1       0      10     .06       0     120      .1       0
   238.6    .045       0   286.1      .1       0
#XS Ineff= 2 , 0
          207.65 2307.02
Permanent Ineff=
       F       F
Bank Sta=238.6,286.1
XS Rating Curve= 0 ,0
Exp/Cntr(USF)=0,0
Exp/Cntr=0.3,0.1

Type RM Length L Ch R = 1 ,12907   ,118.7,113.4,109.9
XS GIS Cut Line= 2
2215692.22975583625891.3198553462216094.94559646  626049.9114917
#Sta/Elev= 30
       0 2339.09    12.8 2336.89    39.2 2328.64    55.8 2322.56    64.4 2320.77
    68.7 2319.03      73 2315.44    78.5 2308.69    85.9 2301.09    90.2 2299.22
    98.8 2300.14     134 2298.34   161.8 2297.96   164.9 2296.71   177.2 2288.11
   180.5 2286.74   186.5 2286.57   214.9 2286.65   220.4 2288.16   227.8  2295.2
   232.1 2297.85   234.3 2298.31   322.4 2298.06     331 2297.18   343.8 2294.36
   352.5 2293.97   359.2 2295.04   416.9 2296.97   423.9 2299.23   432.8 2300.31
#Mann= 4 ,-1,0
       0      .1       0     120     .06       0   177.2    .045       0
   220.4     .08       0
#XS Ineff= 2 , 0
                          273.22         2307.07
Permanent Ineff=
       F       F
Bank Sta=177.2,220.4
XS Rating Curve= 0 ,0
Exp/Cntr(USF)=0,0
Exp/Cntr=0.3,0.1

Type RM Length L Ch R = 1 ,12793   ,254.2,247.6,244.1
XS GIS Cut Line= 2
2215618.52758346626022.3932069472216066.45845128 626120.51282043
#Sta/Elev= 30
       0 2350.71    38.5 2339.14    47.4 2334.23    54.9 2333.05    63.1 2333.01
    83.6 2327.25    95.9 2325.93   108.2 2323.56   128.6  2318.1     145 2310.54
   149.1  2307.2   158.2 2298.01   161.4 2296.65   177.8 2295.93   181.9 2294.34
     190 2287.94   192.5 2286.68   194.1 2285.85   198.2  2285.5     212 2285.28
   239.2 2285.47  245.83 2286.69   267.9 2296.68   269.1 2296.75   292.4 2296.39
   322.8  2294.3     362 2294.24     390  2293.3   435.7 2294.29   458.6 2295.91
#Mann= 6 ,-1,0
       0      .1       0   192.5    .045       0  245.83      .1       0
     290     .08       0     350      .1       0     390     .08       0
Bank Sta=192.5,245.83
XS Rating Curve= 0 ,0
Exp/Cntr=0.3,0.1

Type RM Length L Ch R = 1 ,12546   ,256.3,253.2,250.8
XS GIS Cut Line= 2
2215544.04431992626307.9888640332216104.73276515626324.046766999
#Sta/Elev= 30
       0 2366.81     8.1 2364.85    24.1 2358.72    36.1 2355.41    44.1 2351.49
    72.2 2343.16    96.2 2339.62   124.2 2333.19   145.2 2322.84   188.2 2307.75
   192.2 2303.85   196.2 2297.15   200.2 2292.87   208.2 2293.46   224.2 2291.99
  233.51 2285.14   240.2 2283.97   260.2 2283.68   316.4 2285.12   324.3 2287.49
   336.7 2294.57   340.3  2295.6   347.5 2295.91   376.3 2294.09   400.3 2294.09
   420.3 2292.29   447.9 2291.74   508.3    2292   536.4 2291.29   560.9 2292.62
#Mann= 4 ,-1,0
       0      .1       0  233.51    .045       0   316.4     .08       0
     450      .1       0
Bank Sta=233.51,316.4
XS Rating Curve= 0 ,0
Exp/Cntr(USF)=0,0
Exp/Cntr=0.3,0.1

Type RM Length L Ch R = 1 ,12293   ,246,239.8,232.8
XS GIS Cut Line= 2
2215549.15681102626577.3887618482216147.87290344626559.012619076
#Sta/Elev= 30
       0 2364.88    71.1 2334.12    79.1 2329.12    87.1 2328.42   123.1 2312.02
   150.7 2306.54   175.1 2303.89   191.1 2298.27   199.1 2289.12   203.1  2287.3
   211.1 2287.52   231.1 2283.38   247.1 2283.45   254.7 2281.21   274.9 2279.42
   319.2 2279.92   325.4 2281.24   335.2 2288.56   343.2 2290.91   351.2 2295.42
   375.2 2293.45   387.2 2296.33   395.2 2295.25   422.5 2296.53   471.2 2295.56
   475.2 2297.36   495.3 2313.65   500.1 2316.28   515.3 2314.23     599 2312.17
#Mann= 3 ,-1,0
       0      .1       0   254.7    .045       0   325.4      .1       0
Bank Sta=254.7,325.4
XS Rating Curve= 0 ,0
Exp/Cntr=0.3,0.1

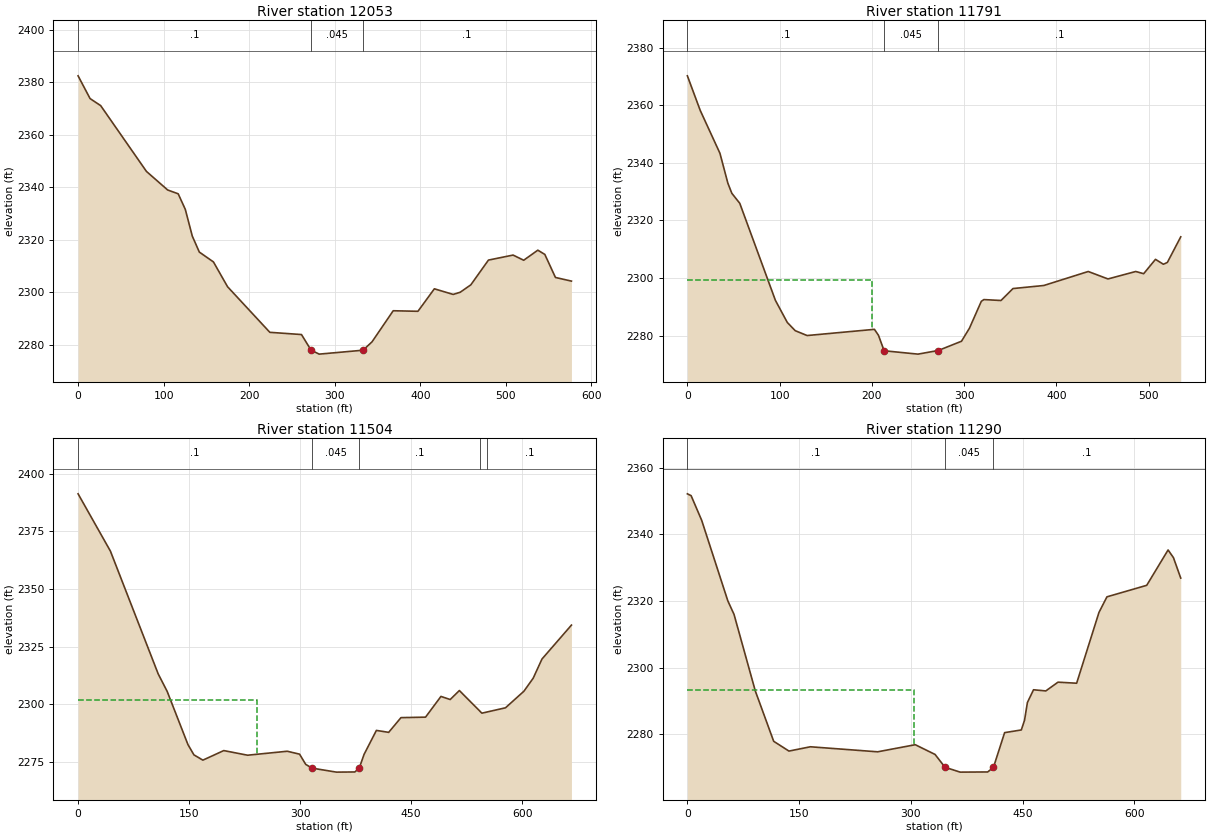
Type RM Length L Ch R = 1 ,12053   ,265.1,261.6,257.5
XS GIS Cut Line= 2
2215562.56959794626879.6861331612216122.31687458626741.448951481
#Sta/Elev= 30
       0 2382.41      14 2373.76    26.4 2371.07    79.9 2346.03   104.7 2338.96
     117 2337.51   125.3 2331.59   133.5  2321.4   141.7 2315.33   158.2 2311.58
   174.7 2302.14   224.1 2284.79   261.1 2283.94   272.3    2278   281.8 2276.49
     333 2277.98   343.5 2281.15   368.3    2293   397.2 2292.79   416.4 2301.35
   438.4 2299.21   446.6 2300.04     459 2302.86   479.6 2312.28   508.4 2314.19
   520.8 2312.22   537.3 2316.05   545.5 2314.44   557.9 2305.67   576.6 2304.28
#Mann= 3 ,-1,0
       0      .1       0   272.3    .045       0     333      .1       0
Bank Sta=272.3,333
XS Rating Curve= 0 ,0
Exp/Cntr(USF)=0,0
Exp/Cntr=0.3,0.1

Type RM Length L Ch R = 1 ,11791   ,284.4,287.5,290.3
XS GIS Cut Line= 2
2215703.24866937627144.4821489442216201.68090179626950.340315882
#Sta/Elev= 30
       0 2370.25    13.9 2358.25    35.3 2343.34    43.9 2332.94    48.2 2329.44
    56.8 2325.96    95.4 2292.27   108.3 2284.57   116.9 2281.71   129.8 2280.02
   202.8 2282.17   207.2 2280.09   213.3 2274.73     250 2273.56     272 2274.82
   297.2 2278.04   305.8 2282.56   318.7 2291.92   321.5 2292.51     340 2292.19
     353 2296.34   386.4  2297.4   434.6 2302.27     456 2299.68   486.1 2302.27
   494.7  2301.5   507.5 2306.49   516.1 2304.78   520.4 2305.42   534.9 2314.31
#Mann= 3 ,-1,0
       0      .1       0   213.3    .045       0     272      .1       0
#XS Ineff= 2 , 0
             200 2299.26
Permanent Ineff=
       F       F
Bank Sta=213.3,272
XS Rating Curve= 0 ,0
Exp/Cntr=0.3,0.1

Type RM Length L Ch R = 1 ,11504   ,212.9,214,215.7
XS GIS Cut Line= 3
2215668.72406783627388.0009579922215909.92302185627359.916148278
2216317.97878652627245.924861791
#Sta/Elev= 30
       0 2391.29    43.7 2366.41   108.2 2313.15   120.3 2305.58   148.4 2282.48
   156.5 2277.99   168.6  2275.7   196.8 2279.85     229 2277.84   282.6 2279.56
   299.2  2278.3   307.5 2273.88   315.8 2272.25     349  2270.5   373.9 2270.57
  379.79 2272.23   386.4 2278.23     403 2288.61   419.6 2287.76   436.2 2294.15
   469.4 2294.36   490.2 2303.36   502.7 2302.01   515.1 2305.91   545.5 2296.09
   577.4 2298.42   602.3 2305.62   614.8 2311.25   626.7 2319.59   666.5 2334.31
#Mann= 5 ,-1,0
       0      .1       0   315.8    .045       0  379.79      .1       0
  542.83    .025       0  552.83      .1       0
#XS Ineff= 2 , 0
          242.26 2301.74
Permanent Ineff=
       F       F
Bank Sta=315.8,379.79
XS Rating Curve= 0 ,0
Exp/Cntr(USF)=0,0
Exp/Cntr=0.3,0.1

Type RM Length L Ch R = 1 ,11290   ,276.3,282,288
XS GIS Cut Line= 2
 2215683.2919041627627.345610146  2216328.718672627478.013169562
#Sta/Elev= 30
       0 2352.11       5 2351.56    19.2 2344.17    54.3 2320.03    62.6 2315.99
    91.2 2293.02   115.9 2277.92   136.4 2274.99   165.1 2276.28   255.5 2274.77
     306  2276.9   332.6 2273.98     346 2270.13   366.3 2268.68   403.3 2268.73
  410.99 2270.11     426 2280.52   448.4 2281.32   452.7 2284.19   456.6 2289.56
   464.8 2293.37   481.3 2293.02   497.7 2295.65   522.7 2295.33   552.7 2316.56
   563.4 2321.23   616.8 2324.68   645.5 2335.28   652.7 2332.98   662.5 2326.85
#Mann= 3 ,-1,0
       0      .1       0     346    .045       0  410.99      .1       0
#XS Ineff= 2 , 0
          304.74 2293.25
Permanent Ineff=
       F       F
Bank Sta=346,410.99
XS Rating Curve= 0 ,0
Exp/Cntr=0.3,0.1