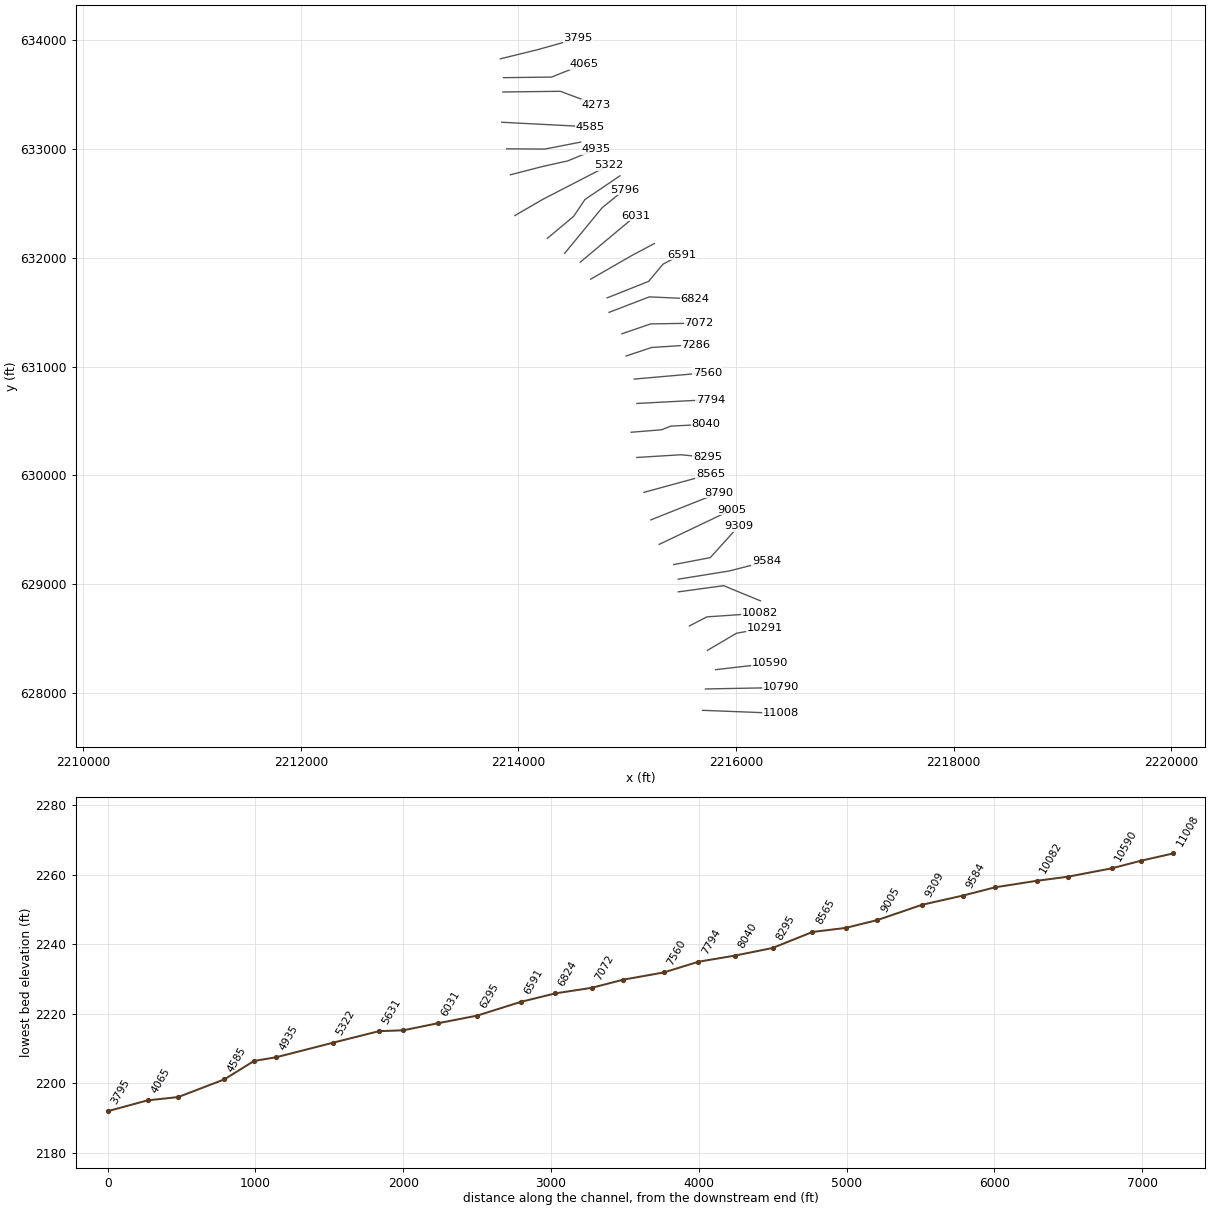
HEC-RAS study LFBUCKRV.prj: LFBUCKRV

--- LFBUCKRV.g01 (geometry) --- (continued)

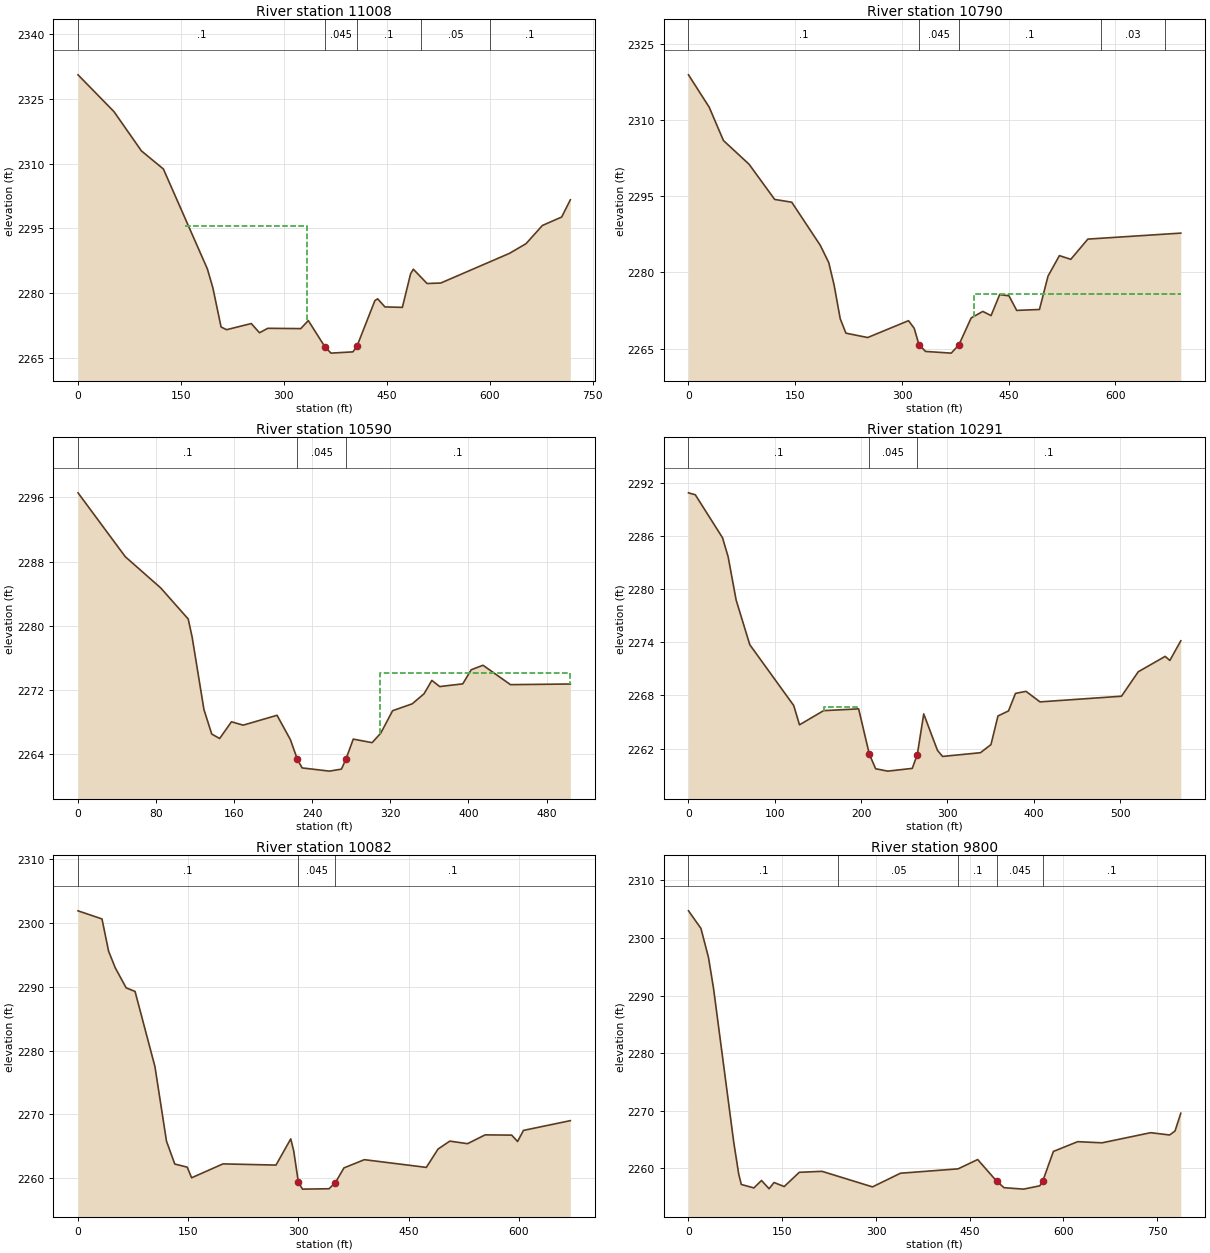
Type RM Length L Ch R = 1 ,11008   ,216.8,218.1,219.5
XS GIS Cut Line= 2
2215691.85273465627837.3579134192216408.84140618627809.273103705
#Sta/Elev= 30
       0 2330.53    52.4 2322.02    92.4 2312.94   124.4 2308.76   188.5 2285.66
   196.5 2281.29   208.5 2272.22   216.5  2271.6   252.5 2273.02   264.5 2270.89
   276.5 2271.92   324.6 2271.85   335.6 2273.71  359.58  2267.7   368.6 2266.18
   400.6 2266.47  406.37 2267.72   432.7 2278.34   436.7 2278.74   447.3 2276.86
   472.7 2276.76   484.7 2284.52   488.7 2285.58   508.7 2282.28   528.7 2282.39
   628.8 2289.25   652.8 2291.47   676.8  2295.7   704.9 2297.65   717.5 2301.63
#Mann= 5 ,-1,0
       0      .1       0  359.58    .045       0  406.37      .1       0
     500     .05       0     600      .1       0
#XS Ineff= 1 ,-1
  155.92   333.7 2295.67
Permanent Ineff=
       F
Bank Sta=359.58,406.37
XS Rating Curve= 0 ,0
Exp/Cntr(USF)=0,0
Exp/Cntr=0.3,0.1

Type RM Length L Ch R = 1 ,10790   ,197.4,199.9,202.5
XS GIS Cut Line= 3
2215719.06023886628033.9221905212216238.34909644628043.540142891
2216410.65995166 628050.24495237
#Sta/Elev= 30
       0 2318.86    29.1 2312.49    49.1 2305.93    85.1 2301.27   121.1 2294.34
   145.1 2293.79   185.1 2285.33   197.1 2281.91   204.6 2277.51   213.2 2270.87
   221.2 2268.02   251.8 2267.16   309.2 2270.48   317.2 2268.97   323.9 2265.74
   333.2 2264.42   369.2 2264.09  380.04 2265.73   397.2 2271.01   413.6  2272.3
   425.2 2271.48   437.2 2275.59   450.3 2275.38   461.2  2272.5   493.2 2272.68
   505.2 2279.24   521.2 2283.28   537.2 2282.55   561.2 2286.53   691.8 2287.71
#Mann= 5 ,-1,0
       0      .1       0   323.9    .045       0  380.04      .1       0
  579.38     .03       0  669.38      .1       0
#XS Ineff= 2 , 0
                          400.79          2275.8
Permanent Ineff=
       F       F
Bank Sta=323.9,380.04
XS Rating Curve= 0 ,0
Exp/Cntr=0.3,0.1

Type RM Length L Ch R = 1 ,10590   ,287.2,298.6,308.4
XS GIS Cut Line= 2
2215812.05929856628211.3311912572216313.12534482628269.318063079
#Sta/Elev= 30
       0 2296.57    48.4 2288.61    84.7 2284.72   112.9 2280.84   116.9  2278.6
     129 2269.56     137  2266.5   145.1 2265.95   157.2 2268.03   169.2 2267.61
   203.9 2268.84   217.6  2265.8   224.8 2263.33   229.6 2262.28   257.6 2261.88
   269.9 2262.13  274.42 2263.36     282 2265.87   301.3 2265.43   310.2 2266.62
   322.3 2269.41   342.4 2270.27   354.5 2271.52   362.5 2273.19   370.6 2272.42
   394.2 2272.76   402.8 2274.51   414.9 2275.08   443.1 2272.66   504.4 2272.74
#Mann= 3 ,-1,0
       0      .1       0   224.8    .045       0  274.42      .1       0
#XS Ineff= 2 , 0
                          309.29         2274.14
Permanent Ineff=
       F       F
Bank Sta=224.8,274.42
XS Rating Curve= 0 ,0
Exp/Cntr(USF)=0,0
Exp/Cntr=0.3,0.1

Type RM Length L Ch R = 1 ,10291   ,222.7,209.7,198.3
XS GIS Cut Line= 3
 2215737.3085318628389.1782198082216004.61497754628546.506123093
2216260.65603188628592.363242585
#Sta/Elev= 30
       0 2290.88     7.9 2290.66    39.4 2285.81    45.9 2283.67    55.2 2278.77
      71 2273.73   121.9 2266.86   128.6 2264.68   156.5 2266.28   197.1 2266.48
   209.5 2261.37   216.8 2259.72   230.8 2259.45   259.2 2259.76  265.04 2261.31
   272.5 2265.91   288.4  2261.8   294.3 2261.11   338.2 2261.53   350.4 2262.45
   358.5 2265.68   370.7 2266.25   378.8 2268.23     391 2268.46   407.2 2267.27
   501.6 2267.91     521 2270.67   552.2 2272.41   557.6 2271.95   570.3 2274.17
#Mann= 3 ,-1,0
       0      .1       0   209.5    .045       0  265.04      .1       0
#XS Ineff= 1 ,-1
  156.85  194.82 2266.69
Permanent Ineff=
       F
Bank Sta=209.5,265.04
XS Rating Curve= 0 ,0
Exp/Cntr=0.3,0.1

Type RM Length L Ch R = 1 ,10082   ,290.3,281.5,270
XS GIS Cut Line= 3
 2215571.2444878628613.7538285452215731.82351746628697.017029109
2216219.80534648628730.470993622
#Sta/Elev= 30
       0 2301.93    32.6 2300.66    41.6  2295.6    50.6 2293.01    65.5 2289.85
    77.6 2289.29   104.7 2277.49   120.4  2265.8   131.7 2262.21   148.6 2261.73
   154.6 2260.06   197.3 2262.24   269.4 2262.05   289.5 2266.16   293.5  2264.3
   299.9 2259.35   305.5 2258.28   341.6 2258.34  350.27 2259.31   361.9 2261.61
   389.7  2262.9     474 2261.69     490 2264.57     506 2265.81   530.1 2265.41
   554.1 2266.79   590.2 2266.75   598.2 2265.75   606.2 2267.49     670 2269.02
#Mann= 3 ,-1,0
       0      .1       0   299.9    .045       0  350.27      .1       0
Bank Sta=299.9,350.27
XS Rating Curve= 0 ,0
Exp/Cntr(USF)=0,0
Exp/Cntr=0.3,0.1

Type RM Length L Ch R = 1 ,9800    ,185.6,216,227.6
XS GIS Cut Line= 3
2215468.48742722628927.023511229 2215886.1439964628984.024281674
2216224.69490879628844.537039089
#Sta/Elev= 30
       0 2304.73    19.9 2301.68      32 2296.63    40.1 2291.25    72.4 2264.56
    80.4    2259    84.5 2257.22   104.6 2256.62   116.8 2257.91   128.9 2256.48
   136.9 2257.56   153.1 2256.86   177.3 2259.33   213.6  2259.5   294.4  2256.8
   339.1 2259.17   431.4 2259.93   462.7 2261.55   492.9 2257.81   504.9 2256.66
   536.2 2256.41   562.2 2256.99  566.96 2257.85   583.8 2262.95   622.7 2264.65
   661.7 2264.45   739.5 2266.21   769.8 2265.81   778.5 2266.51   787.7 2269.59
#Mann= 5 ,-1,0
       0      .1       0     240     .05       0  431.53      .1       0
   492.9    .045       0  566.96      .1       0
Bank Sta=492.9,566.96
XS Rating Curve= 0 ,0
Exp/Cntr=0.3,0.1

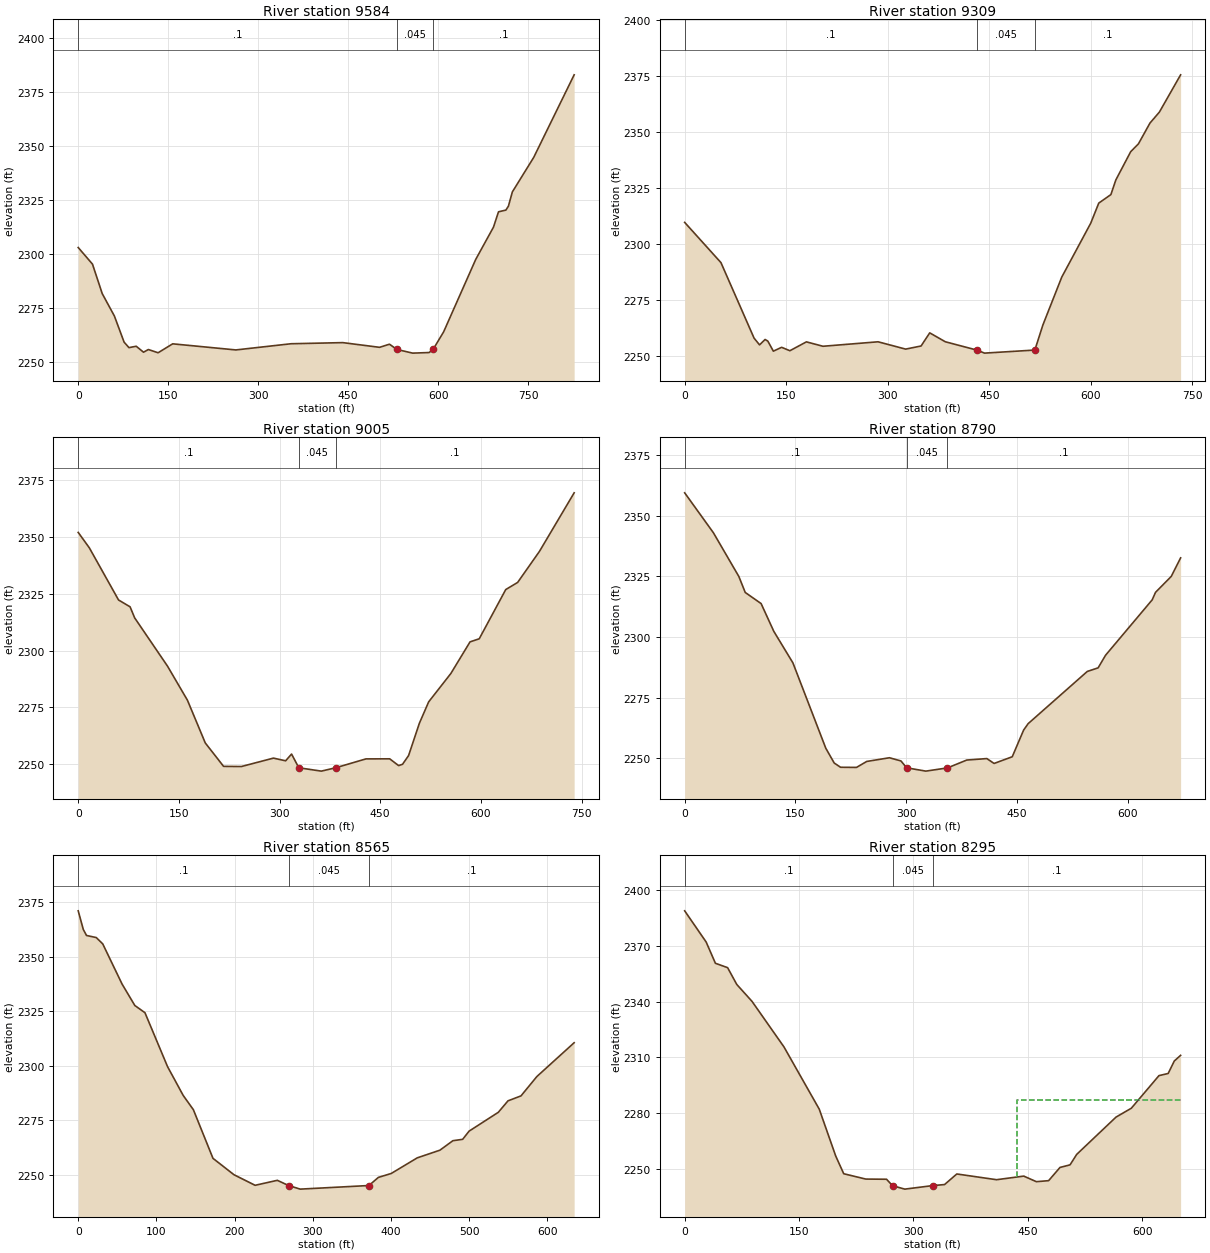
Type RM Length L Ch R = 1 ,9584    ,245.3,275.3,284
XS GIS Cut Line= 3
2215468.67932272629043.7002189192215937.77926711629119.164123017
2216278.38661804629206.865416969
#Sta/Elev= 30
       0 2303.01    23.8 2295.31      40 2281.67    60.3 2271.26    76.5 2259.14
    84.6 2256.59    96.7 2257.23   108.9 2254.47     117 2255.71   133.2 2254.21
   157.5 2258.35   262.8 2255.52   354.9 2258.39   441.1 2258.91   502.4 2256.73
   518.9 2258.18   531.3 2255.75   531.3 2255.74   557.6 2254.04     585 2254.31
  591.69 2255.78   609.2  2263.9   662.7 2297.49   692.3 2312.46   700.7 2319.58
     713 2320.37   717.2 2322.19   723.8 2328.81   759.4 2344.81   826.8  2383.1
#Mann= 3 ,-1,0
       0      .1       0   531.3    .045       0  591.69      .1       0
Bank Sta=531.3,591.69
XS Rating Curve= 0 ,0
Exp/Cntr(USF)=0,0
Exp/Cntr=0.3,0.1

Type RM Length L Ch R = 1 ,9309    ,310.9,304,294
XS GIS Cut Line= 3
2215427.51592581629178.155239508 2215763.1776492629242.104908881
2216025.22166775629532.144391145
#Sta/Elev= 30
       0 2309.69    53.6 2291.75   102.5  2258.1   110.6 2255.09   118.8 2257.49
   122.8 2256.78     131 2252.28   143.2    2254   155.4 2252.48   179.8 2256.43
   204.3 2254.47   285.7 2256.46   326.4  2253.2   349.2 2254.59     362 2260.44
     385 2256.48   432.4  2252.7   442.9 2251.41   517.3 2252.78   529.1 2263.92
     557 2285.28   599.8 2309.32   611.7 2318.29   629.6 2322.08   636.9  2328.6
   658.9 2341.23   670.3  2344.7   687.3 2353.95   701.2 2358.84   732.6 2375.47
#Mann= 3 ,-1,0
       0      .1       0   432.4    .045       0   517.3      .1       0
Bank Sta=432.4,517.3
XS Rating Curve= 0 ,0
Exp/Cntr=0.3,0.1

Type RM Length L Ch R = 1 ,9005    ,216.9,214.8,213.3
XS GIS Cut Line= 2
2215293.27673482629363.9119200912215960.21448184629682.084056287
#Sta/Elev= 30
       0 2351.96    16.5 2345.22    60.1 2322.25    77.3 2319.24    84.1 2314.39
     133 2293.18   162.8 2278.14   189.3 2259.39   216.6 2249.08   243.2 2249.02
   290.9 2252.71     309 2251.53   317.9  2254.5  328.65 2248.47   362.2 2246.99
   383.8 2248.48   428.7 2252.37   464.1  2252.4   477.4 2249.42   483.2    2250
   492.2 2253.82   508.4 2268.11   522.2 2277.47   555.2 2289.92   583.8 2303.83
   597.5 2305.19     637 2326.84   654.7 2329.96   687.2 2343.61   738.9 2369.37
#Mann= 3 ,-1,0
       0      .1       0  328.65    .045       0   383.8      .1       0
Bank Sta=328.65,383.8
XS Rating Curve= 0 ,0
Exp/Cntr(USF)=0,0
Exp/Cntr=0.3,0.1

Type RM Length L Ch R = 1 ,8790    ,228.5,224.7,223.3
XS GIS Cut Line= 2
2215216.01819123629589.081381278 2215839.9968564629837.549713983
#Sta/Elev= 30
       0 2359.36    38.9 2342.91    73.4 2324.88      82 2318.32   103.5 2313.74
   120.7  2302.3   146.6  2289.3   191.1 2254.15   202.5 2248.06   211.1 2246.31
   232.7 2246.25   246.5  2248.7   277.3 2250.23   292.9 2248.91   300.6 2246.09
   326.6 2244.72  355.88 2246.05     382 2249.28   409.2 2249.89     419 2247.88
   443.6 2250.64     459 2261.63   465.1 2264.27   545.2 2285.78   559.9 2287.26
   569.9 2292.43   633.1 2315.27   637.6 2318.36   658.9 2324.92   671.6 2332.57
#Mann= 3 ,-1,0
       0      .1       0   300.6    .045       0  355.88      .1       0
Bank Sta=300.6,355.88
XS Rating Curve= 0 ,0
Exp/Cntr=0.3,0.1

Type RM Length L Ch R = 1 ,8565    ,273.9,270.1,264.7
XS GIS Cut Line= 2
2215153.91440957629842.4750668122215765.78390225630010.172631474
#Sta/Elev= 30
       0 2370.95     6.5 2362.43    10.6 2359.67    23.1 2358.71    31.4  2355.8
    56.1 2337.43    72.4 2327.62    85.4  2324.3   114.3 2299.61   134.3 2286.44
   147.3 2279.92   172.4 2257.64   199.3 2250.13   226.3  2245.3   254.7 2247.58
  269.21 2245.18     284 2243.55   371.9  2245.2   383.9 2248.91   400.5 2250.73
   433.7 2257.87   462.7 2261.38   479.3 2265.72   491.8 2266.35     500 2270.09
   537.4 2278.72   549.8 2283.97   566.4 2286.23   586.7 2295.09   634.4 2310.57
#Mann= 3 ,-1,0
       0      .1       0  269.21    .045       0   371.9      .1       0
Bank Sta=269.21,371.9
XS Rating Curve= 0 ,0
Exp/Cntr(USF)=0,0
Exp/Cntr=0.3,0.1

Type RM Length L Ch R = 1 ,8295    ,245.4,254.9,261.4
XS GIS Cut Line= 3
 2215087.9937154630163.4437139832215494.03333412 630188.49109526
2215736.43114218630164.332761613
#Sta/Elev= 30
       0    2389    28.2 2372.16    40.3 2360.72    56.3 2358.36    68.3 2349.31
    88.3 2340.19   130.2 2315.63   176.5 2282.05   198.1 2256.77   208.6 2247.24
   237.5 2244.36   264.7 2244.27   272.7 2240.76   288.7 2238.94  325.64 2240.86
   340.8  2241.4   356.9 2247.11     409 2244.02   444.7 2245.96   461.2 2242.96
   477.3  2243.5   492.2 2250.63   505.4 2252.03   514.1 2257.66   565.7 2277.78
   585.8 2282.57     622 2300.14   634.1  2301.3   642.1 2308.01   650.4 2311.08
#Mann= 3 ,-1,0
       0      .1       0   272.7    .045       0  325.64      .1       0
#XS Ineff= 2 , 0
                          436.07         2286.97
Permanent Ineff=
       F       F
Bank Sta=272.7,325.64
XS Rating Curve= 0 ,0
Exp/Cntr=0.3,0.1

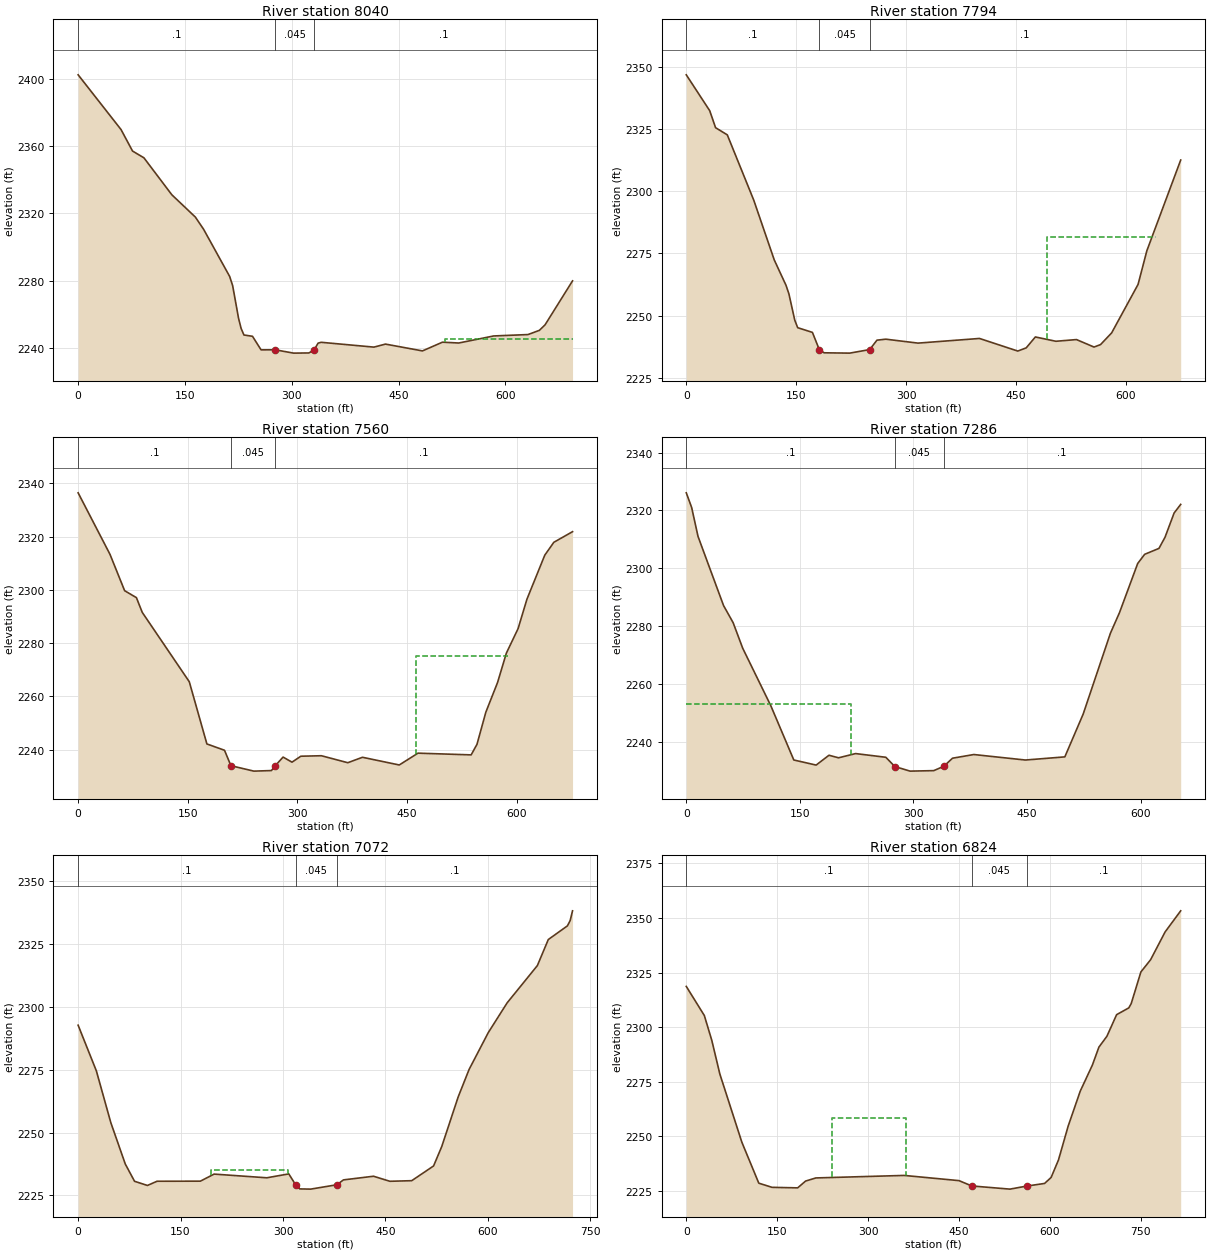
Type RM Length L Ch R = 1 ,8040    ,257.5,246.5,240.3
XS GIS Cut Line= 4
2215036.07287764630395.4237935352215314.81342431630418.085626597
2215400.92838995630452.0783761912215722.72641943630467.941659334
#Sta/Elev= 30
       0 2402.53    60.3  2369.9    76.4 2357.13    92.4 2353.09   131.6 2331.07
   164.6 2317.81   176.2 2310.53   212.8 2282.44     217 2276.99   225.3 2257.51
   228.9 2251.45   232.9 2247.53   244.9 2246.78   256.9 2238.69     277 2238.71
   302.6 2236.74   324.1 2236.85  331.35 2238.62     337 2242.67   341.3 2243.19
   415.5 2240.32   431.6 2242.12   483.6 2238.06   511.7 2243.26   534.6 2242.77
   583.7 2246.97   631.8  2247.8   647.8  2250.3   655.8 2253.59   694.4 2279.79
#Mann= 3 ,-1,0
       0      .1       0     277    .045       0  331.35      .1       0
#XS Ineff= 2 , 0
                          515.12         2245.33
Permanent Ineff=
       F       F
Bank Sta=277,331.35
XS Rating Curve= 0 ,0
Exp/Cntr(USF)=0,0
Exp/Cntr=0.3,0.1

Type RM Length L Ch R = 1 ,7794    ,233.3,233.7,235
XS GIS Cut Line= 2
2215088.23888519630660.322433912     2215762.274      630695.767
#Sta/Elev= 30
       0 2346.69      32 2332.29      40 2325.47      56 2322.59    92.1  2296.4
   120.1  2272.4   136.1 2262.25   140.1 2258.79   148.1 2248.22   152.1 2245.19
   172.2 2243.31  181.55 2236.43   188.2 2235.11   223.1 2234.98   250.4  2236.4
   260.3 2240.18   272.3 2240.58   316.4    2239   400.3 2240.87   452.6 2235.81
   464.1  2237.1   476.6 2241.47   504.6 2239.74   532.7 2240.42   556.7 2237.42
   565.6 2238.41   580.7 2243.09   616.8 2262.55   628.8 2276.07     675 2312.48
#Mann= 3 ,-1,0
       0      .1       0  181.55    .045       0   250.4      .1       0
#XS Ineff= 1 ,-1
  492.17  641.35 2281.69
Permanent Ineff=
       F
Bank Sta=181.55,250.4
XS Rating Curve= 0 ,0
Exp/Cntr=0.3,0.1

Type RM Length L Ch R = 1 ,7560    ,274.8,274.2,273.4
XS GIS Cut Line= 2
2215064.78199422630884.6818643742215738.32181307630944.155579063
#Sta/Elev= 30
       0 2336.42    43.6  2313.3    63.6 2299.66    79.7 2297.06    87.7 2291.52
     152 2265.48   176.1 2242.11   200.2 2239.73  208.95 2233.94   240.3  2231.9
   264.4 2232.11   269.3 2233.84   280.3 2237.17   292.5 2235.27   304.6  2237.5
   332.7 2237.68   368.8 2235.06   388.9  2237.1   439.2 2234.21   464.8 2238.65
   537.5    2238   545.5 2241.97   557.6 2254.03   573.6 2265.16   585.7 2276.22
   601.7 2285.42   613.8 2296.45   638.2    2313   650.6 2317.84   676.2 2321.83
#Mann= 3 ,-1,0
       0      .1       0  208.95    .045       0   269.3      .1       0
#XS Ineff= 1 ,-1
  461.57   587.8 2275.09
Permanent Ineff=
       F
Bank Sta=208.95,269.3
XS Rating Curve= 0 ,0
Exp/Cntr(USF)=0,0
Exp/Cntr=0.3,0.1

Type RM Length L Ch R = 1 ,7286    ,215.9,214.3,212.7
XS GIS Cut Line= 3
2214989.47418679631097.0113425142215223.66744244631175.233842867
2215628.84762782631201.416842867
#Sta/Elev= 30
       0 2326.08     7.1 2321.01    15.5 2311.01    49.2  2287.1    61.9 2281.15
    74.5 2272.34   111.7  2252.4     142 2233.67   171.5 2231.91   188.4 2235.31
   201.1 2234.43   223.6 2235.89   263.5 2234.61   275.4 2231.41   295.5 2229.82
   326.8 2229.99     340 2231.48   351.6 2234.29   379.7 2235.56   447.8 2233.66
   499.9 2234.75   524.1 2249.54   560.1 2277.52   572.1 2284.65   596.1 2301.63
   605.3 2304.81   624.2 2306.86   632.2 2310.71   644.2 2319.09   652.9 2322.08
#Mann= 3 ,-1,0
       0      .1       0   275.4    .045       0     340      .1       0
#XS Ineff= 2 , 0
          218.03 2252.93
Permanent Ineff=
       F       F
Bank Sta=275.4,340
XS Rating Curve= 0 ,0
Exp/Cntr=0.3,0.1

Type RM Length L Ch R = 1 ,7072    ,246.2,247.3,246.4
XS GIS Cut Line= 3
2214950.90635022631301.4285651262215215.23397106 631392.29118479
 2215659.6347836631398.899375311
#Sta/Elev= 30
       0 2292.69    26.7 2274.51    47.9 2253.89      69 2237.49    82.6 2230.59
   101.5 2228.93   115.5  2230.6     179 2230.64   199.1 2233.45   276.3 2231.98
   308.5 2233.53  318.63 2229.12   324.5 2227.56   340.4 2227.47  378.93 2229.21
   388.5 2231.14   432.5  2232.6   456.5 2230.59   488.5 2230.83   520.5 2236.69
   532.5 2244.44   556.5 2264.14   572.5 2275.09   600.6 2289.75   628.2 2301.58
   672.5 2316.42   688.5 2326.78   716.5 2332.22   720.5 2334.32     724  2338.2
#Mann= 3 ,-1,0
       0      .1       0  318.63    .045       0  378.93      .1       0
#XS Ineff= 1 ,-1
  195.26  307.47  2235.2
Permanent Ineff=
       F
Bank Sta=318.63,378.93
XS Rating Curve= 0 ,0
Exp/Cntr(USF)=0,0
Exp/Cntr=0.3,0.1

Type RM Length L Ch R = 1 ,6824    ,191.7,233.2,258.3
XS GIS Cut Line= 3
     2214832.497       631498.382215202.80298482 631640.82382839
2215621.81134181631621.916299788
#Sta/Elev= 30
       0 2318.67    29.8 2305.35    42.2 2293.89    55.4 2278.58    91.7 2247.38
   119.7 2228.59   141.5 2226.68   183.9 2226.44   196.9 2229.54   213.9 2230.98
   359.7 2232.13   450.2 2229.75  471.35 2227.31   534.3 2225.86   562.3 2227.27
   591.5 2228.46   602.3 2231.21   614.4 2239.18   630.4 2254.69   650.4 2270.74
   670.4 2282.64   681.2 2290.88   694.4 2295.84   710.4 2305.73   730.5 2308.84
   734.5  2310.8   750.5  2325.3   766.5 2330.88   790.5 2343.63   816.2 2353.28
#Mann= 3 ,-1,0
       0      .1       0  471.35    .045       0   562.3      .1       0
#XS Ineff= 1 ,-1
  240.44  362.482258.417
Permanent Ineff=
       F
Bank Sta=471.35,562.3
XS Rating Curve= 0 ,0
Exp/Cntr=0.3,0.1

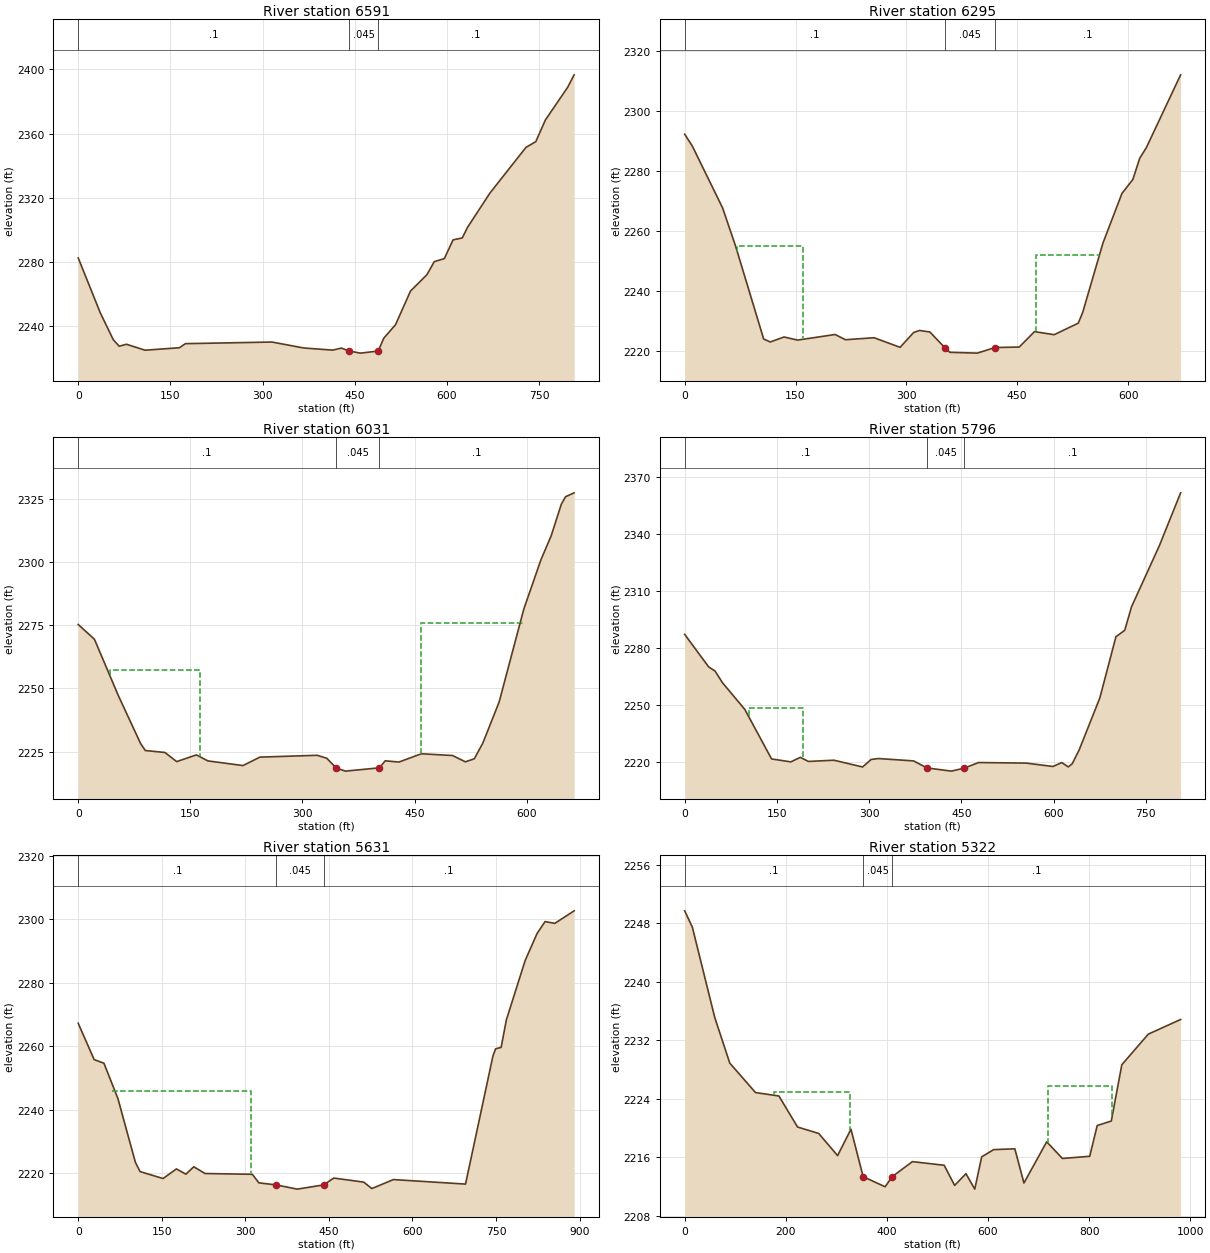
Type RM Length L Ch R = 1 ,6591    ,304.6,296.1,279.1
XS GIS Cut Line= 4
2214815.13324841631631.5671032142215195.76502242631783.225075671
2215329.58088047631942.3172624642215497.59412446 632030.04099163
#Sta/Elev= 30
       0 2282.67    35.9 2248.53    57.1 2231.75    66.7 2227.72    78.6 2228.92
   108.8 2225.23   164.7 2226.76   174.5  2229.3   315.4 2230.31   367.1 2226.61
   414.2 2225.28   428.4 2226.55  440.79 2224.73   459.3 2223.41   488.2  2224.7
   497.4 2232.72   516.5 2241.13   540.9 2262.06   567.6 2272.22   579.5 2280.32
   595.9 2282.23   610.1 2293.88   625.1 2295.08   633.5 2301.59   670.2 2323.05
   728.8 2351.45   744.8 2355.03   760.4  2368.5   796.7 2388.87   807.2 2396.59
#Mann= 3 ,-1,0
       0      .1       0  440.79    .045       0   488.2      .1       0
Bank Sta=440.79,488.2
XS Rating Curve= 0 ,0
Exp/Cntr(USF)=0,0
Exp/Cntr=0.3,0.1

Type RM Length L Ch R = 1 ,6295    ,257,263.5,266.5
XS GIS Cut Line= 3
2214663.69359193631803.6156661252215046.08659193632023.776795966
2215249.01589033 632131.63818711
#Sta/Elev= 30
       0  2292.3    10.3 2288.38    51.3 2267.79    68.9 2255.05   106.9 2224.14
   115.9 2223.16   134.4 2224.82   152.9 2223.79   203.6 2225.65   217.5 2223.91
   256.3 2224.57   291.5 2221.38   309.8 2226.31   317.8    2227   331.8 2226.48
  351.96 2221.29   358.9 2219.72     396 2219.45     420 2221.32   452.7 2221.47
   473.4 2226.61     500 2225.58   532.6 2229.43   538.5 2232.93   565.9    2256
   591.7 2272.59   606.5 2277.25   615.7 2284.26   624.8 2287.87   671.1 2312.06
#Mann= 3 ,-1,0
       0      .1       0  351.96    .045       0     420      .1       0
#XS Ineff= 2 ,-1
    71.4  160.66 2255.09  475.59  561.02 2252.24
Permanent Ineff=
       F       F
Bank Sta=351.96,420
XS Rating Curve= 0 ,0
Exp/Cntr=0.3,0.1

Type RM Length L Ch R = 1 ,6031    ,228.6,235.7,239.6
XS GIS Cut Line= 2
2214567.22378709 631959.625506052215075.70694779 632385.63931859
#Sta/Elev= 30
       0 2275.27    21.7 2269.43    53.4 2247.32    83.4 2228.21    89.8 2225.41
     116 2224.65   131.7 2221.03   158.1 2223.69   173.4 2221.32   220.4 2219.47
   243.1 2222.81   319.6 2223.53   332.5 2222.36     345 2218.54   357.4 2217.27
  402.85 2218.57   410.7 2221.35   429.1 2220.86   458.9 2224.13   500.7 2223.45
   517.9 2220.95   529.9 2222.16   541.3  2228.4     563 2244.55   596.1 2281.39
     619 2300.88   632.7 2310.36   646.3 2322.89     652 2325.81   663.4 2327.33
#Mann= 3 ,-1,0
       0      .1       0     345    .045       0  402.85      .1       0
#XS Ineff= 2 ,-1
   42.08  163.21 2257.26  459.02  595.45 2275.73
Permanent Ineff=
       F       F
Bank Sta=345,402.85
XS Rating Curve= 0 ,0
Exp/Cntr(USF)=0,0
Exp/Cntr=0.3,0.1

Type RM Length L Ch R = 1 ,5796    ,162,164.4,166
XS GIS Cut Line= 3
 2214424.7695286632041.6359717522214770.31730049632462.125357698
2214974.30829979632626.977799434
#Sta/Elev= 30
       0 2287.13      39 2270.03    49.5 2267.82    61.5  2261.7    97.8 2247.67
   141.3 2221.64   172.6 2220.09   188.1 2222.48   201.3 2220.32   242.7 2220.97
   289.3 2217.41   303.3 2221.38   315.2 2221.84   372.2 2220.61  394.26 2216.89
   433.8 2215.23     455 2216.84   477.9 2219.74   555.5 2219.45   598.9 2217.66
   613.2 2219.74   623.8 2217.46   630.2 2219.09   641.6 2226.44   675.2 2253.77
   701.3 2285.89   715.6 2289.25   726.6 2301.58   771.9 2333.73   806.5 2361.54
#Mann= 3 ,-1,0
       0      .1       0  394.26    .045       0     455      .1       0
#XS Ineff= 1 ,-1
  103.83  193.082248.438
Permanent Ineff=
       F
Bank Sta=394.26,455
XS Rating Curve= 0 ,0
Exp/Cntr=0.3,0.1

Type RM Length L Ch R = 1 ,5631    ,318.5,309.6,295.5
XS GIS Cut Line= 4
2214265.47322648632179.546089946 2214506.6721805632381.095900837
 2214610.7511812 632536.38837808 2214932.9004691632754.458665273
#Sta/Elev= 30
       0 2267.24    28.6  2255.8    46.2 2254.65    71.3 2243.51   102.6 2223.45
     111 2220.51   152.3 2218.32   176.3 2221.35   193.3  2219.7   207.5 2222.02
   227.7  2219.9   312.6 2219.65   324.2 2216.97  355.62  2216.3   393.3 2214.98
   440.6 2216.31   458.9 2218.47   512.6 2217.18   527.1 2215.16   565.8 2217.99
   695.3 2216.57   744.5 2256.93   749.3  2259.2   759.2 2259.64   768.7 2268.37
   802.4 2287.04   823.8 2295.56   838.1 2299.29   855.6 2298.73   890.3 2302.68
#Mann= 3 ,-1,0
       0      .1       0  355.62    .045       0   440.6      .1       0
#XS Ineff= 1 ,-1
   60.11  309.65 2245.91
Permanent Ineff=
       F
Bank Sta=355.62,440.6
XS Rating Curve= 0 ,0
Exp/Cntr(USF)=0,0
Exp/Cntr=0.3,0.1

Type RM Length L Ch R = 1 ,5322    ,377.3,386.4,367.9
XS GIS Cut Line= 3
2213967.02822881632388.9280144782214221.39775671632536.857070974
     2214831.488       632852.11
#Sta/Elev= 30
       0 2249.71    15.2 2247.47    59.5 2235.13    89.2  2228.9   140.1 2224.87
   186.4  2224.4   223.3 2220.16   265.1 2219.28   302.5 2216.25   328.9 2219.86
     353 2213.38   396.4 2211.99  410.65 2213.38   450.5 2215.43   513.3 2214.93
     534 2212.18   556.4 2213.78   573.8 2211.67   587.5 2216.08   611.2 2217.07
   653.1 2217.18   671.1  2212.5   716.1 2218.14   747.2 2215.86   801.2 2216.16
     816 2220.36   843.9 2220.98   864.7 2228.67     917 2232.85     981 2234.86
#Mann= 3 ,-1,0
       0      .1       0     353    .045       0  410.65      .1       0
#XS Ineff= 2 ,-1
  176.68  327.87 2224.99  719.49  845.17 2225.83
Permanent Ineff=
       F       F
Bank Sta=353,410.65
XS Rating Curve= 0 ,0
Exp/Cntr=0.3,0.1

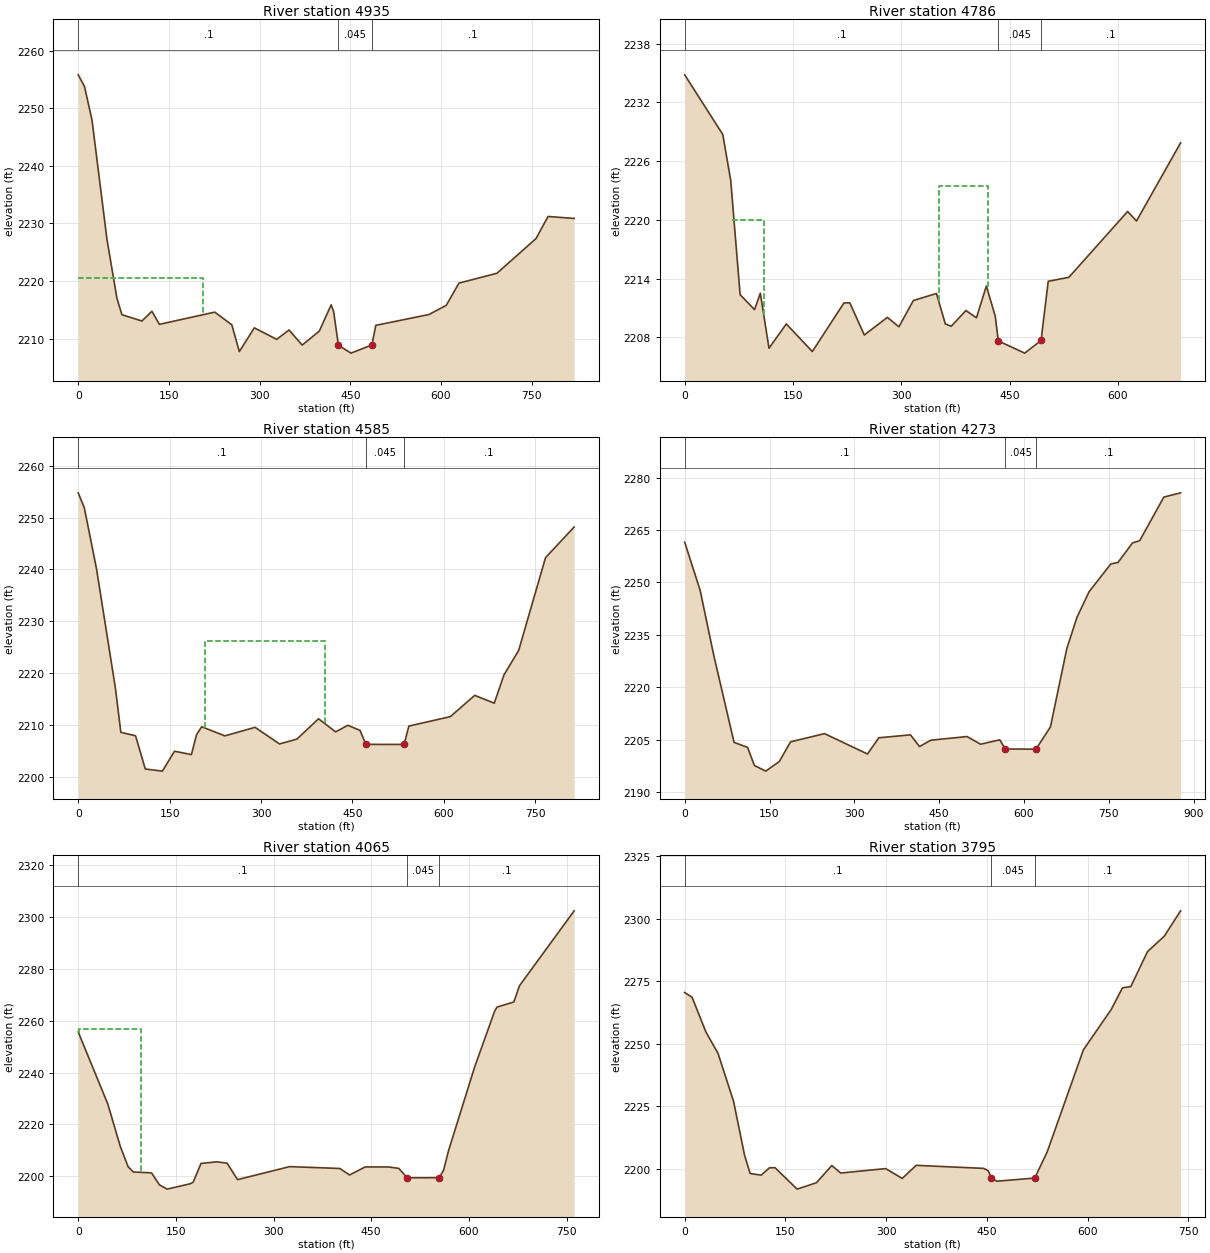
Type RM Length L Ch R = 1 ,4935    ,150.6,149.4,149.4
XS GIS Cut Line= 4
2213926.12491261632763.973535021  2214215.167166632838.642783813
2214452.42268232632891.6338636012214710.15202493632997.616023177
#Sta/Elev= 30
       0 2255.79    10.4 2253.77    22.8 2247.94    47.6 2227.19    64.1 2216.96
    72.3 2214.13   105.4 2213.04   121.9 2214.73   134.3 2212.46   225.9 2214.58
   254.1 2212.37   266.5 2207.73   291.3 2211.85   328.3 2209.85   348.7 2211.48
   370.4 2208.86   398.7 2211.27   418.4 2215.84   422.5 2214.68  430.35 2208.83
   451.2 2207.46   485.8 2208.88   492.2 2212.28   580.3 2214.17   608.8 2215.76
   629.8 2219.62   692.6 2221.33   757.2 2227.35   777.1 2231.19   820.3 2230.85
#Mann= 3 ,-1,0
       0      .1       0  430.35    .045       0   485.8      .1       0
#XS Ineff= 2 , 0
          205.83 2220.58
Permanent Ineff=
       F       F
Bank Sta=430.35,485.8
XS Rating Curve= 0 ,0
Exp/Cntr(USF)=0,0
Exp/Cntr=0.3,0.1

Type RM Length L Ch R = 1 ,4786    ,206.7,201,192
XS GIS Cut Line= 3
     2213891.342      633002.6282214241.78506343633000.546281697
2214572.22204235633064.595387342
#Sta/Elev= 30
       0 2234.81    52.8 2228.72    63.8 2224.02    76.8 2212.37    96.8 2210.84
   104.8 2212.52   116.8  2206.9   140.8 2209.38   176.8 2206.56   220.7 2211.53
   228.8 2211.53   248.8 2208.25   280.8 2210.05   296.8 2209.09   316.8 2211.77
   348.8 2212.49     361 2209.39   369.2 2209.14   389.6 2210.75   404.2 2210.01
   417.9 2213.25   430.3 2210.15   434.4 2207.65     471  2206.4  493.69 2207.69
   503.6 2213.73   532.2 2214.14   613.6 2220.86   625.9 2219.89     687 2227.87
#Mann= 3 ,-1,0
       0      .1       0   434.4    .045       0  493.69      .1       0
#XS Ineff= 2 ,-1
   65.03  109.65 2220.04  351.91  419.492223.444
Permanent Ineff=
       F       F
Bank Sta=434.4,493.69
XS Rating Curve= 0 ,0
Exp/Cntr=0.3,0.1

Type RM Length L Ch R = 1 ,4585    ,318.7,312.1,299.8
XS GIS Cut Line= 2
2213846.23747762633247.2228186622214659.16881527633205.070823376
#Sta/Elev= 30
       0 2254.77      10  2251.9      30 2240.14    60.9 2217.22      70 2208.57
    94.1 2207.91   110.1  2201.5   138.1 2201.09   158.1 2204.93   185.8 2204.28
   194.2 2208.12   202.7 2209.65   240.7 2207.89   290.3 2209.54   330.4 2206.33
     359 2207.27   394.5 2211.19   422.5 2208.66   442.5 2209.93   462.6 2208.94
   472.2 2206.25  534.87 2206.24   542.7 2209.78   610.8  2211.6   650.8  2215.7
   682.9  2214.2   698.9 2219.67   722.9 2224.36     767 2242.26     814 2248.18
#Mann= 3 ,-1,0
       0      .1       0   472.2    .045       0  534.87      .1       0
#XS Ineff= 1 ,-1
  207.65  404.372226.275
Permanent Ineff=
       F
Bank Sta=472.2,534.87
XS Rating Curve= 0 ,0
Exp/Cntr(USF)=0,0
Exp/Cntr=0.3,0.1

Type RM Length L Ch R = 1 ,4273    ,189.5,207.6,228.6
XS GIS Cut Line= 3
2213856.90269227633525.7496828392214384.26360214633532.011186603
2214711.99554582633410.261605569
#Sta/Elev= 30
       0 2261.52    27.3 2247.76    51.3 2229.23    87.3 2204.24   111.3 2202.78
   123.3 2197.61   143.3    2196   167.3 2198.74   187.3 2204.38   247.3 2206.73
   323.3  2200.9   343.3 2205.54   399.3 2206.38   415.3 2203.03   435.3 2204.85
   499.3 2205.89   523.3  2203.7   557.2 2204.95   566.9 2202.34   621.2 2202.28
   646.8 2208.64   675.8 2231.09   693.7 2239.99   715.1 2247.32   753.5 2255.26
   766.3  2255.7   791.9 2261.28   804.7 2261.93   847.3  2274.4     877 2275.62
#Mann= 3 ,-1,0
       0      .1       0   566.9    .045       0   621.2      .1       0
Bank Sta=566.9,621.2
XS Rating Curve= 0 ,0
Exp/Cntr=0.3,0.1

Type RM Length L Ch R = 1 ,4065    ,272.4,269.8,267.5
XS GIS Cut Line= 3
2213863.54041641633657.4432932462214303.79458939633662.795927568
2214602.20395284633781.892041233
#Sta/Elev= 30
       0 2255.67    45.5 2227.84    64.6 2211.54    76.6  2203.7    84.6 2201.67
   112.6 2201.32   124.6 2196.73   136.6 2195.05   172.6 2197.16   176.6 2197.77
   188.6 2204.96   212.7 2205.57   228.7 2205.07   244.7 2198.72   324.7 2203.73
   401.8 2203.01   416.7  2200.5   440.7 2203.61   476.3 2203.61   492.4 2203.05
   505.3 2199.42   554.6 2199.46   561.3  2202.5   568.6 2209.79   608.6 2242.01
   639.4 2263.62   643.1 2265.26     669 2267.22   677.6 2273.47   761.6 2302.38
#Mann= 3 ,-1,0
       0      .1       0   505.3    .045       0   554.6      .1       0
#XS Ineff= 1 ,-1
     .58   96.46 2256.63
Permanent Ineff=
       F
Bank Sta=505.3,554.6
XS Rating Curve= 0 ,0
Exp/Cntr(USF)=0,0
Exp/Cntr=0.3,0.1

Type RM Length L Ch R = 1 ,3795    ,166.3,172.8,177.2
XS GIS Cut Line= 3
2213833.51144968633830.9276473522214173.20466621633914.162925423
2214547.61253008634019.241753813
#Sta/Elev= 30
       0 2270.49      11 2268.62    31.6 2254.75    49.7 2246.16    72.8    2227
    89.2 2205.47    97.5 2198.17   113.9  2197.5   126.3 2200.44   134.5 2200.49
   167.5 2191.92   196.3 2194.49   219.1 2201.35   232.3 2198.36   299.3 2200.12
     324  2196.2   344.8 2201.43   445.4 2200.21   451.9 2199.31   456.7 2196.37
   464.9 2195.09  521.34 2196.34   539.8 2206.73   593.8 2247.59   635.3 2263.74
     652 2272.38   664.4 2272.86   689.3 2286.85   714.3 2293.03   738.6 2303.15
#Mann= 3 ,-1,0
       0      .1       0   456.7    .045       0  521.34      .1       0
Bank Sta=456.7,521.34
XS Rating Curve= 0 ,0
Exp/Cntr=0.3,0.1