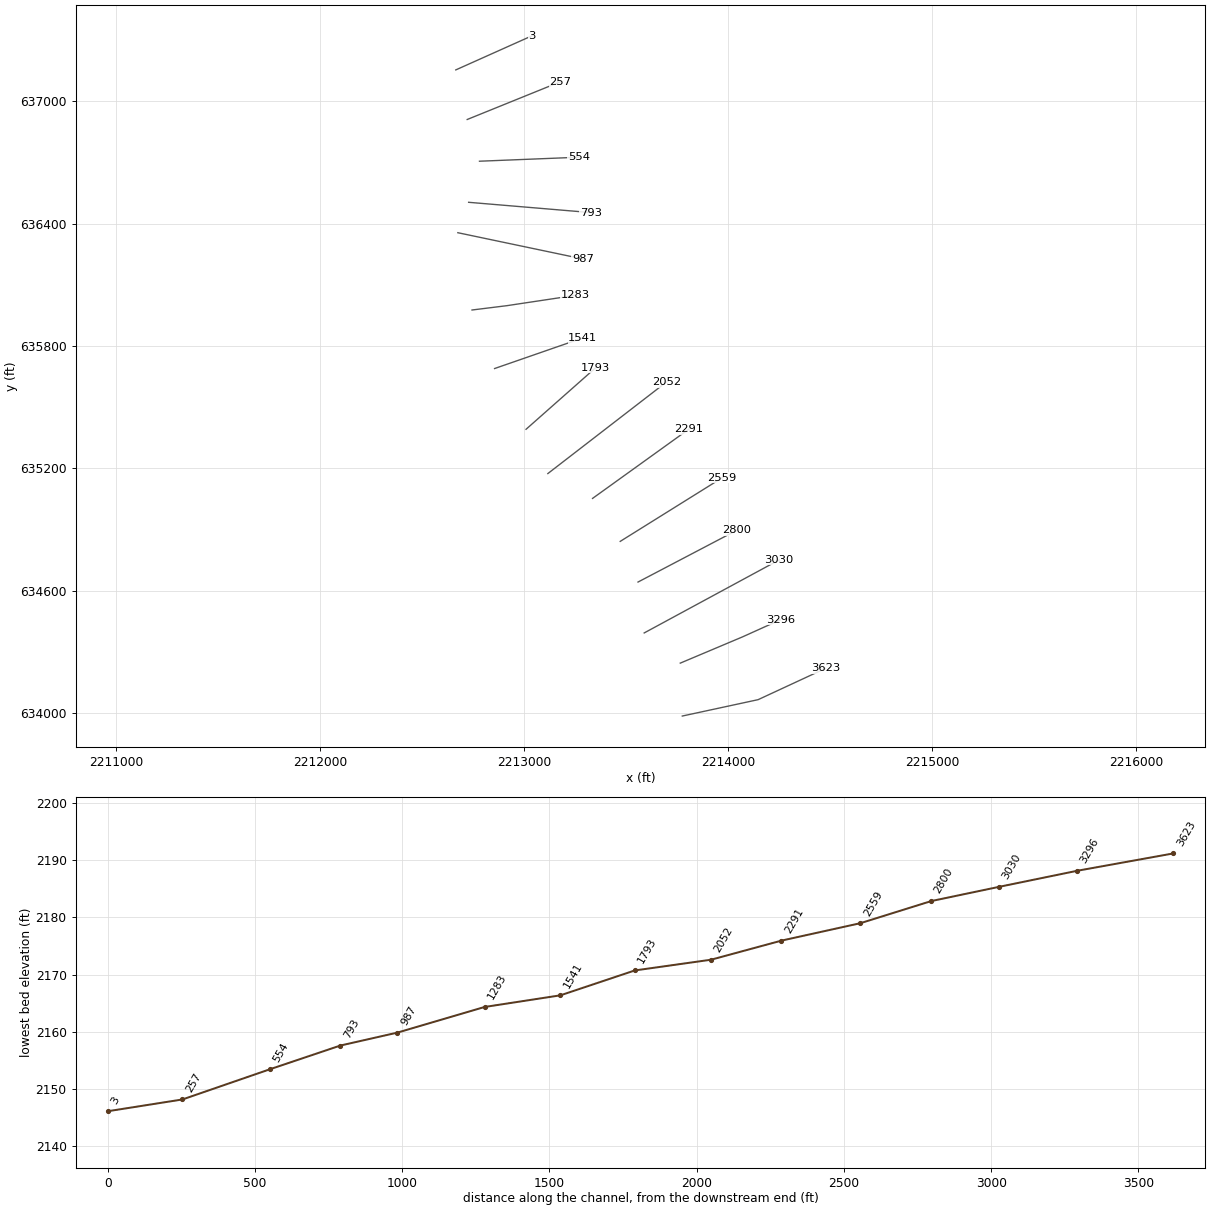
HEC-RAS study LFBUCKRV.prj: LFBUCKRV

--- LFBUCKRV.g01 (geometry) --- (continued)

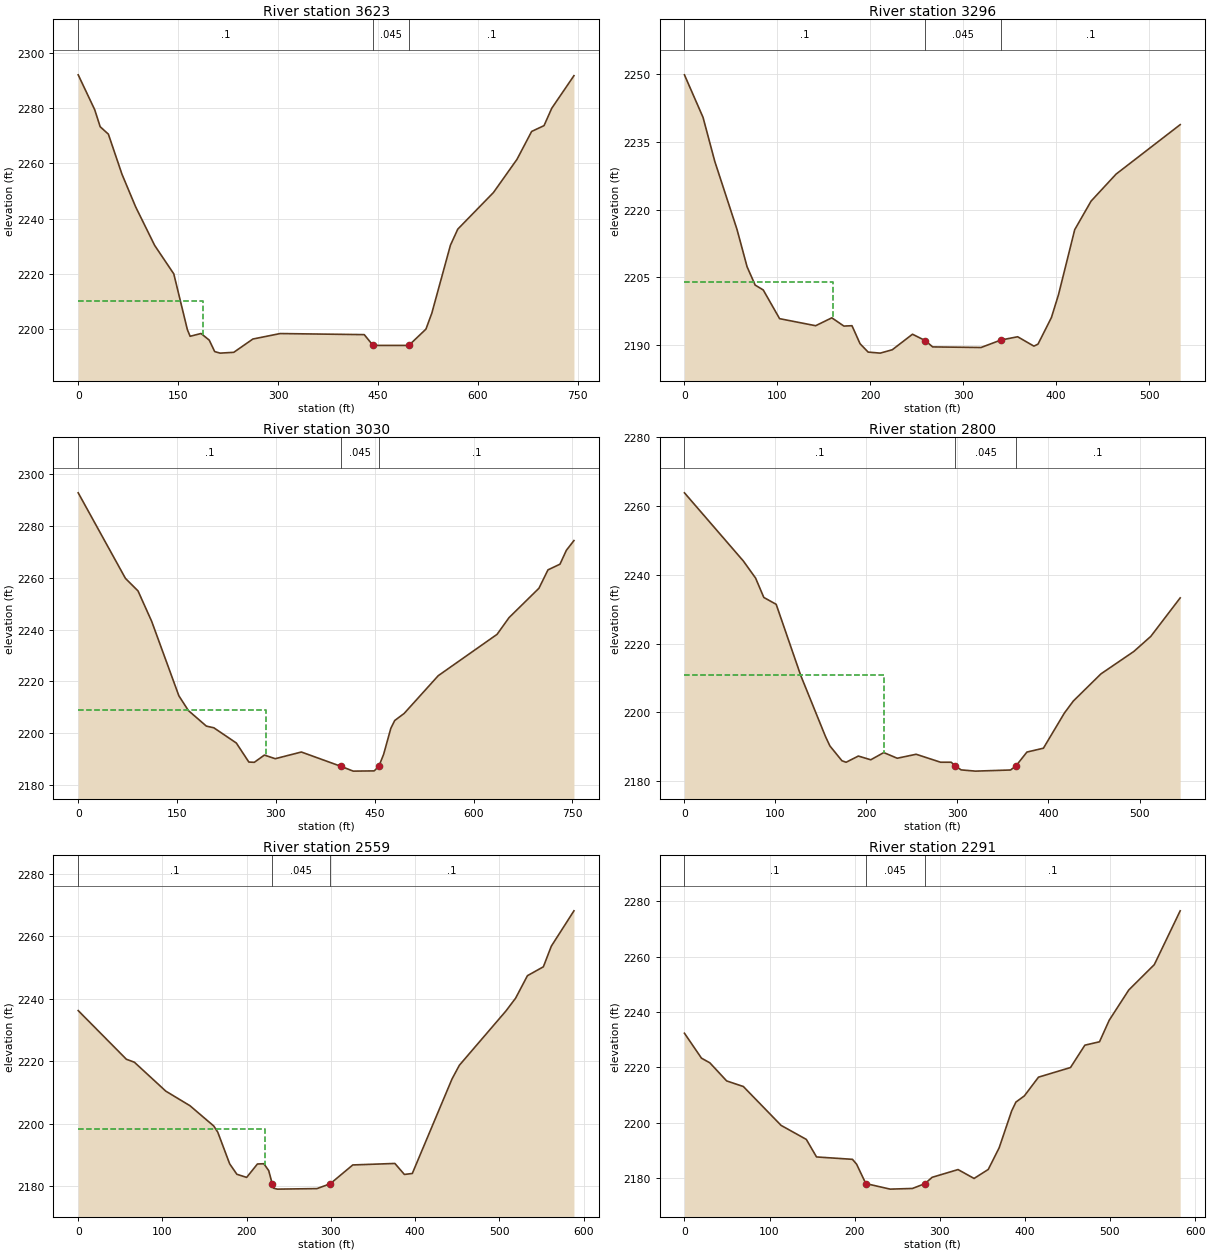
Type RM Length L Ch R = 1 ,3623    ,323.9,326.9,315.5
XS GIS Cut Line= 3
2213775.93174948633985.7434206232214147.64246629634066.032935453
2214477.72158281634219.177750778
#Sta/Elev= 30
       0 2292.16    24.8  2279.5      33 2273.33    45.3 2270.64    65.7 2256.11
    86.2 2244.28   114.8 2230.27   143.5 2219.95   163.9 2199.71     168 2197.31
   184.4 2198.32   196.7 2195.92   204.9 2191.76     213  2191.2   233.5 2191.49
   262.2 2196.31   303.1  2198.3   429.4 2197.91   442.6    2194  496.29 2193.99
     522  2199.9   530.8 2205.65   558.8 2230.35   569.8 2236.17   623.4 2249.47
   658.7  2261.5   680.7 2271.62   699.3 2273.73   710.9 2280.04   744.2 2291.85
#Mann= 3 ,-1,0
       0      .1       0   442.6    .045       0  496.29      .1       0
#XS Ineff= 2 , 0
          187.98 2210.08
Permanent Ineff=
       F       F
Bank Sta=442.6,496.29
XS Rating Curve= 0 ,0
Exp/Cntr(USF)=0,0
Exp/Cntr=0.3,0.1

Type RM Length L Ch R = 1 ,3296    ,255.7,265.3,256.1
XS GIS Cut Line= 3
 2213766.0355803  634245.17857092214071.05395068634373.776316894
2214255.63905643634457.093968348
#Sta/Elev= 30
       0 2249.88      20 2240.45    32.7 2230.65    56.6 2215.57    67.4 2207.31
    76.1 2203.25    84.8 2202.17   102.4  2195.8   141.2 2194.24   158.6 2195.99
   171.6 2194.16   180.3 2194.24     189 2190.24   197.7 2188.39   210.7 2188.16
   223.7 2188.91   245.4 2192.35   259.2 2190.94   267.1 2189.54   319.2 2189.41
   340.5 2191.06   358.6 2191.79   376.1 2189.71   380.5 2190.16   394.9 2196.04
   402.5  2201.1     420 2215.54   437.6 2221.87   464.5 2227.86   533.5 2238.83
#Mann= 3 ,-1,0
       0      .1       0   259.2    .045       0   340.5      .1       0
#XS Ineff= 2 , 0
          159.56 2203.83
Permanent Ineff=
       F       F
Bank Sta=259.2,340.5
XS Rating Curve= 0 ,0
Exp/Cntr=0.3,0.1

Type RM Length L Ch R = 1 ,3030    ,230.3,230.3,229.3
XS GIS Cut Line= 2
2213589.11213008634393.168733099 2214250.8376555634751.225695485
#Sta/Elev= 30
       0 2292.83    71.7 2259.79    90.8 2254.94   111.5 2243.21   152.8 2214.43
   167.2 2208.75   194.5 2202.74   205.9 2202.08     240 2196.21     259 2188.85
   267.3 2188.76   282.6 2191.55   299.1 2190.15   338.7 2192.73   399.2 2187.16
   417.4 2185.35   449.2 2185.44  456.24 2187.18   463.5  2191.8   474.5 2201.89
   480.4  2204.9   494.7 2207.62   546.4  2222.2   635.7 2238.17   653.9 2244.63
   699.3 2255.98     713 2263.08   731.2 2265.27   740.9 2270.63   752.4 2274.39
#Mann= 3 ,-1,0
       0      .1       0   399.2    .045       0  456.24      .1       0
#XS Ineff= 2 , 0
          285.61 2209.13
Permanent Ineff=
       F       F
Bank Sta=399.2,456.24
XS Rating Curve= 0 ,0
Exp/Cntr(USF)=0,0
Exp/Cntr=0.3,0.1

Type RM Length L Ch R = 1 ,2800    ,240.3,240.7,244.9
XS GIS Cut Line= 2
2213558.91494206 634642.750052122214041.33788939634895.687030379
#Sta/Elev= 30
       0 2263.87    64.7 2244.03    78.2 2239.04    87.2 2233.42   100.8 2231.41
   127.9 2210.62     155 2192.91   159.8  2190.2     173 2185.89   177.6 2185.44
   191.1 2187.25   204.7 2186.16     219 2188.26   233.8 2186.61   254.6 2187.77
   281.4 2185.45   293.1 2185.45  297.64 2184.37     304 2183.22   319.8 2182.86
   358.3 2183.19   364.2 2184.36   376.3 2188.41   394.4 2189.53   417.5 2199.78
   427.3 2203.27   457.6 2211.16   493.7 2217.68   512.4 2222.08   544.7 2233.29
#Mann= 3 ,-1,0
       0      .1       0  297.64    .045       0   364.2      .1       0
#XS Ineff= 2 , 0
          219.67 2210.87
Permanent Ineff=
       F       F
Bank Sta=297.64,364.2
XS Rating Curve= 0 ,0
Exp/Cntr=0.3,0.1

Type RM Length L Ch R = 1 ,2559    ,265.4,268,269.9
XS GIS Cut Line= 2
2213471.61091903634842.1338447132213970.99378701635153.694569859
#Sta/Elev= 30
       0 2236.22    57.2 2220.62    66.7 2219.67     104  2210.4   132.7 2205.73
     161 2199.21   165.7 2197.26   179.8 2187.12   188.4 2183.75     200 2182.75
   212.8 2187.05   220.4 2187.13   226.2 2184.93   230.4 2180.68     232 2179.29
   236.4 2178.99   283.5 2179.16   299.2  2180.7     326 2186.74     376 2187.22
   387.3 2183.69   396.7 2184.01   443.8 2214.28   452.6 2218.71   507.8 2236.08
   519.3 2240.18   533.4 2247.41   552.3 2250.26   561.7 2256.85   588.6  2268.2
#Mann= 3 ,-1,0
       0      .1       0   230.4    .045       0   299.2      .1       0
#XS Ineff= 2 , 0
          221.86 2198.31
Permanent Ineff=
       F       F
Bank Sta=230.4,299.2
XS Rating Curve= 0 ,0
Exp/Cntr(USF)=0,0
Exp/Cntr=0.3,0.1

Type RM Length L Ch R = 1 ,2291    ,237.9,239.1,240.2
XS GIS Cut Line= 2
2213335.93837915635052.7615225122213808.87642773635392.878761256
#Sta/Elev= 30
       0 2232.29      20 2223.28    29.9 2221.58    49.6 2215.05    69.2 2213.03
   113.6 2198.97   143.2 2193.91   155.2 2187.57   197.4 2186.71   202.3 2184.95
   213.1 2177.95   241.7 2175.94   267.9 2176.18  282.66 2177.93     291 2180.21
   321.5 2183.01   340.3  2179.8     357 2183.06   369.8 2190.89   384.5 2204.23
   389.5 2207.41   399.4 2209.64     416 2216.41   453.6 2219.89   470.5 2227.97
   487.7  2229.2   499.1 2236.98   522.1 2247.92   552.1 2257.09   582.5 2276.53
#Mann= 3 ,-1,0
       0      .1       0   213.1    .045       0  282.66      .1       0
Bank Sta=213.1,282.66
XS Rating Curve= 0 ,0
Exp/Cntr=0.3,0.1

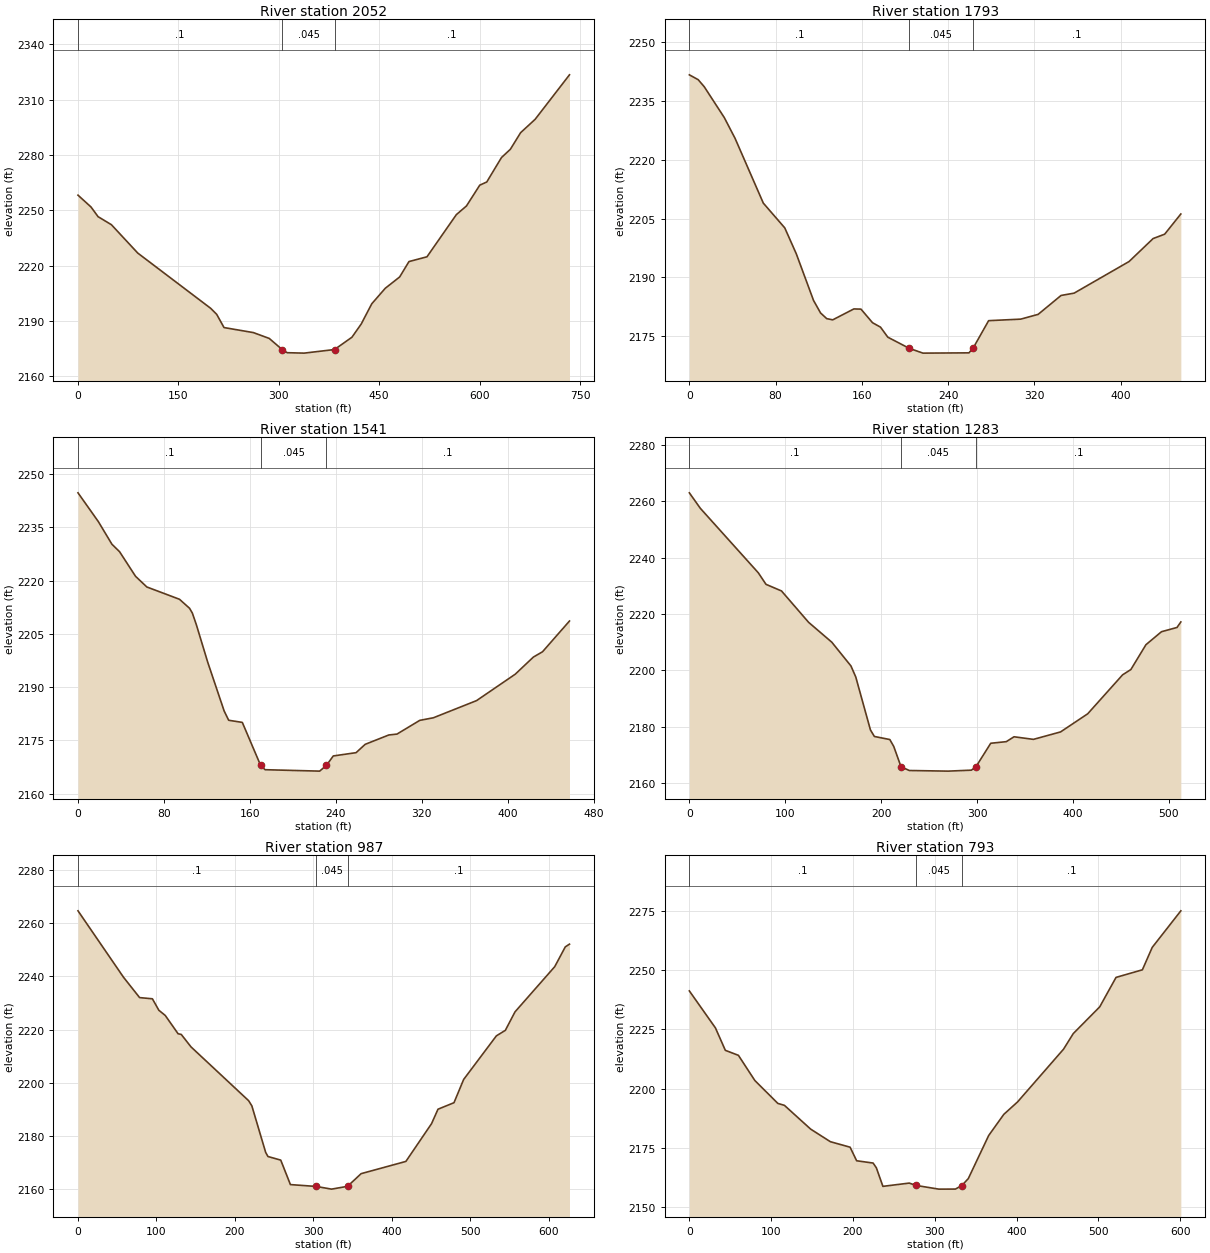
Type RM Length L Ch R = 1 ,2052    ,256.9,259.1,265.6
XS GIS Cut Line= 2
2213116.72661327635174.5829357392213698.00263132635623.287230375
#Sta/Elev= 30
       0 2258.26    19.5 2251.83      30  2246.6    49.9 2242.25    89.3 2226.86
   198.2 2196.91   207.2 2193.65   218.2 2186.46   262.1 2183.73   285.7 2180.58
   305.4 2174.44   312.6 2172.83   337.9  2172.6   383.3 2174.55   409.3 2181.22
   423.2 2188.42   438.9 2199.35   459.1 2207.77   480.6 2213.91   494.5 2222.25
   521.4 2224.84   565.3 2247.71   580.4 2252.41   600.3  2263.7   610.7  2265.4
   632.7 2278.65     646 2283.15   661.3 2292.14     683  2299.4   734.3 2323.52
#Mann= 3 ,-1,0
       0      .1       0   305.4    .045       0   383.3      .1       0
Bank Sta=305.4,383.3
XS Rating Curve= 0 ,0
Exp/Cntr(USF)=0,0
Exp/Cntr=0.3,0.1

Type RM Length L Ch R = 1 ,1793    ,266.3,252.4,242.8
XS GIS Cut Line= 2
2213009.83262026635391.7232873222213351.36943009635693.658096563
#Sta/Elev= 30
       0 2241.62     8.2 2240.38    13.8 2238.59    32.4 2230.73    42.4 2225.44
    68.6 2208.94    88.5 2202.63    99.2 2196.02   115.2 2184.14   121.7 2180.96
   127.4 2179.51     133  2179.2   152.6 2181.98   159.2 2181.93   169.9 2178.47
   177.3 2177.34   184.1 2174.78   203.9 2171.95   216.7 2170.72   259.4 2170.79
   263.4 2172.08   277.6 2178.99   307.4 2179.38   323.5 2180.59   344.8 2185.41
   356.9    2186   407.9 2194.06   430.2 2199.91   440.9 2201.02   455.9 2206.17
#Mann= 3 ,-1,0
       0      .1       0   203.9    .045       0   263.4      .1       0
Bank Sta=203.9,263.4
XS Rating Curve= 0 ,0
Exp/Cntr=0.3,0.1

Type RM Length L Ch R = 1 ,1541    ,265.1,257.6,253.9
XS GIS Cut Line= 2
2212855.57587678635689.5803973382213287.90772755 635839.53318716
#Sta/Elev= 30
       0 2244.67      19 2236.55    31.6 2230.21    38.7 2228.11    53.6 2221.18
    64.1 2218.18    94.5 2214.72   103.9 2212.18   106.5 2210.82   110.2 2207.57
   120.8    2197   136.1 2183.28   140.3 2180.68     153 2180.08     170 2168.01
   174.2 2166.77     225 2166.37  231.35    2168   237.7 2170.64   258.9 2171.56
   267.4 2173.91   289.4 2176.54     297 2176.79   318.2 2180.65   330.9 2181.38
   371.1 2186.21   407.1 2193.64     424 2198.46   432.5 2199.95   457.6  2208.6
#Mann= 3 ,-1,0
       0      .1       0     170    .045       0  231.35      .1       0
Bank Sta=170,231.35
XS Rating Curve= 0 ,0
Exp/Cntr(USF)=0,0
Exp/Cntr=0.3,0.1

Type RM Length L Ch R = 1 ,1283    ,305.1,295.7,287.1
XS GIS Cut Line= 3
  2212744.853328635976.5704175512212915.15662127 635997.70721394
2213252.14711258636048.437434233
#Sta/Elev= 30
       0 2262.93    11.4 2257.46    71.9 2234.59    79.9 2230.51    96.1 2228.16
   124.3 2217.06   148.5 2210.01   168.5 2201.58   173.5 2197.68   188.8 2178.92
   192.9 2176.61     209 2175.52   213.1 2173.07  220.68 2165.88   229.3 2164.55
   269.7 2164.33     294 2164.67   298.6 2165.77   314.2  2174.2   330.4 2174.77
   338.5  2176.5   358.7 2175.58     387 2178.22   415.3 2184.64   451.7 2198.45
   460.3 2200.32     476 2209.11   492.2 2213.72   508.4 2215.23   512.4 2217.18
#Mann= 3 ,-1,0
       0      .1       0  220.68    .045       0   298.6      .1       0
Bank Sta=220.68,298.6
XS Rating Curve= 0 ,0
Exp/Cntr=0.3,0.1

Type RM Length L Ch R = 1 ,987     ,191,194.2,197.9
XS GIS Cut Line= 2
 2212675.3797031636355.5724968872213288.08852293636226.875667149
#Sta/Elev= 30
       0 2264.72      58 2239.69    78.5 2232.02    94.8 2231.57     103 2227.26
   111.2 2225.28   127.5 2218.41   131.6 2218.13   143.9 2213.47   217.4 2193.17
   221.5 2191.21   239.1 2173.68     242 2172.14   258.3 2170.78   270.6 2161.56
   303.5 2160.86     323 2159.85  343.35  2160.9   360.7 2165.68   417.7 2170.29
   450.4 2184.52   458.6 2189.96     479 2192.42   491.3 2201.18     533 2217.61
   544.4 2219.68   556.7 2226.64   607.3 2243.67   620.8 2251.15   626.1 2252.16
#Mann= 3 ,-1,0
       0      .1       0   303.5    .045       0  343.35      .1       0
Bank Sta=303.5,343.35
XS Rating Curve= 0 ,0
Exp/Cntr(USF)=0,0
Exp/Cntr=0.3,0.1

Type RM Length L Ch R = 1 ,793     ,235,238.7,242.1
XS GIS Cut Line= 2
2212728.36116073636504.6367554032213327.08119472636454.277126376
#Sta/Elev= 30
       0 2241.25    31.9 2225.63      44 2216.17      60 2214.05    80.1 2203.41
   108.2 2193.76   116.2 2192.95   148.3 2182.91   172.4  2177.6   196.5 2175.28
   204.5 2169.55   224.6 2168.59   228.6 2166.58   236.6 2158.75   268.8 2160.13
     277 2159.15   304.9 2157.58   325.2  2157.6     333 2159.07     341 2162.03
   365.9 2180.21   384.4 2189.14   401.2 2194.39   457.4 2216.65   469.3 2223.24
   501.6 2234.51   521.6 2246.96   553.8 2250.16   565.8 2259.61   600.8 2275.06
#Mann= 3 ,-1,0
       0      .1       0     277    .045       0     333      .1       0
Bank Sta=277,333
XS Rating Curve= 0 ,0
Exp/Cntr(USF)=0,0
Exp/Cntr=0.3,0.1

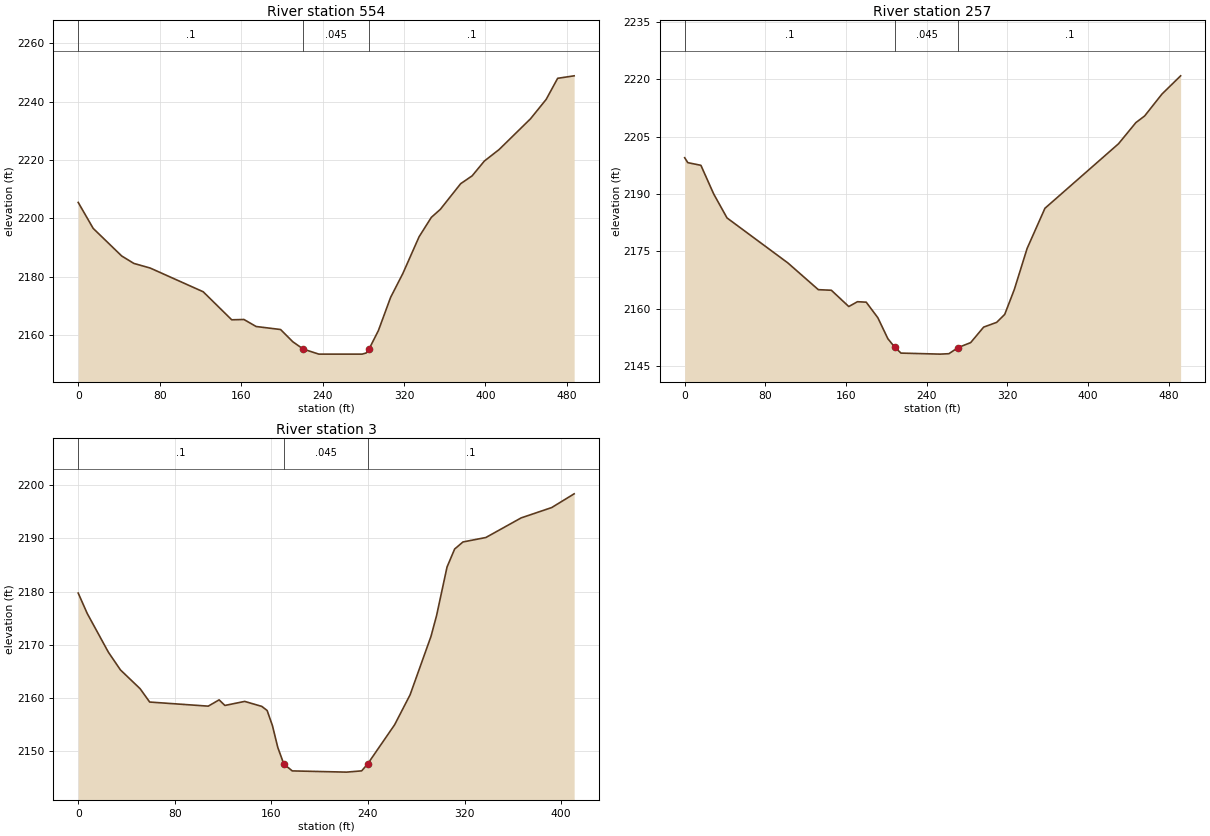
Type RM Length L Ch R = 1 ,554     ,289.3,297.4,311.4
XS GIS Cut Line= 2
2212781.51854692636706.0752715142213268.32829419636725.659571691
#Sta/Elev= 30
       0 2205.46    14.7 2196.56    42.7  2187.1    54.7 2184.54    70.7 2182.96
   122.8 2174.82   150.8 2165.21   162.8 2165.32   174.8 2162.91   198.8 2161.88
   210.8 2157.68   221.1 2155.17   236.4 2153.44   278.9 2153.44   282.9 2153.83
  285.75 2155.21   294.9 2161.52   306.9  2172.9   318.9 2181.08   334.9  2193.7
   346.9 2200.34   355.7 2203.07   375.7 2211.88     387 2214.58     399 2219.65
   413.5  2223.6   444.3 2234.13   459.7 2240.78     471 2248.02   487.2 2248.87
#Mann= 3 ,-1,0
       0      .1       0   221.1    .045       0  285.75      .1       0
Bank Sta=221.1,285.75
XS Rating Curve= 0 ,0
Exp/Cntr(USF)=0,0
Exp/Cntr=0.3,0.1

Type RM Length L Ch R = 1 ,257     ,252.5,253.6,255.2
XS GIS Cut Line= 2
 2212721.2749462636910.6239836612213177.30936461637095.275956762
#Sta/Elev= 30
       0 2199.52     3.1 2198.24    16.1 2197.54    28.8 2190.04      42 2183.78
   102.4    2172   132.6 2165.01   145.5 2164.86   162.8  2160.6   171.4 2161.86
   180.1 2161.74   191.6 2157.69   201.6 2152.17  208.59  2149.9   214.6 2148.42
   253.4 2148.15   262.1 2148.26   271.4 2149.88   283.7 2151.16   296.6 2155.22
   309.5 2156.46   317.5 2158.54     327 2165.04   339.7 2175.78   357.4  2186.3
   430.4 2203.18   447.6 2208.71   456.3 2210.45   473.5 2216.18     492 2220.95
#Mann= 3 ,-1,0
       0      .1       0  208.59    .045       0   271.4      .1       0
Bank Sta=208.59,271.4
XS Rating Curve= 0 ,0
Exp/Cntr(USF)=0,0
Exp/Cntr=0.3,0.1

Type RM Length L Ch R = 1 ,3       ,,,
XS GIS Cut Line= 2
2212665.31980283   637153.7712662213040.21926337637321.636696092
#Sta/Elev= 30
       0 2179.71     7.5 2175.87      25 2168.61      35 2165.28    51.3 2161.75
    59.2 2159.25   107.7 2158.48   116.7 2159.66   121.5 2158.61   137.9 2159.37
   152.1 2158.43   156.5 2157.66   160.9 2154.81   165.3 2150.74  170.31 2147.61
   177.3 2146.32   222.3 2146.09   234.8 2146.33   239.8 2147.64   262.1 2154.99
   274.9 2160.61   292.2 2171.57   296.8 2175.45   305.5  2184.6   311.8 2187.98
   318.7 2189.31   337.7 2190.15   366.9 2193.83   392.2 2195.77   410.8 2198.35
#Mann= 3 ,-1,0
       0      .1       0  170.31    .045       0   239.8      .1       0
Bank Sta=170.31,239.8
XS Rating Curve= 0 ,0
Exp/Cntr(USF)=0,0
Exp/Cntr=0.3,0.1
LCMann Table=0

Chan Stop Cuts=-1
Use User Specified Reach Order=0
Composite Channel Slope=5